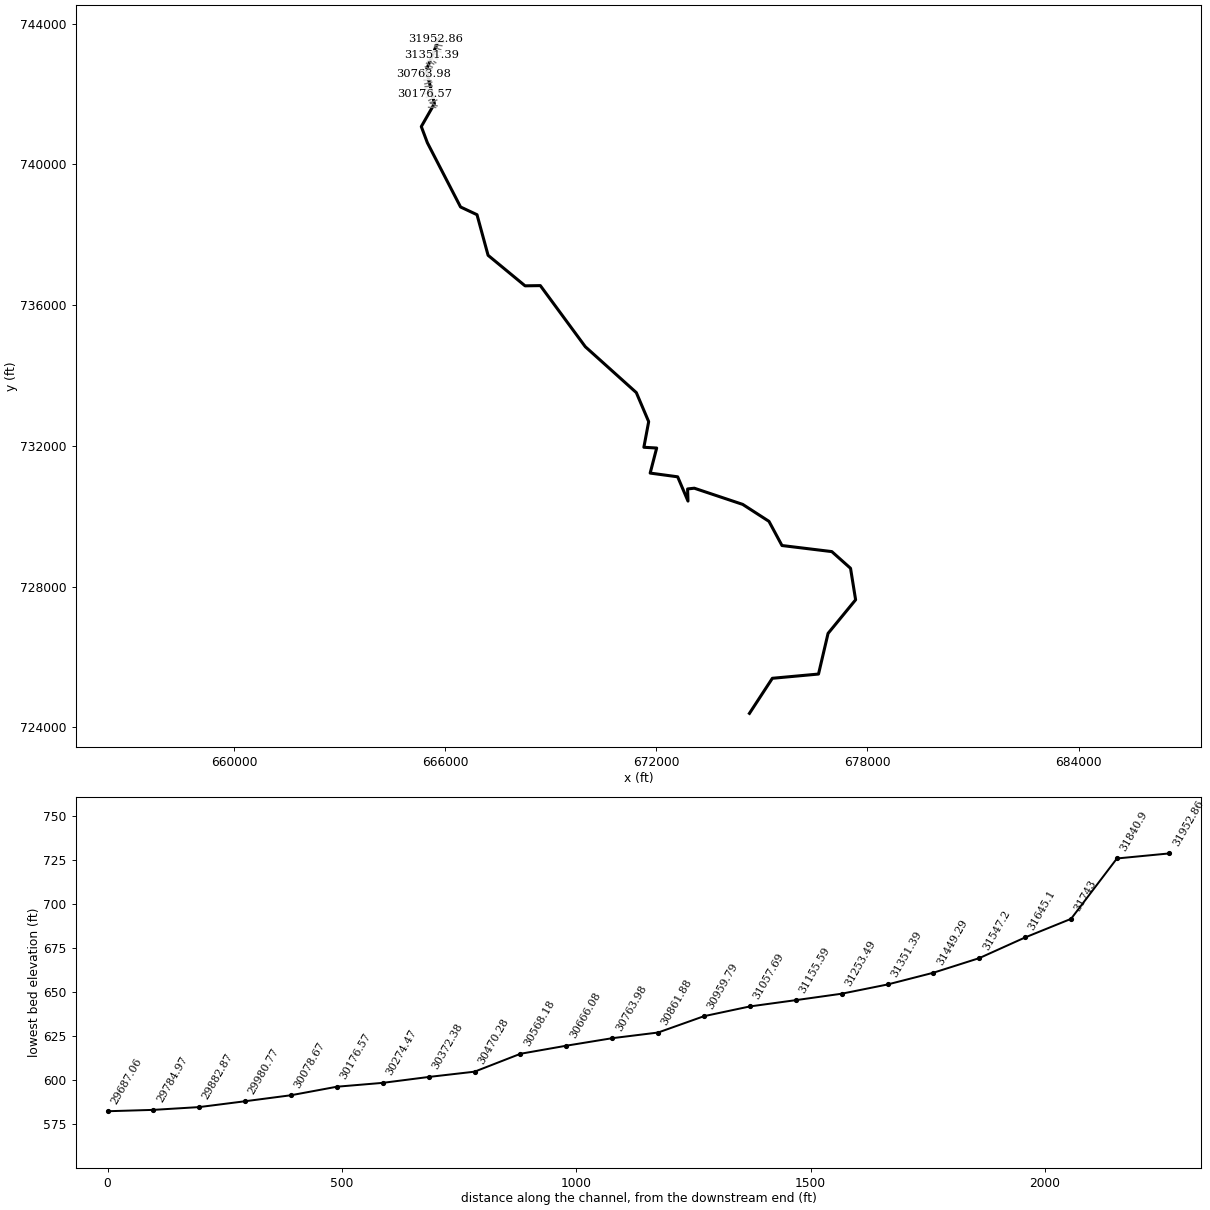
--- 4078_ras.prj (project) ---

Proj Title=4078
Current Plan=p01
Default Exp/Contr=0.3,0.1
English Units
Geom File=g01
Flow File=f01
Plan File=p01
Y Axis Title=Elevation
X Axis Title(PF)=Main Channel Distance
X Axis Title(XS)=Station
BEGIN DESCRIPTION:
RFD model 4078 exported to HEC-RAS
END DESCRIPTION:

--- 4078_ras.p01 (plan) ---

Plan Title=Plan 01
Program Version=4.10
Short Identifier=Plan 01
Geom File=g01
Flow File=f01
Subcritical Flow
Calc Critical at every XS
Secant Critical Depth

--- 4078_ras.f01 (steady flow) ---

Flow Title=Flow 01
Program Version=5.01
Number of Profiles= 6
Profile Names=10yr,25yr,50yr,100yr,100plus,500yr
River Rch & RM=4078,124,31952.86
  103.83  181.94  260.53  340.41     497  1017.3
River Rch & RM=4078,124,30666.08
  147.77  259.93  373.25  488.68  713.47 1393.39
River Rch & RM=4078,124,30568.18
  151.88  267.29  383.95  502.81   734.1  1428.7
River Rch & RM=4078,124,30372.38
  153.93  270.95  389.27  509.85  744.37 1446.23
River Rch & RM=4078,124,30274.47
  156.73  275.98  396.57  519.49  758.45  1470.2
River Rch & RM=4078,124,30176.57
  160.04  281.88  405.16  530.84  775.02 1498.33
River Rch & RM=4078,124,30078.67
  161.05   283.7  407.79  534.32  780.11 1506.95
River Rch & RM=4078,124,29882.87
  162.06  285.51  410.42   537.8  785.18 1515.54
River Rch & RM=4078,124,29687.06
  180.73  318.83  458.78  601.61  878.35 1671.29
River Rch & RM=4078,124,29589.16
  185.63  327.62  471.57  618.52  903.04  1712.4
River Rch & RM=4078,124,29491.26
  248.41  439.26  633.21   831.3  1213.7 2211.14
River Rch & RM=4078,124,29393.36
  249.92  442.02  637.27  836.73 1221.62 2224.08
River Rch & RM=4078,124, 29158.2
  254.45  450.28  649.44  852.97 1245.34 2262.72
River Rch & RM=4078,124,29008.97
   297.5  528.45  764.17 1005.81 1468.49 2618.78
River Rch & RM=4078,124,28859.73
  298.51  530.31  766.92 1009.51 1473.88 2627.43
River Rch & RM=4078,124,28710.49
  299.53  532.18  769.68  1013.2 1479.27 2636.07
River Rch & RM=4078,124,28561.26
  304.78  541.83  783.96 1032.36 1507.24 2680.82
River Rch & RM=4078,124,28412.02
   309.4  550.33  796.53 1049.22 1531.87 2720.16
River Rch & RM=4078,124,28208.72
  314.21  559.18  809.62 1066.78  1557.5 2760.98
River Rch & RM=4078,124,27869.59
  315.81  562.12  813.98 1072.62 1566.03 2774.53
River Rch & RM=4078,124,27666.94
  317.19  564.67  817.76  1077.7 1573.44 2786.37
River Rch & RM=4078,124,27419.64
  320.93  571.56  827.98 1091.45 1593.52  2818.4
River Rch & RM=4078,124,27172.35
  399.23  712.95 1034.82 1366.08 1994.48 3427.74
River Rch & RM=4078,124,26925.06
  402.32  718.79 1043.63  1378.1 2012.02 3455.74
River Rch & RM=4078,124,26677.77
  403.34  720.74 1046.56  1382.1 2017.86 3465.05
River Rch & RM=4078,124,26430.48
  407.11  727.87 1057.32 1396.76 2039.27 3499.11
River Rch & RM=4078,124,26183.18
  411.83  736.75 1070.64 1414.86 2065.69 3540.73
River Rch & RM=4078,124,25798.67
  415.76  744.19 1081.84 1430.12 2087.97 3576.03
River Rch & RM=4078,124,25560.25
     417  746.51 1085.32 1434.82 2094.84 3586.75
River Rch & RM=4078,124, 25258.2
  418.48  749.34 1089.61  1440.7 2103.43 3600.51
River Rch & RM=4078,124,24983.78
  419.01  750.33  1091.1 1442.72 2106.36 3605.09
River Rch & RM=4078,124,24787.62
  505.01  908.47 1325.21 1756.82 2564.95 4293.38
River Rch & RM=4078,124,24458.28
  508.51  915.15 1335.32 1770.64 2585.14  4324.7
River Rch & RM=4078,124, 24323.5
  514.68  926.83 1352.94 1794.67 2620.22 4378.59
River Rch & RM=4078,124,24078.45
  519.96  937.05 1368.55 1816.19 2651.63 4428.01
River Rch & RM=4078,124,23833.39
  521.33  939.69 1372.58 1821.73 2659.73 4440.68
River Rch & RM=4078,124,23588.34
  534.45  964.78 1410.61 1873.84  2735.8 4558.26
River Rch & RM=4078,124,23343.29
   539.9  975.27 1426.61 1895.85 2767.94 4608.29
River Rch & RM=4078,124,23098.23
  542.62  980.51 1434.59 1906.84 2783.98 4633.23
River Rch & RM=4078,124,22853.18
  550.49  995.84 1458.08 1939.32 2831.41 4707.72
River Rch & RM=4078,124,22608.12
  555.41 1005.43  1472.8 1959.69 2861.14 4754.38
River Rch & RM=4078,124,22363.07
  563.42 1021.17 1497.06  1993.4 2910.36 4832.21
River Rch & RM=4078,124,22118.01
  566.15 1026.58 1505.45  2005.1 2927.44 4859.41
River Rch & RM=4078,124,21872.96
  569.44 1033.08 1515.51 2019.12 2947.92 4891.96
River Rch & RM=4078,124,21627.91
  571.62  1037.4 1522.19 2028.45 2961.54 4913.61
River Rch & RM=4078,124,21382.85
  671.63 1225.19 1804.05 2411.16  3520.3  5736.6
River Rch & RM=4078,124,21220.05
  672.55 1227.01 1806.87  2415.1 3526.05 5745.51
River Rch & RM=4078,124, 21099.9
  673.08 1228.05 1808.48 2417.35 3529.33  5750.6
River Rch & RM=4078,124,20644.12
   673.6 1229.09 1810.09  2419.6 3532.61 5755.68
River Rch & RM=4078,124,20397.29
  676.37 1234.56 1818.55 2431.39 3549.83 5782.34
River Rch & RM=4078,124,20150.45
  687.26 1256.09 1851.88 2477.88  3617.7 5887.25
River Rch & RM=4078,124,19903.61
  688.02  1257.6 1854.24 2481.19 3622.53 5894.81
River Rch & RM=4078,124,19656.77
  688.85  1259.3 1856.92 2484.97 3628.06 5903.62
River Rch & RM=4078,124,19409.94
  699.07 1279.64 1888.53 2529.21 3692.65 6003.94
River Rch & RM=4078,124, 19163.1
  699.88 1281.31 1891.17 2532.95 3698.11 6012.68
River Rch & RM=4078,124,18916.26
  730.94 1342.28 1985.22 2663.74 3889.07  6303.5
River Rch & RM=4078,124,18669.43
  826.13 1532.53  2281.9 3080.17 4497.05 7236.07
River Rch & RM=4078,124,18422.59
  925.52 1729.91 2588.76  3509.9 5124.45  8174.5
River Rch & RM=4078,124,18175.75
  929.39 1737.83 2601.29  3527.7 5150.45 8214.32
River Rch & RM=4078,124,17928.92
  932.68 1744.59    2612 3542.95 5172.71 8248.55
River Rch & RM=4078,124,17682.08
  936.26 1751.95 2623.68 3559.61 5197.03 8286.03
River Rch & RM=4078,124,17435.24
  936.88 1753.23 2625.73 3562.54 5201.31 8292.64
River Rch & RM=4078,124,17188.41
  942.52    1765 2644.56 3589.55 5240.75 8354.21
River Rch & RM=4078,124,16941.57
  953.12 1787.16 2680.04 3640.49 5315.12 8470.26
River Rch & RM=4078,124,16694.73
  953.69 1788.37    2682 3643.32 5319.25 8476.81
River Rch & RM=4078,124,16447.89
  964.22  1810.6  2717.8 3694.97 5394.65 8595.46
River Rch & RM=4078,124,16201.06
  970.45 1823.77 2739.03 3725.62 5439.41 8665.91
River Rch & RM=4078,124,15954.22
   971.4 1825.78 2742.28 3730.32 5446.26 8676.72
River Rch & RM=4078,124,15707.38
  972.52 1828.18 2746.16 3735.94 5454.47  8689.7
River Rch & RM=4078,124,15460.55
  999.07  1885.4 2839.39 3871.69 5652.67 9006.33
River Rch & RM=4078,124,14961.82
 1004.05 1896.22 2857.09 3897.57 5690.45    9067
River Rch & RM=4078,124,14606.44
 1005.01  1898.3  2860.5 3902.56 5697.73 9078.69
River Rch & RM=4078,124,14213.73
 1010.29 1909.87 2879.52 3930.45 5738.46 9144.48
River Rch & RM=4078,124,13789.59
 1012.72 1915.16 2888.17  3943.1 5756.93 9174.12
River Rch & RM=4078,124,13440.84
 1014.67 1919.43  2895.2 3953.42 5771.99 9198.45
River Rch & RM=4078,124,13126.58
  1016.6 1923.74 2902.36    3964 5787.45  9223.8
River Rch & RM=4078,124, 12999.4
 1018.72 1928.44 2910.15 3975.51 5804.24 9251.24
River Rch & RM=4078,124,12717.55
 1019.75 1930.77 2914.01 3981.22 5812.58 9264.95
River Rch & RM=4078,124,12630.99
 1020.38 1932.17 2916.36 3984.71 5817.68 9273.38
River Rch & RM=4078,124,12050.42
 1023.02 1938.15 2926.34 3999.54 5839.33 9309.18
River Rch & RM=4078,124,11428.01
 1024.99 1942.58 2933.72 4010.48  5855.3 9335.46
River Rch & RM=4078,124,11178.23
 1025.69 1944.16 2936.36  4014.4 5861.03 9344.92
River Rch & RM=4078,124,10928.45
 1028.67 1950.86 2947.53 4030.97 5885.22 9384.81
River Rch & RM=4078,124,10678.68
 1029.37 1952.44 2950.17 4034.89 5890.94 9394.25
River Rch & RM=4078,124, 10428.9
  1030.2 1954.34 2953.35 4039.64 5897.87 9405.77
River Rch & RM=4078,124,10179.12
 1031.48 1957.27 2958.27 4046.97 5908.58 9423.58
River Rch & RM=4078,124,9929.349
 1066.69 2035.44  3087.8 4238.28 6187.89 9877.93
River Rch & RM=4078,124,9679.573
 1067.29 2036.81 3090.09 4241.69 6192.87 9886.16
River Rch & RM=4078,124,9429.797
 1071.61 2046.57 3106.43 4266.01 6228.38 9944.66
River Rch & RM=4078,124,9180.021
 1073.13    2050 3112.17 4274.55 6240.84 9965.15
River Rch & RM=4078,124,8930.245
 1075.43 2055.18 3120.81 4287.38 6259.58 9995.86
River Rch & RM=4078,124,8680.468
 1179.94 2284.71 3499.52 4845.31 7074.1611297.53
River Rch & RM=4078,124,8430.692
 1182.33 2290.06 3508.44 4858.56  7093.511328.72
River Rch & RM=4078,124,8180.916
 1189.53 2306.24 3535.49 4898.85 7152.3211424.01
River Rch & RM=4078,124, 7931.14
 1190.75 2308.94 3539.97 4905.49 7162.0111439.54
River Rch & RM=4078,124,7681.364
 1197.75 2324.58 3566.04 4944.22 7218.5611530.61
River Rch & RM=4078,124, 7437.15
 1199.27 2327.95 3571.63  4952.5 7230.6511549.95
River Rch & RM=4078,124,7159.664
  1200.4 2330.47 3575.82 4958.71 7239.7211564.44
River Rch & RM=4078,124,6815.037
  1214.1 2360.78  3626.1 5033.16 7348.4111737.84
River Rch & RM=4078,124,6144.671
  1216.9 2366.75  3635.8 5047.28 7369.0311769.53
Boundary for River Rch & Prof#=4078,124,1
Up Type= 0
Dn Type= 2
Boundary for River Rch & Prof#=4078,124,2
Up Type= 0
Dn Type= 2
Boundary for River Rch & Prof#=4078,124,2
Up Type= 0
Dn Type= 2
Boundary for River Rch & Prof#=4078,124,2
Up Type= 0
Dn Type= 2
Boundary for River Rch & Prof#=4078,124,2
Up Type= 0
Dn Type= 2
Boundary for River Rch & Prof#=4078,124,2
Up Type= 0
Dn Type= 2

--- 4078_ras.g01 (geometry) ---

Geom Title=4078
Program Version=4.10

River Reach=4078,124
Reach XY= 30
665827.460793167743571.431197882665463.623225063742682.934198871
665692.912182063741724.643003449665320.082320929741072.733281225
 665492.39134869740613.097864553666435.533709794 738787.57703121
666902.981626511738568.393003419667218.085793138737414.313142315
668268.867043138736547.125642329668702.894820929 736553.20203121
669981.106626481734816.309670091671430.585793167733512.663836762
671782.148293167732687.143003419671645.169126481731959.018003434
672009.231626511731937.143003434671824.335793138731225.163836762
672605.585793138731119.434670091672899.335793167730429.330503419
672887.877459854730774.643003434673078.502459824730795.476336747
674454.023293167730335.580503419675200.898293138729853.288836762
675570.038918167  729166.6568923676986.705584854728993.913836762
677518.838564306728519.396749184677662.935786486727624.431471422
676879.949675381726669.570360303676608.682314277 725513.97140196
675296.833355933725393.528693631674645.791689277724396.349874184

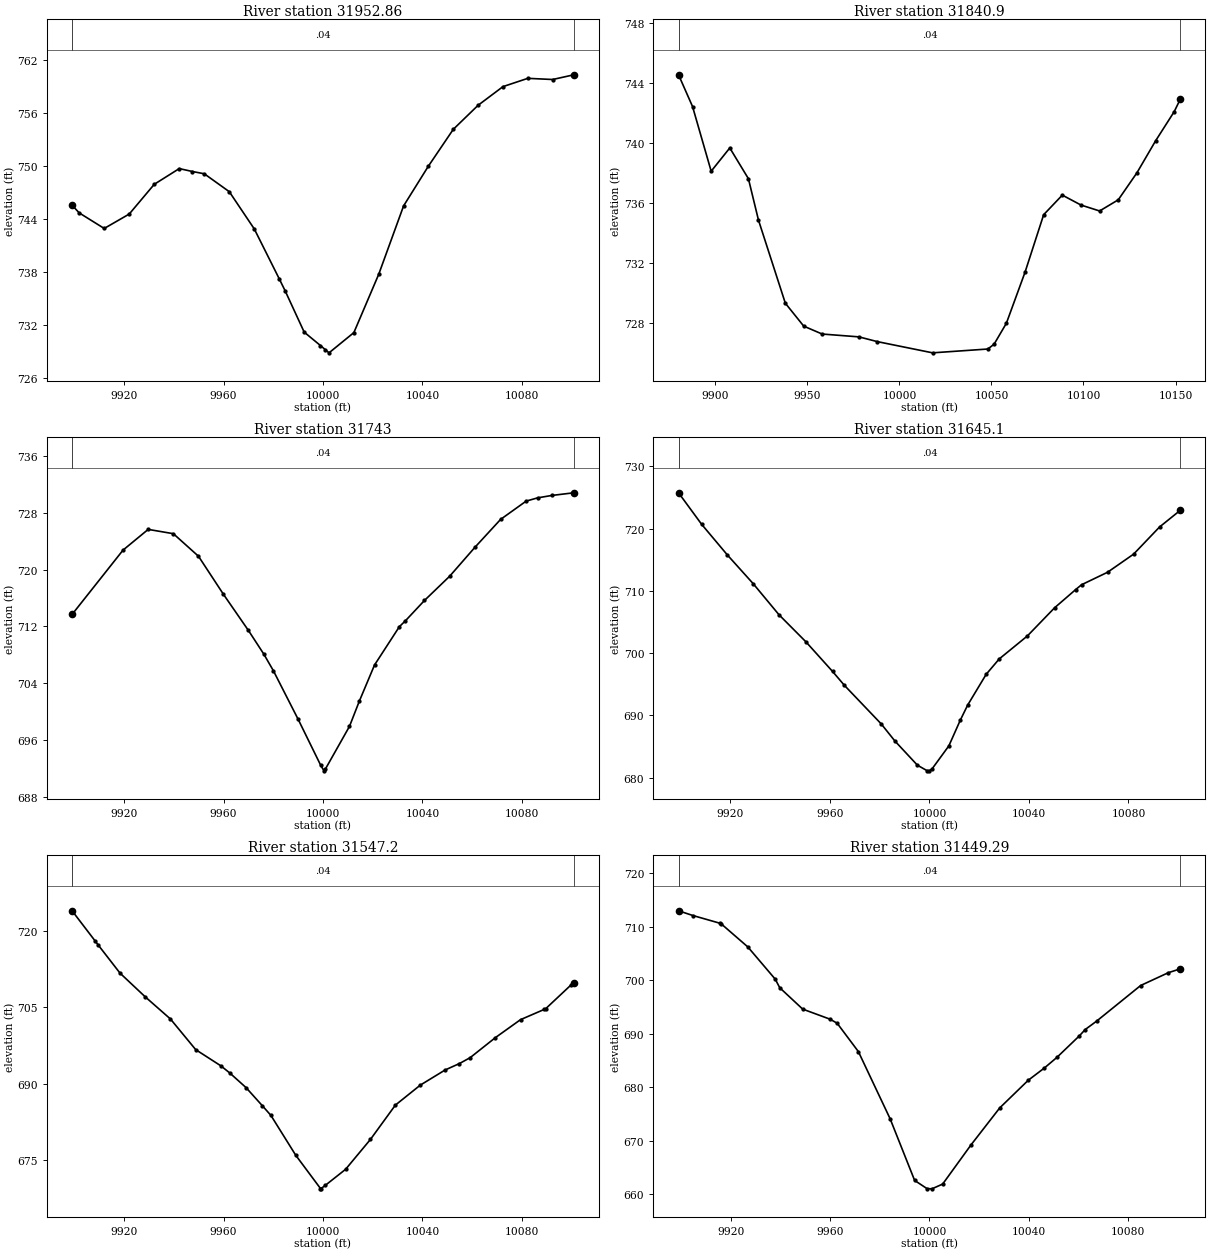
Type RM Length L Ch R = 1 ,31952.86,111.959800,111.959800,111.959800
XS GIS Cut Line= 5
665927.854630015743580.572775296665842.641331471743570.704445885
665828.443405749743570.414107662665826.443702948  743570.4485853
665726.472906496743569.187478623
#Sta/Elev= 26
9899.016745.5589 9901.89744.68589911.957742.92589922.024744.55599932.091 747.919
9942.157749.69829947.459749.36919952.224749.11139962.291747.08649972.358742.8708
9982.425737.21789984.799735.85889992.442731.2008    9999729.6787   10001729.2029
10002.44728.857410012.44731.147710022.45737.748710032.45745.479710042.45749.9839
10052.45 754.13910062.45756.862710072.45758.970510082.45759.906610092.45 759.775
10100.98760.3097
#Mann= 3 , 0 , 0
9899.016    0.04       09899.016    0.04       010100.98    0.04       0
#XS Ineff= 2 , 0
       0                               0
Bank Sta=9899.016,10100.98
Exp/Cntr=0.3,0.1

Type RM Length L Ch R = 1 , 31840.9,97.901700,97.901700,97.901700
XS GIS Cut Line= 4
665962.529220372743470.926275879665919.596658856743464.363940358
665791.585995972743465.647395119665691.721129388743481.934734851
#Sta/Elev= 25
9879.986744.52899887.603742.40849897.719738.09529907.835739.64819917.951737.5967
9923.417734.83519938.015 729.2899948.015727.76049958.016727.23449978.017727.0448
9988.017726.727410018.02725.979810048.02726.234710051.43726.555210058.11727.9538
10068.24731.355510078.37735.1952 10088.5736.501110098.64735.839510108.77735.4431
 10118.9736.187610129.03737.987310139.16740.1181 10149.3742.070910152.62742.9058
#Mann= 3 , 0 , 0
9879.986    0.04       09879.986    0.04       010152.62    0.04       0
#XS Ineff= 2 , 0
       09976.977        10026.59       0
Bank Sta=9879.986,10152.62
Exp/Cntr=0.3,0.1

Type RM Length L Ch R = 1 ,   31743,97.901700,97.901700,97.901700
XS GIS Cut Line= 6
665905.262667263743370.740374481665828.849685924743380.795675622
 665814.03907273743379.932000891665791.107362125743374.350769539
665772.590130165743374.290734983665706.367902327743388.477161938
#Sta/Elev= 27
9899.047713.76769899.313713.79599919.552722.73289929.672725.64859939.791725.0439
9949.903721.86989959.942716.51549969.982711.43249976.156708.11649980.012705.7754
9990.029698.9027    9999 692.50310000.39 691.671   10001691.945710010.65697.9284
10014.63701.493110020.73706.566510030.73711.963210033.14712.778410040.83715.6511
10050.96719.058610061.14723.135910071.44727.052110081.73729.629410086.37730.0891
10092.03730.424610100.92730.8013
#Mann= 3 , 0 , 0
9899.047    0.04       09899.047    0.04       010100.92    0.04       0
#XS Ineff= 2 , 0
       0                               0
Bank Sta=9899.047,10100.92
Exp/Cntr=0.3,0.1

Type RM Length L Ch R = 1 , 31645.1,97.901700,97.901700,97.901700
XS GIS Cut Line= 6
 665873.95041784743256.320057089665810.579702512743276.761815904
665793.707044325743288.056738394665777.339246033743308.615837624
665762.970378726  743319.7881987665697.014050018743343.559550517
#Sta/Elev= 27
9899.138725.77349908.418720.71229918.788715.77599929.157711.16889939.527706.1765
9950.296701.85219961.076 697.0639965.825 694.8369980.634688.63669986.129685.8923
9995.166682.0139    9999681.14019999.924681.1034   10001681.383310007.81685.1125
10012.43689.257410015.39691.676310022.83696.616410028.06699.079410039.36702.7654
10050.32707.295710058.77710.214510061.16710.998210071.62713.005510082.07 715.911
10092.52720.277610100.87722.9633
#Mann= 3 , 0 , 0
9899.138    0.04       09899.138    0.04       010100.87    0.04       0
#XS Ineff= 2 , 0
       0                               0
Bank Sta=9899.138,10100.87
Exp/Cntr=0.3,0.1

Type RM Length L Ch R = 1 , 31547.2,97.901700,97.901700,97.901700
XS GIS Cut Line= 6
665884.020034827743193.187111439665821.527983672743204.045948135
 665785.09492804743206.694779183 665783.09532792 743206.65478718
665729.239933088743209.454200493665683.819870288743216.919366903
#Sta/Elev= 29
9899.042723.93349908.198718.08699909.632 717.1699918.347711.68859928.497707.0325
9938.647702.68179948.797696.67479958.947693.48629962.471692.10529969.016689.2398
9975.628685.65419979.042683.77269989.069675.9303    9999669.41689999.095669.3506
   10001670.056210009.11673.184710019.12679.060510029.13685.781610039.15689.7033
10049.16692.682710054.93693.947810059.22695.096910069.36699.024610079.49702.5578
10089.12704.590210089.63704.712510099.76 709.34510100.96709.7202
#Mann= 3 , 0 , 0
9899.042    0.04       09899.042    0.04       010100.96    0.04       0
#XS Ineff= 2 , 0
       0                               0
Bank Sta=9899.042,10100.96
Exp/Cntr=0.3,0.1

Type RM Length L Ch R = 1 ,31449.29,97.901700,97.901700,97.901700
XS GIS Cut Line= 6
665850.235285386743067.671882772 665796.00683211743093.152669625
665760.623564722743111.958956606665758.763951496743112.695053508
665707.138544366743141.927256343665670.676556905743159.923081163
#Sta/Elev= 27
9899.013713.02069904.797 712.1349915.846710.66869916.244710.55529926.895706.2668
9937.944700.23369939.759698.63169948.993694.6373 9960.07692.74439962.866691.9966
9971.394686.70379984.173674.14859994.044662.6179    9999661.0947   10001661.0447
10005.33661.937810016.82669.308810028.31676.1781 10039.8681.351210046.27683.6316
10051.29685.605210060.33689.630310062.71690.823410067.27692.384810085.02699.0518
10096.17701.448110100.99702.1685
#Mann= 3 , 0 , 0
9899.013    0.04       09899.013    0.04       010100.99    0.04       0
#XS Ineff= 2 , 0
       0                               0
Bank Sta=9899.013,10100.99
Exp/Cntr=0.3,0.1

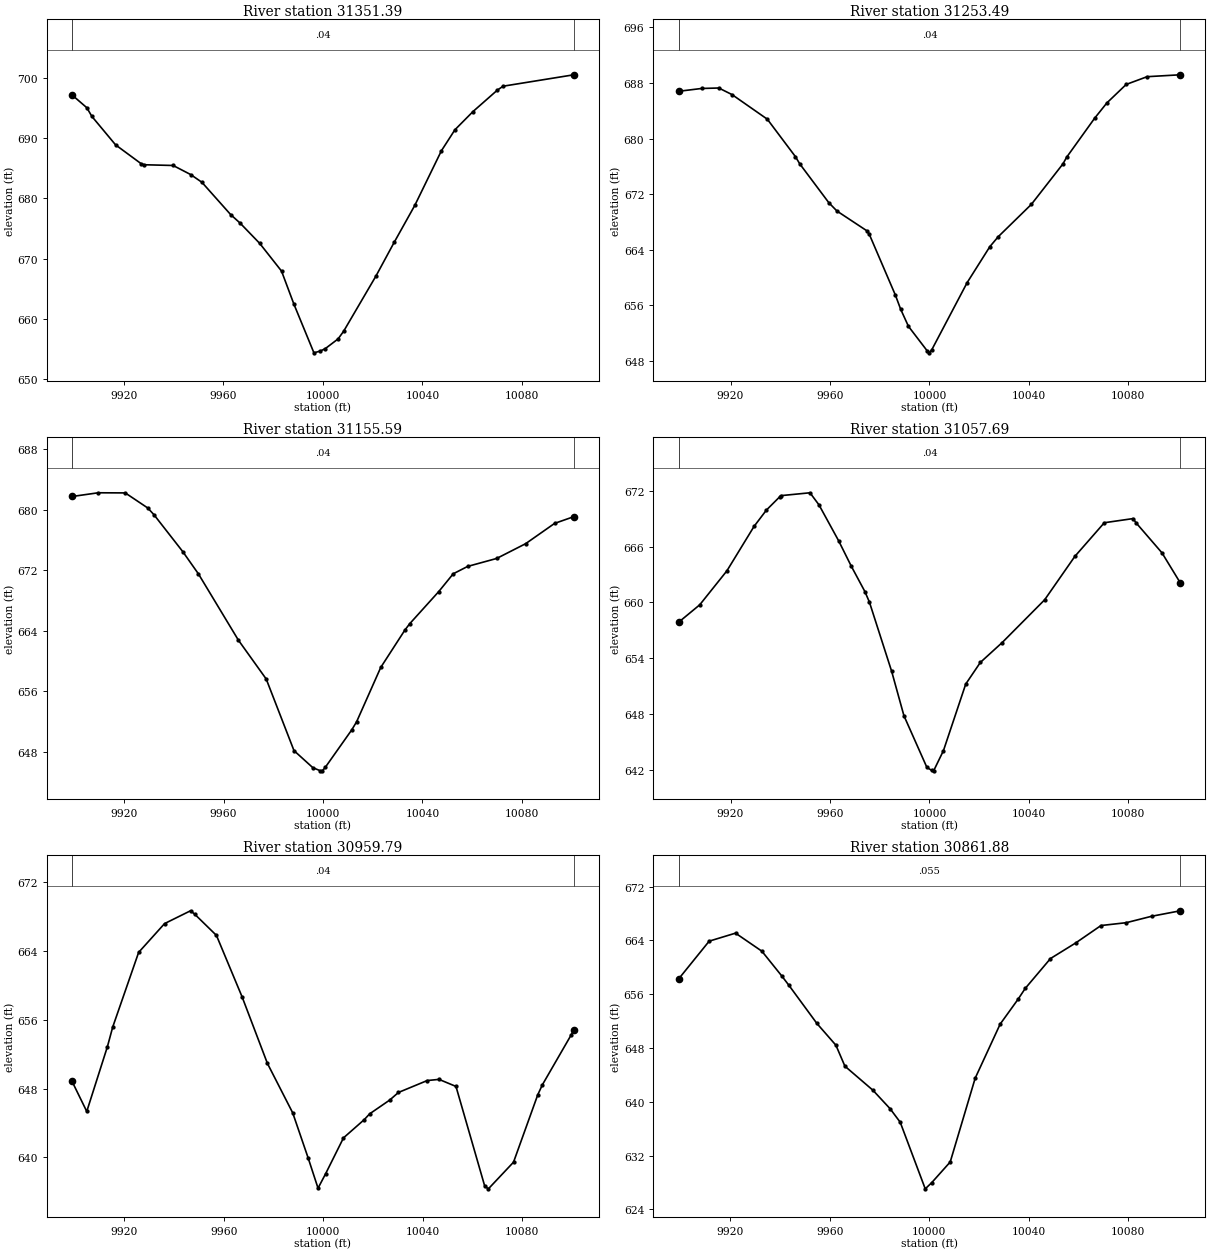
Type RM Length L Ch R = 1 ,31351.39,97.901700,97.901700,97.901700
XS GIS Cut Line= 6
 665780.13225814742980.989138447665715.492577777743018.616486447
665704.814822323743028.370612319 665692.45889345743046.977943129
665679.928526393743059.839617305665621.442536411743102.269372102
#Sta/Elev= 28
9899.091697.17759905.029695.06019907.063693.6187  9916.6688.89329926.941685.7499
9928.171 685.5939939.742685.47239946.818683.96259951.313682.68579962.884677.3212
9966.696 675.9029974.552672.54749983.349667.94019988.347662.43189996.387654.3646
    9999654.6706   10001655.077810006.09656.673110008.32657.937510021.38667.1482
10028.65 672.69810036.97 678.85110047.67687.9165 10053.1691.397310060.39694.4317
 10070.2697.993110072.48698.635110100.95700.5319
#Mann= 3 , 0 , 0
9899.091    0.04       09899.091    0.04       010100.95    0.04       0
#XS Ineff= 2 , 0
       0                               0
Bank Sta=9899.091,10100.95
Exp/Cntr=0.3,0.1

Type RM Length L Ch R = 1 ,31253.49,97.901700,97.901700,97.901700
XS GIS Cut Line= 6
665732.569671109742885.634767248665703.437272592742906.295832609
665682.595816972742924.952710738665653.259566482742968.151081855
 665642.55264092742980.336518044665587.866238312 743023.24522446
#Sta/Elev= 28
9899.072 686.8029908.352 687.2119915.261687.27879920.612686.32419934.787682.7832
9946.111677.37849947.837676.34629959.533 670.7489962.821669.54489974.743666.7233
 9975.75666.24769986.292657.44989988.435655.39459991.563652.9354    9999649.4494
9999.951 649.116   10001649.595410015.19659.245710024.31664.419810027.71665.8617
10041.01670.512310053.73676.352110055.17677.286910066.44682.914210071.37685.1228
10079.15687.790910087.57688.908510100.93689.1837
#Mann= 3 , 0 , 0
9899.072    0.04       09899.072    0.04       010100.93    0.04       0
#XS Ineff= 2 , 0
       0                               0
Bank Sta=9899.072,10100.93
Exp/Cntr=0.3,0.1

Type RM Length L Ch R = 1 ,31155.59,97.901700,97.901700,97.901700
XS GIS Cut Line= 6
665673.523787929742849.720327594665632.931584627742873.243552967
665588.231946237742895.601561923665585.605440605742897.229460563
665584.100287211742898.546469774665498.353736214742949.974004533
#Sta/Elev= 26
9899.015681.76459909.545682.25699920.424682.23879929.489680.24229931.982679.3523
 9943.54674.48449949.857671.5317 9965.98662.74329977.161657.60989988.342 648.133
 9995.91645.8809    9999645.45849999.804645.4797   10001645.950610011.61650.8898
10013.55651.954310023.27659.149710032.99664.093810034.93664.930910046.59669.1758
10052.43671.535110058.25672.512510069.91673.564410081.58 675.51910093.24678.2057
10100.99679.0986
#Mann= 3 , 0 , 0
9899.015    0.04       09899.015    0.04       010100.99    0.04       0
#XS Ineff= 2 , 0
       0                               0
Bank Sta=9899.015,10100.99
Exp/Cntr=0.3,0.1

Type RM Length L Ch R = 1 ,31057.69,97.901700,97.901700,97.901700
XS GIS Cut Line= 6
665632.799709578 742760.70575537665595.599864055742777.136117765
665570.564308642742791.470644847665558.165824188742801.931579262
665524.892435775742838.432032227665468.637114535 742874.05946542
#Sta/Elev= 29
9899.072657.86149907.599659.74289918.531663.39749929.463668.17879934.452669.9374
9939.739671.3482 9940.43671.48739951.953 671.7919955.565670.49429963.477666.6324
9968.588663.88789974.061661.15999975.868 660.032 9984.81652.59199989.757647.8138
    9999642.2534   10001641.9275 10001.7641.889910005.65644.063510014.62651.2236
 10020.5653.548510029.29655.686910046.36660.281310058.53664.954910070.36668.5688
10081.96669.017310083.09668.578510093.57665.331610100.95662.0973
#Mann= 3 , 0 , 0
9899.072    0.04       09899.072    0.04       010100.95    0.04       0
#XS Ineff= 2 , 0
       0                               0
Bank Sta=9899.072,10100.95
Exp/Cntr=0.3,0.1

Type RM Length L Ch R = 1 ,30959.79,97.901700,97.901700,97.901700
XS GIS Cut Line= 6
665620.665541656742700.945089003665559.618616079742719.109768918
665523.990315104742725.936752203 665522.00972715742726.214729461
665506.852638822742729.861224072665434.039648648742772.319109048
#Sta/Elev= 30
9899.031648.83299904.942645.34159913.249652.87029915.376655.14339925.809663.8246
9936.242667.17069946.676668.66019948.313668.27799957.109 665.7989967.426658.6559
9977.608650.9243 9987.79645.17539994.022639.91489997.972636.4244   10001638.0881
10008.21642.269510016.59644.397210018.73645.061410026.79646.661810030.31647.5469
10041.89648.931910046.64649.067410053.46648.248610065.04636.6521 10066.5636.3481
10076.61639.447210086.35647.270210088.19648.423910099.77 654.21810100.88654.8484
#Mann= 3 , 0 , 0
9899.031    0.04       09899.031    0.04       010100.88    0.04       0
#XS Ineff= 2 , 0
       0                10028.59       0
Bank Sta=9899.031,10100.88
Exp/Cntr=0.3,0.1

Type RM Length L Ch R = 1 ,30861.88,97.901700,97.901700,97.901700
XS GIS Cut Line= 6
665556.627793355742640.995658264665519.366296883742654.081067952
665477.196903326742675.844987111665464.389840093742677.312135366
665427.868182194742680.743858923665363.586260747742692.194191072
#Sta/Elev= 25
9899.162658.25629911.486663.89299922.085665.08389932.684662.39879940.658658.7295
9943.568 657.3219954.822  651.659962.463648.41629966.075645.30179977.328641.7304
9984.267638.9707 9988.32636.96819998.386627.0629   10001627.984610008.43631.0562
10018.47643.514310028.52651.558810035.69655.2393 10038.6656.863610048.76661.3069
10058.91663.629410069.07666.215710079.23666.638210089.39667.589210100.98668.4095
#Mann= 3 , 0 , 0
9899.162   0.055       09899.162   0.055       010100.98   0.055       0
#XS Ineff= 2 , 0
       0                               0
Bank Sta=9899.162,10100.98
Exp/Cntr=0.3,0.1

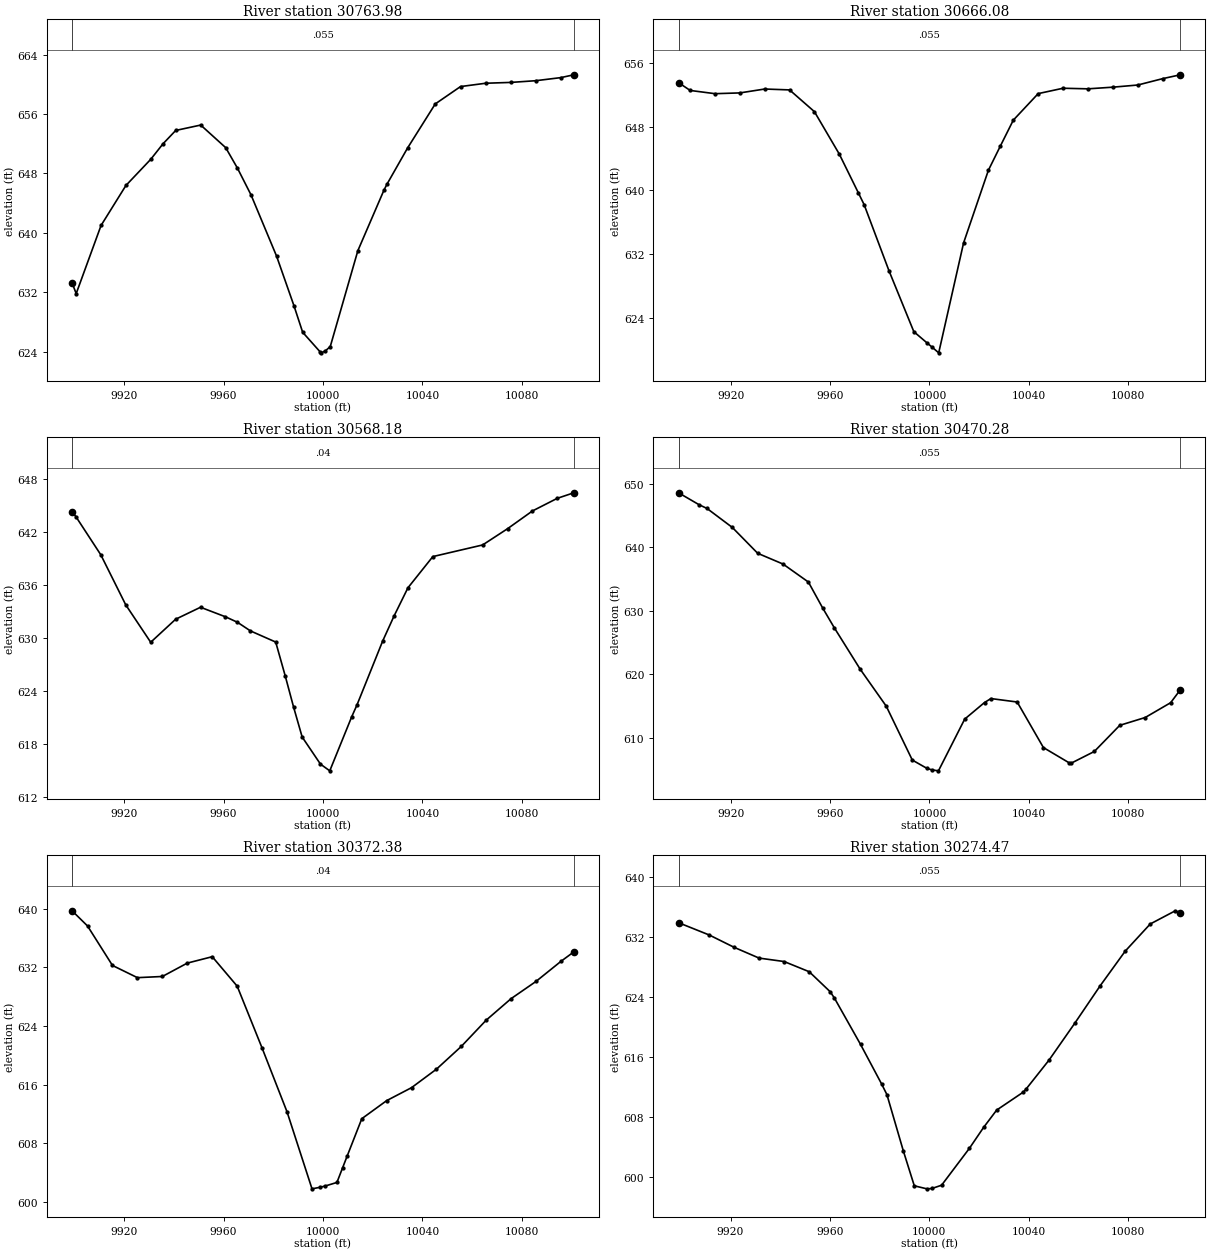
Type RM Length L Ch R = 1 ,30763.98,97.901700,97.901700,97.901700
XS GIS Cut Line= 6
665576.662726282742597.434156867665540.106427477742598.080662416
665510.307805836 742594.87108156 665488.18386163742589.631293664
665445.958298906742572.479339367665379.750708074742563.112843124
#Sta/Elev= 29
9899.075633.26459900.738631.82469910.739641.00069920.741646.38349930.742649.9151
9935.637651.98819940.773653.7963 9950.83654.52259960.888651.47549965.608648.7168
9971.062645.12279981.339 636.8799988.344630.18769991.845626.6146    9999623.9255
9999.399623.8427   10001624.116710002.94624.679510014.05637.602210024.55645.7548
10025.72646.529710034.04 651.42810045.18657.365410055.35659.706510065.51660.1546
10075.57660.265510085.62660.495810095.68660.910810100.95 661.294
#Mann= 3 , 0 , 0
9899.075   0.055       09899.075   0.055       010100.95   0.055       0
#XS Ineff= 2 , 0
       0                               0
Bank Sta=9899.075,10100.95
Exp/Cntr=0.3,0.1

Type RM Length L Ch R = 1 ,30666.08,97.901800,97.901800,97.901800
XS GIS Cut Line= 6
665589.680543707742494.497678974665517.377641041742493.039096469
665489.723226946742493.946060565665487.733152566742494.145068003
665460.156186683 742494.79770586665387.888722908742490.539891139
#Sta/Elev= 26
9899.013653.54939903.695652.56449913.697652.15689923.699652.25439933.701652.7432
9943.703652.63229953.705649.89669963.707644.56889971.331639.7275 9973.71638.2081
9983.715629.8962 9993.72622.2339    9999620.8314   10001620.305910003.73619.5737
10013.74633.392410023.74642.537310028.58645.595710033.75648.827110043.77652.1648
10053.78652.8415 10063.8652.766810073.82 652.97510083.84653.245810093.85 654.046
10100.98654.5339
#Mann= 3 , 0 , 0
9899.013   0.055       09899.013   0.055       010100.98   0.055       0
#XS Ineff= 2 , 0
       0                               0
Bank Sta=9899.013,10100.98
Exp/Cntr=0.3,0.1

Type RM Length L Ch R = 1 ,30568.18,97.901700,97.901700,97.901700
XS GIS Cut Line= 6
 665596.50831719742394.025084705665530.146062223742390.253826496
665511.221314503742393.634291648 665486.95876188742405.039765701
665470.590312062742409.308260013665398.333809344742409.198914641
#Sta/Elev= 27
 9899.09644.27129900.604643.74479910.643639.41999920.682633.75699930.721629.5256
9940.756632.13169950.757 633.4859960.757632.41049965.611631.78679970.838630.8095
9980.997 629.5499984.835625.71429988.216 622.1689991.636618.8117    9999615.7436
10002.74614.984410011.57621.100610013.69 622.43810024.02629.663910028.58632.4852
10034.18635.6845 10044.2639.215810064.23640.530210074.23642.364710084.24 644.372
10094.25645.804910100.92646.4319
#Mann= 3 , 0 , 0
 9899.09    0.04       0 9899.09    0.04       010100.92    0.04       0
#XS Ineff= 2 , 0
       0                               0
Bank Sta=9899.09,10100.92
Exp/Cntr=0.3,0.1

Type RM Length L Ch R = 1 ,30470.28,97.901700,97.901700,97.901700
XS GIS Cut Line= 6
665616.237243743742336.614317276665561.911440081742325.760453113
665519.373118145742312.475620453665517.486742068742311.811101606
 665475.33102419742297.487188594665421.208289313742285.495279162
#Sta/Elev= 27
9899.036648.60819907.276646.73289910.495646.13949920.693643.14379930.891639.0764
9941.088637.38369951.286 634.5519956.986630.49759961.676627.37269972.152620.8127
9982.629614.99429993.105606.5115    9999605.2036   10001604.964310003.63604.8144
10014.19612.961310022.17615.575610024.75616.197910035.31615.654410045.86608.4811
 10056.1606.105310057.02606.015110066.35607.863310076.59611.981610086.83613.2145
10097.07615.546910100.96617.5818
#Mann= 3 , 0 , 0
9899.036   0.055       09899.036   0.055       010100.96   0.055       0
#XS Ineff= 2 , 0
       0                10025.48       0
Bank Sta=9899.036,10100.96
Exp/Cntr=0.3,0.1

Type RM Length L Ch R = 1 ,30372.38,97.901700,97.901700,97.901700
XS GIS Cut Line= 5
665631.199958089742224.543357323665531.599749828742215.632419221
665529.604980236742215.487870699665520.807593989742214.860214466
665429.750107323742210.251511926
#Sta/Elev= 26
9899.002639.71779905.227 637.6469915.267632.26349925.307630.59949935.347630.7601
9945.386632.58529955.426633.45669965.466629.44029975.506 620.9949985.546612.2956
9995.586601.8078    9999602.0318   10001602.202810005.62602.681210007.86604.6399
10009.82606.346310015.63611.371510025.65613.836710035.66615.603910045.67618.1209
10055.69621.2292 10065.7624.804210075.71627.733910085.72630.077610095.74632.8091
10100.99634.1182
#Mann= 3 , 0 , 0
9899.002    0.04       09899.002    0.04       010100.99    0.04       0
#XS Ineff= 2 , 0
       0                               0
Bank Sta=9899.002,10100.99
Exp/Cntr=0.3,0.1

Type RM Length L Ch R = 1 ,30274.47,97.901700,97.901700,97.901700
XS GIS Cut Line= 6
665627.376238008742101.208978441665596.385273799742100.926250931
665566.653989067 742104.99388479665546.893455103742111.342267075
665492.097995131742135.661539879665433.002143693742146.109786801
#Sta/Elev= 28
 9899.08633.87299911.457632.23319921.457630.59499931.471629.16459941.564628.7054
9951.657 627.3489960.101624.68389961.818623.83029972.321617.66779980.836612.3782
9982.921610.9905 9989.57603.45369993.933598.8631    9999598.4601   10001598.5056
10004.91598.941310016.12603.858210021.79606.622910027.07608.938110037.76 611.325
10038.98611.767910048.15615.595110058.43620.4641 10068.7625.471710078.78630.0853
10088.86633.701410098.94635.458410100.96635.1935
#Mann= 3 , 0 , 0
 9899.08   0.055       0 9899.08   0.055       010100.96   0.055       0
#XS Ineff= 2 , 0
       0                               0
Bank Sta=9899.08,10100.96
Exp/Cntr=0.3,0.1

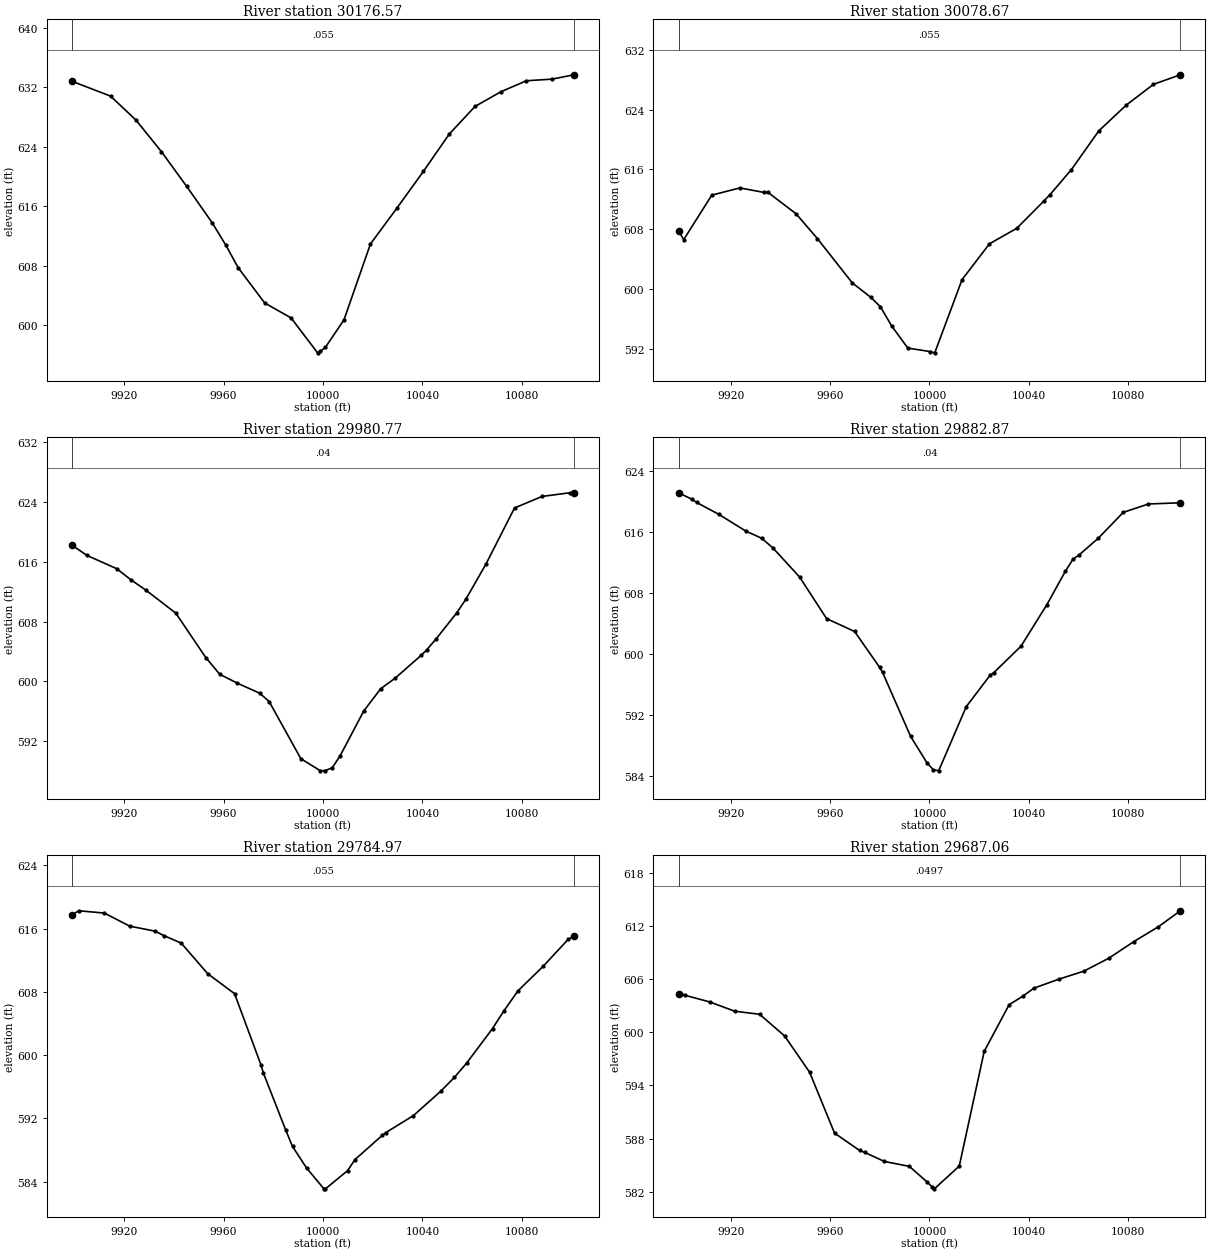
Type RM Length L Ch R = 1 ,30176.57,97.901700,97.901700,97.901700
XS GIS Cut Line= 6
665610.128849243742058.245554608665551.992640943742045.800810622
665513.901576129742032.016737291665512.019186788742031.341007784
665471.328592927742016.538806846665416.540410624742002.041211532
#Sta/Elev= 23
9899.038632.8047 9914.51 630.8159924.736627.59379934.963623.3553 9945.19618.6517
9955.416613.77629960.845610.79369965.928 607.6999976.563 602.9739987.197600.9558
9997.832596.2655    9999 596.484   10001597.013110008.47600.714710019.11610.9152
10029.75615.735810040.39620.671110050.85625.715110061.19629.418910071.53631.3886
10081.88632.880610092.22633.098610100.97633.6838
#Mann= 3 , 0 , 0
9899.038   0.055       09899.038   0.055       010100.97   0.055       0
#XS Ineff= 2 , 0
       0                               0
Bank Sta=9899.038,10100.97
Exp/Cntr=0.3,0.1

Type RM Length L Ch R = 1 ,30078.67,97.901700,97.901700,97.901700
XS GIS Cut Line= 5
665646.826579392741991.105161442665570.964469767741951.050325906
665557.915546124741945.460348493665556.028132963741944.798780993
 665465.17543762741903.112618849
#Sta/Elev= 25
9899.017607.78989901.082606.58899912.391612.55399923.699613.5252 9933.51 612.914
9935.007612.92769946.316610.05779954.928606.72179968.932600.80079976.345598.8753
9980.241597.60449984.804595.01999991.293592.060810000.39591.587310002.13591.4236
10013.13601.239910024.14606.032510035.14608.111110046.14611.796110048.48 612.611
10057.14615.985410068.15621.171110079.15624.609110090.15627.402810100.96628.6847
#Mann= 3 , 0 , 0
9899.017   0.055       09899.017   0.055       010100.96   0.055       0
#XS Ineff= 2 , 0
       0                               0
Bank Sta=9899.017,10100.96
Exp/Cntr=0.3,0.1

Type RM Length L Ch R = 1 ,29980.77,97.901700,97.901700,97.901700
XS GIS Cut Line= 6
665700.062712842741927.842477189665656.865708434 741899.95004973
665618.796422592741869.826400612665581.998034356741841.296857536
665558.875641353741826.961221656665533.541073366741814.593512414
#Sta/Elev= 29
9899.035618.21459905.061616.84449916.964615.0813 9922.71613.59059928.868612.1688
9940.771609.12389952.833603.18499958.431600.94399965.585599.73989974.547598.4034
9978.337597.29359991.089589.6421    9999588.0128   10001588.057510003.77588.4307
10006.93590.046810016.44596.036310023.23599.0069 10029.1600.429610039.53603.4807
10041.76604.214610045.56605.6917 10053.8609.147710057.51610.988210065.56615.6762
10077.08623.203310088.21624.751710099.34 625.23710100.96625.1828
#Mann= 3 , 0 , 0
9899.035    0.04       09899.035    0.04       010100.96    0.04       0
#XS Ineff= 2 , 0
       0                               0
Bank Sta=9899.035,10100.96
Exp/Cntr=0.3,0.1

Type RM Length L Ch R = 1 ,29882.87,97.901700,97.901700,97.901700
XS GIS Cut Line= 6
665759.972015838741827.782714517665706.815497538741805.771143738
665667.416186611741785.225966494665637.297489602741770.659649176
665612.511934853741763.428535086665572.328066647 741757.30273041
#Sta/Elev= 28
9899.029621.16559904.411620.31529906.303619.89699915.234618.33869926.058616.1474
9932.441615.20399936.881613.96959947.705610.12949958.608604.65719969.873602.9691
9979.962598.25389981.137597.59099992.402589.2135    9999585.729310001.52584.8472
10003.68584.691310014.79593.112710024.49597.2726 10025.9597.577110036.85601.0541
10047.27606.510410054.66610.867310057.68612.431810060.27613.033210067.87615.1914
10077.99618.6015 10088.1619.694610100.92 619.854
#Mann= 3 , 0 , 0
9899.029    0.04       09899.029    0.04       010100.92    0.04       0
#XS Ineff= 2 , 0
       0                               0
Bank Sta=9899.029,10100.92
Exp/Cntr=0.3,0.1

Type RM Length L Ch R = 1 ,29784.97,97.901700,97.901700,97.901700
XS GIS Cut Line= 6
665767.749323616741662.321433175665731.475258258741669.529554076
665706.383955669741678.858798483665656.205606376741713.365883304
665636.801044249741723.008597195 665582.74485295741734.471402375
#Sta/Elev= 30
9899.091617.76449901.894618.2453 9912.09617.95239922.285616.30279932.481615.6691
9936.074615.09889942.983614.16189953.652610.28959964.441607.76979975.148598.6993
9975.982597.78899984.936590.59929987.745588.46369993.414585.735910000.36583.1168
   10001583.106510009.88585.402410012.88586.808710023.86589.8692 10025.2 590.199
10036.37592.3613 10047.4595.453310052.83597.181210057.79599.003510068.19603.3668
10072.71605.570210078.42608.127310088.52611.216810098.63614.6403 10100.9615.0122
#Mann= 3 , 0 , 0
9899.091   0.055       09899.091   0.055       0 10100.9   0.055       0
#XS Ineff= 2 , 0
       0                               0
Bank Sta=9899.091,10100.9
Exp/Cntr=0.3,0.1

Type RM Length L Ch R = 1 ,29687.06,97.901700,97.901700,97.901700
XS GIS Cut Line= 6
665727.452474298741614.884595836665653.016076729 741622.45093103
665627.940074813741620.959712463665625.971820778741620.604781408
665589.572136606741617.953837475665526.225383372741621.257915174
#Sta/Elev= 27
 9899.06604.35779900.201604.29349901.525604.17369911.576603.41549921.628602.3692
9931.679602.01919941.731599.57989951.782595.48869961.834588.60839971.886586.6633
 9973.88586.4444 9981.91585.41629991.928584.8635    9999583.1147   10001582.5754
10001.97  582.33   10012584.894610022.03597.837910032.05603.0966 10037.5 604.052
10042.07604.970310052.09605.9843 10062.1606.882310072.12608.335910082.13610.2007
10092.14611.901810100.93 613.696
#Mann= 3 , 0 , 0
 9899.06  0.0497       0 9899.06  0.0497       010100.93  0.0497       0
#XS Ineff= 2 , 0
       0                               0
Bank Sta=9899.06,10100.93
Exp/Cntr=0.3,0.1