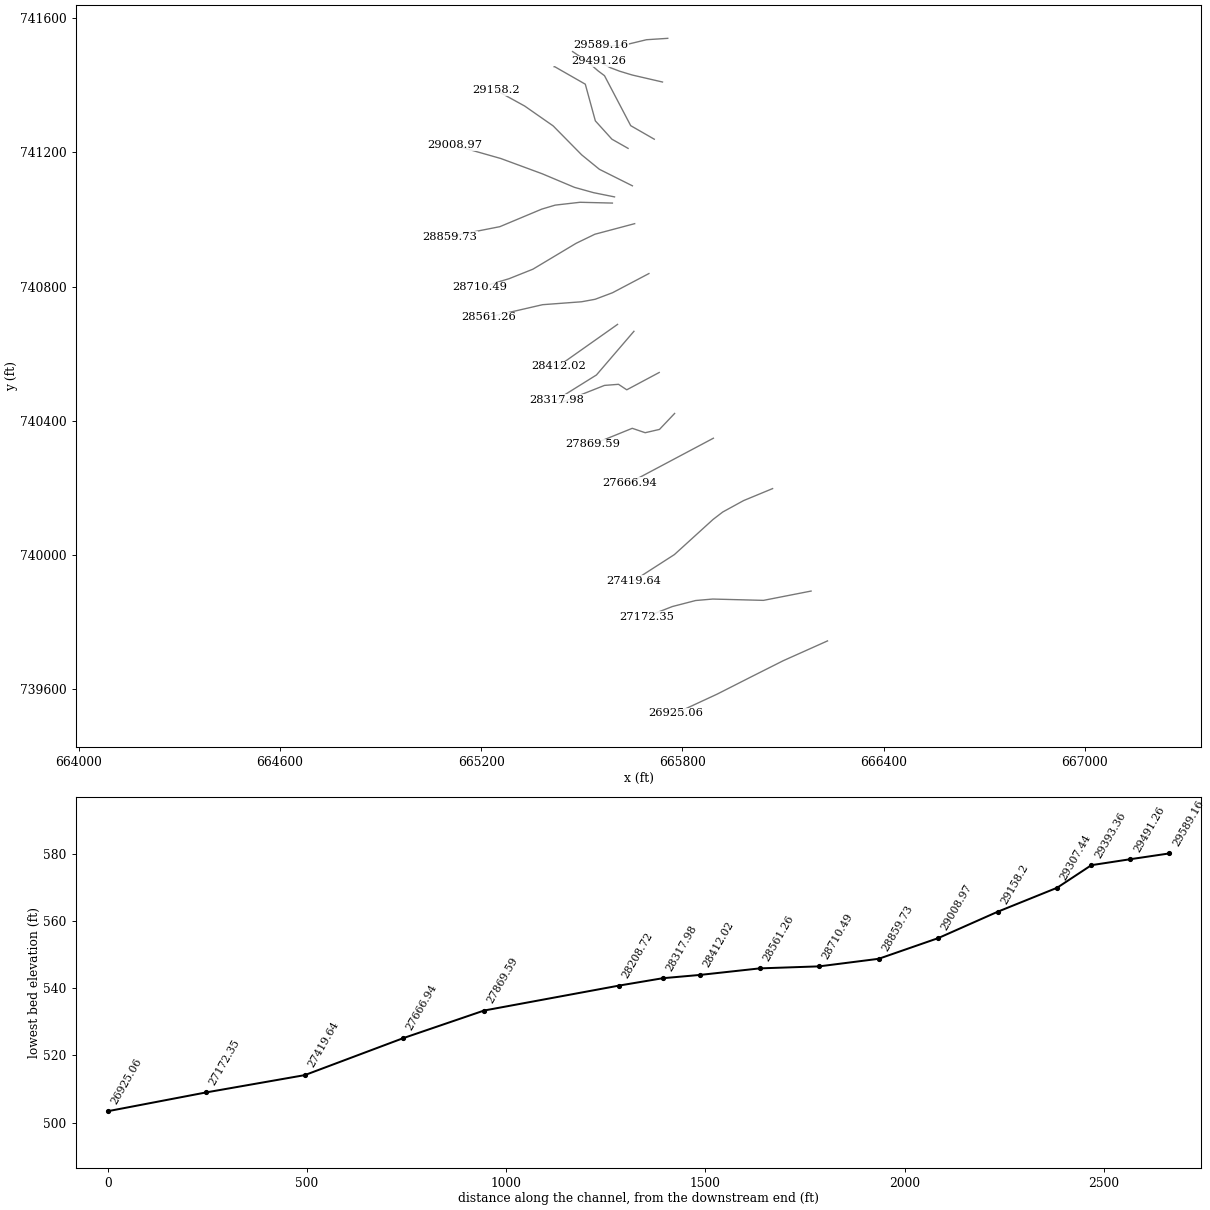
HEC-RAS study 4078_ras.prj: 4078

--- 4078_ras.g01 (geometry) --- (continued)

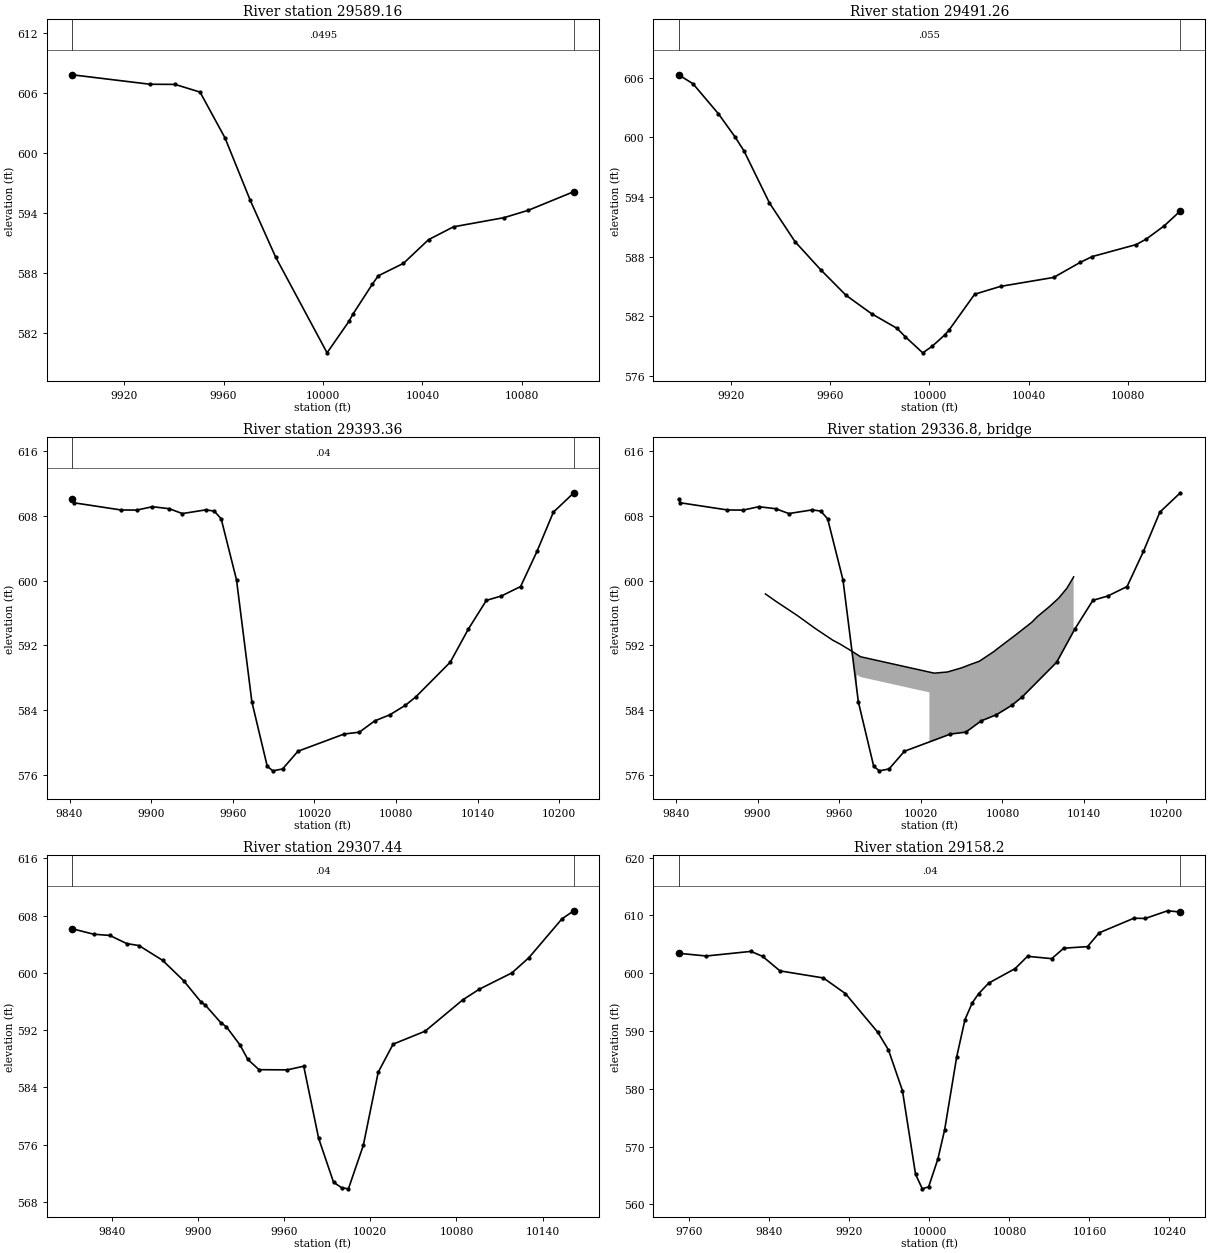
Type RM Length L Ch R = 1 ,29589.16,97.901700,97.901700,97.901700
XS GIS Cut Line= 6
 665756.38465723741540.142188089665693.096032915741536.024842075
665637.332207571741522.601298931665611.963667879741518.747825457
665584.779466237 741517.78089512665556.686639737741520.094630822
#Sta/Elev= 18
9899.025607.82469930.426 606.8789940.459606.86399950.519 606.0949960.579601.5109
9970.741595.27339980.927589.622810001.63580.051310010.48583.211710011.97583.8882
 10019.9586.927710022.25587.747410032.37588.989710042.48591.357610052.52592.6392
10072.76593.549710082.57594.285410100.94596.1529
#Mann= 3 , 0 , 0
9899.025  0.0495       09899.025  0.0495       010100.94  0.0495       0
#XS Ineff= 2 , 0
       0                               0
Bank Sta=9899.025,10100.94
Exp/Cntr=0.3,0.1

Type RM Length L Ch R = 1 ,29491.26,97.901700,97.901700,97.901700
XS GIS Cut Line= 6
665740.671555405741409.888540848665651.835137149741430.423839249
665643.365533007741432.873468064665612.370790324741442.295474055
665585.432938488741452.558198633665549.254472882 741471.29680776
#Sta/Elev= 25
9899.004606.29559904.825605.39339915.089602.3644  9921.7600.06169925.353598.6373
9935.616593.3966 9945.88589.51619956.144586.70719966.408 584.1189976.671 582.268
9986.935580.79699990.183579.96929997.299578.3291   10001578.970710006.06580.1077
10007.77580.585110018.21584.228110028.65 585.01510049.99585.913810060.71587.4309
10065.53588.012710083.24589.219910087.28589.7749 10094.5591.106310100.97592.6006
#Mann= 3 , 0 , 0
9899.004   0.055       09899.004   0.055       010100.97   0.055       0
#XS Ineff= 2 , 0
       0                               0
Bank Sta=9899.004,10100.97
Exp/Cntr=0.3,0.1

Type RM Length L Ch R = 1 ,29393.36,85.917700,85.917700,85.917700
XS GIS Cut Line= 6
665716.208023876741239.369009018665645.895523846741279.733592331
665567.722436935741428.769360244665548.164352387  741443.4379237
665516.714359462741471.039068475665472.503363013 741500.72244589
#Sta/Elev= 30
9841.855610.00279843.248609.5849 9877.84608.70119889.371608.68539900.902609.1042
9913.423608.8511 9922.93 608.257 9940.17608.71439946.387608.56139951.462 607.617
9962.754 600.0879974.046585.05989985.338577.11649989.443576.5501 9996.63576.7816
10007.92578.9646 10041.8581.083710053.09581.317510064.38582.707510075.56583.4634
10086.97584.635910094.63585.674710119.88589.9384 10133.2594.023210146.49597.5634
10157.52598.100710171.63599.266710183.67603.599710195.72608.431610210.77610.8198
#Mann= 3 , 0 , 0
9841.855    0.04       09841.855    0.04       010210.77    0.04       0
#XS Ineff= 2 , 0
       0                               0
Bank Sta=9841.855,10210.77
Exp/Cntr=0.3,0.1

Type RM Length L Ch R = 3 , 29336.8,,,
BEGIN DESCRIPTION:
END DESCRIPTION:
Bridge Culvert--1,0,-1,-1, 0
Deck Dist Width WeirC Skew NumUp NumDn MinLoCord MaxHiCord MaxSubmerge Is_Ogee
32.493850,20.930000,2.6,0, 34, 34, , , 0.95, 0, 0,0,,
 9905.73 9913.48 9915.34 9928.04 9929.10 9942.60 9942.86 9955.36 9956.30 9960.47
 9965.15 9966.62 9973.07 9973.07 9975.6910026.3110026.3110029.9710033.1310039.48
10049.3210050.0310058.0410062.9310073.8710075.8310088.7310089.6910101.6310105.52
10114.5310121.3510127.4410132.35
  598.35  597.44  597.23  595.82  595.70  594.07  594.04  592.64  592.56  592.19
  591.71  591.57  590.89  590.89  590.61  588.72  588.72  588.59  588.64  588.73
  589.21  589.25  589.76  590.05  591.27  591.54  593.18  593.30  594.87  595.54
  596.79  597.84  599.07  600.46
 -401.65 -402.56 -402.77 -404.18 -404.30 -405.93 -405.96 -407.36 -407.44 -407.81
 -408.29 -408.43 -409.11  588.39  588.11  586.22 -411.28 -411.41 -411.36 -411.27
 -410.79 -410.75 -410.24 -409.95 -408.73 -408.46 -406.82 -406.70 -405.13 -404.46
 -403.21 -402.16 -400.93 -399.54
 9905.73 9913.48 9915.34 9928.04 9929.10 9942.60 9942.86 9955.36 9956.30 9960.47
 9965.15 9966.62 9973.38 9973.38 9975.6910026.6210026.6210029.9710033.1310039.48
10049.3210050.0310058.0410062.9310073.8710075.8310088.7310089.6910101.6310105.52
10114.5310121.3510127.4410132.35
  598.35  597.44  597.23  595.82  595.70  594.07  594.04  592.64  592.56  592.19
  591.71  591.57  590.85  590.85  590.61  588.71  588.71  588.59  588.64  588.73
  589.21  589.25  589.76  590.05  591.27  591.54  593.18  593.30  594.87  595.54
  596.79  597.84  599.07  600.46
 -401.65 -402.56 -402.77 -404.18 -404.30 -405.93 -405.96 -407.36 -407.44 -407.81
 -408.29 -408.43 -409.15  588.35  588.11  586.21 -411.29 -411.41 -411.36 -411.27
 -410.79 -410.75 -410.24 -409.95 -408.73 -408.46 -406.82 -406.70 -405.13 -404.46
 -403.21 -402.16 -400.93 -399.54
BR Coef=-1 , 0 , 0 ,, 0 ,,,0.8,0,1,0,
WSPro=,,,, 1 ,,,, 0 ,,,, 0 ,,,,-1 ,-1 ,-1 , 0 , 0 , 0 , 0 , 0
BC Design=,, 0 ,, 0 ,,,,,,

Type RM Length L Ch R = 1 ,29307.44,149.236600,149.236600,149.236600
XS GIS Cut Line= 6
665638.083023876741212.025259003665589.905940562741239.369009018
665540.426773846741294.056509018665510.478857219741403.431509018
665419.333023876741455.514842346 665417.62957418 741455.46571283
#Sta/Elev= 30
9812.493606.16169827.536605.39499838.778605.22329850.533604.08689859.037603.8102
9875.482601.74969890.106598.91199902.453595.87459905.011595.54959915.939593.0551
9919.916592.45989929.424 589.9099934.821587.90599942.616586.47569962.187586.4495
 9973.72586.96129984.088576.89539994.456570.765610000.05569.994610004.82569.8363
10015.19575.907810025.56 586.12610035.93590.0402 10058.2591.852610084.38 596.226
 10095.9597.714910118.67600.001610130.45602.122110153.49607.551510161.72608.6671
#Mann= 3 , 0 , 0
9812.493    0.04       09812.493    0.04       010161.72    0.04       0
#XS Ineff= 2 , 0
       0                               0
Bank Sta=9812.493,10161.72
Exp/Cntr=0.3,0.1

Type RM Length L Ch R = 1 , 29158.2,149.236600,149.236600,149.236600
XS GIS Cut Line= 6
665650.946675949741100.393777145665552.491986075 741149.62853008
665499.875269681 741192.52801328 665414.61413308741279.064667567
665329.810970033741338.209953823665243.677848996741385.653533346
#Sta/Elev= 30
9749.074603.44549776.854602.97589821.438603.77379833.136 602.9149850.544600.4002
9893.951599.17899916.001596.47169948.527589.74859959.043 586.7169973.005579.6994
9986.113565.22159992.895562.69559999.212563.0469 10008.4567.819610015.19572.8823
10027.35585.586110035.55591.967710042.85594.870710049.15596.441110059.25598.2847
10085.74600.7988 10098.1602.922410122.34602.517310134.34604.326710158.14604.6001
10169.75606.986610204.56609.517110215.78609.467910238.23610.799410250.94610.5875
#Mann= 3 , 0 , 0
9749.074    0.04       09749.074    0.04       010250.94    0.04       0
#XS Ineff= 2 , 0
       0                               0
Bank Sta=9749.074,10250.94
Exp/Cntr=0.3,0.1

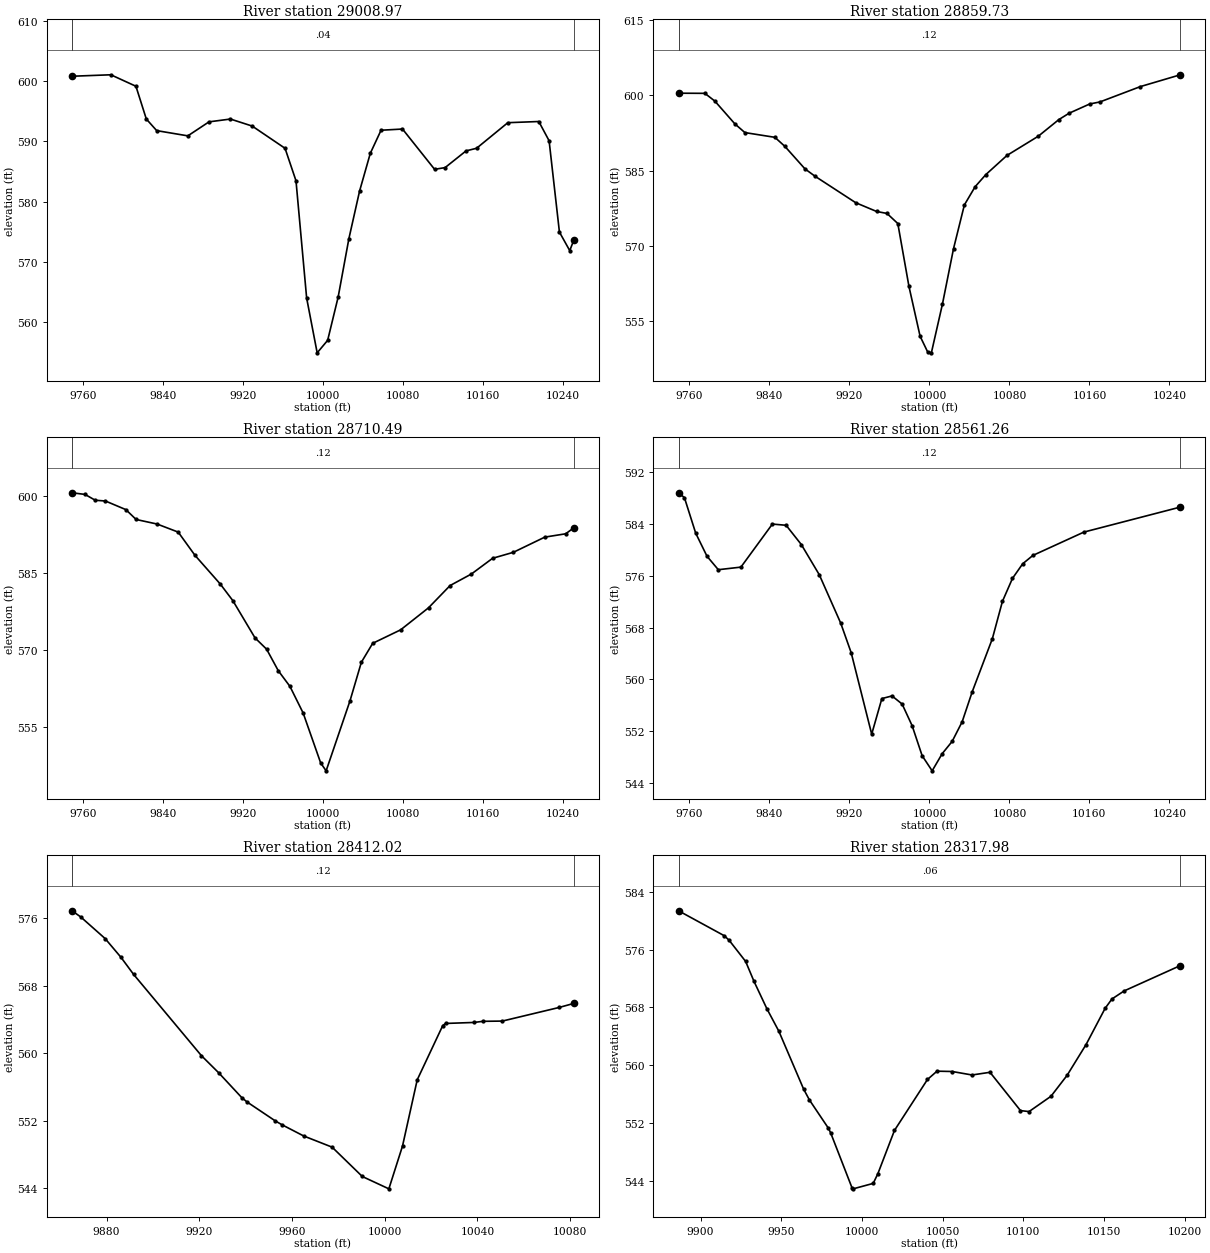
Type RM Length L Ch R = 1 ,29008.97,149.236600,149.236600,149.236600
XS GIS Cut Line= 6
665597.618415031741067.334591544665535.102950304741079.943419693
665478.260726654 741095.78399076665382.162767546 741136.21965385
665258.601306673741181.784342346665121.012292559741220.825814485
#Sta/Elev= 30
 9749.06600.83499787.831601.07829812.941599.16999823.322593.72449833.703591.7937
9864.847590.92449886.036593.25279907.443593.71939929.234 592.5519962.082588.8547
9973.032583.45879983.683563.96659994.216 554.852 10004.7556.9325 10015.2564.1261
10025.92573.821110036.65581.760410047.38588.029310058.11591.859610079.56592.0582
10111.66585.359410122.16585.645610143.15588.427910153.65588.860110184.91593.1138
10215.88593.3094 10226.2590.109710236.52574.929310246.85571.844210250.96573.6155
#Mann= 3 , 0 , 0
 9749.06    0.04       0 9749.06    0.04       010250.96    0.04       0
#XS Ineff= 2 , 0
       0                               0
Bank Sta=9749.06,10250.96
Exp/Cntr=0.3,0.1

Type RM Length L Ch R = 1 ,28859.73,149.236600,149.236600,149.236600
XS GIS Cut Line= 6
665591.302649144741048.921333487665494.776552909 741051.28390792
665420.668723068741042.804364401665380.466423696741030.817380799
665255.720187174740978.564768426665105.630185397740949.054720752
#Sta/Elev= 30
9749.138600.41849775.473600.38879785.485 598.8399805.497594.30289815.497592.5741
9845.497591.62929855.522589.82079875.572585.34539885.615583.88059926.298578.6086
9947.168576.86389957.603576.46799968.421574.45849979.557561.93129990.692552.0155
 9998.29548.871110001.97 548.70710013.05558.424810024.13569.462210034.97578.1639
10045.71581.789210056.44584.208910077.57588.024810108.87591.848410129.42595.1588
 10139.7596.427510160.26598.265910170.54598.676310211.05601.739110250.92604.0859
#Mann= 3 , 0 , 0
9749.138    0.12       09749.138    0.12       010250.92    0.12       0
#XS Ineff= 2 , 0
       0                               0
Bank Sta=9749.138,10250.92
Exp/Cntr=0.3,0.1

Type RM Length L Ch R = 1 ,28710.49,149.236600,149.236600,149.236600
XS GIS Cut Line= 6
665657.674020612740987.533614307665539.043574693740955.992682553
665483.416417302740929.113061021665354.344635019 740851.81657452
665283.149320134 740823.40484497 665197.14744561740797.628342497
#Sta/Elev= 30
9749.117600.62859762.062600.30919772.276599.1748 9782.49599.02499802.917597.3459
9813.174595.42689834.196594.53639855.263592.96469872.071588.43289897.337582.8481
9909.881579.61929932.093572.35079943.673570.15679955.342565.96229967.011562.9044
9980.211557.71799997.749547.988510003.19 546.45710027.09560.117910038.42567.6099
10049.75571.300410077.69573.925310105.57578.216610127.17582.558110148.51584.8082
10169.66587.864810190.42589.030610221.85591.988510242.73592.637410250.93593.8054
#Mann= 3 , 0 , 0
9749.117    0.12       09749.117    0.12       010250.93    0.12       0
#XS Ineff= 2 , 0
       0                               0
Bank Sta=9749.117,10250.93
Exp/Cntr=0.3,0.1

Type RM Length L Ch R = 1 ,28561.26,149.236600,149.236600,149.236600
XS GIS Cut Line= 6
665700.194481437740838.755361155665591.559065509 740781.51116875
665539.770920394740762.038399998665499.147109316 740754.59778575
665383.177563228740745.919423974665221.419536818740708.674214492
#Sta/Elev= 30
9749.087588.84449754.958588.10189766.262582.59889777.565579.03089788.869576.9518
9811.475577.35169842.947584.00719856.689 583.8199871.882580.84399889.837576.1799
 9911.27568.7027 9921.77564.11529942.278551.52689952.444557.0274 9962.61557.4382
9972.714556.17999982.727552.83239992.741548.194610002.75545.856210012.76548.5042
10022.77550.411210032.77 553.44510042.81558.074210062.96566.285210073.03572.0533
 10083.1575.613610093.28 577.86510103.49579.159910154.54582.768110250.96586.6353
#Mann= 3 , 0 , 0
9749.087    0.12       09749.087    0.12       010250.96    0.12       0
#XS Ineff= 2 , 0
       0                               0
Bank Sta=9749.087,10250.96
Exp/Cntr=0.3,0.1

Type RM Length L Ch R = 1 ,28412.02,94.042300,94.042300,94.042300
XS GIS Cut Line= 2
665606.657826781740687.173925757665429.791507334740562.390939638
#Sta/Elev= 24
9865.126 576.9119868.897576.17149879.393573.61179886.243571.38099891.631569.3755
9920.936559.71539928.346557.69449938.283554.75379940.585554.22929952.823 551.971
9955.629551.52779965.061550.1872  9977.3548.86289990.322545.381610001.78543.9166
10007.67548.999310014.01556.851410025.02563.287810026.25563.541710038.49563.6605
10042.36563.794110050.73563.823710075.21565.437810081.58565.9211
#Mann= 3 , 0 , 0
9865.126    0.12       09865.126    0.12       010081.58    0.12       0
#XS Ineff= 2 , 0
       0                10056.56       0
Bank Sta=9865.126,10081.58
Exp/Cntr=0.3,0.1

Type RM Length L Ch R = 1 ,28317.98,109.256100,109.256100,109.256100
XS GIS Cut Line= 3
665655.485951751 740666.55760631 665543.72379896740536.349272981
665425.451229542740462.564550743
#Sta/Elev= 30
9886.356581.36859914.766577.9122 9917.81577.26659927.945574.36699933.163571.5935
9941.123567.82399948.517 564.726 9963.87556.7237 9967.48555.21669979.224 551.317
9980.659550.65999993.837543.09379994.578542.931910007.02543.684510009.93545.0425
10020.19551.009510040.64558.049410046.55559.197910055.99559.151410068.23558.6695
10079.39559.042110098.29553.747410103.59553.611310117.18555.726810127.17558.6202
10138.95562.883610150.74567.883810154.97569.175310162.53570.289510197.35573.7933
#Mann= 3 , 0 , 0
9886.356    0.06       09886.356    0.06       010197.35    0.06       0
#XS Ineff= 2 , 0
       0                10052.83       0
Bank Sta=9886.356,10197.35
Exp/Cntr=0.3,0.1

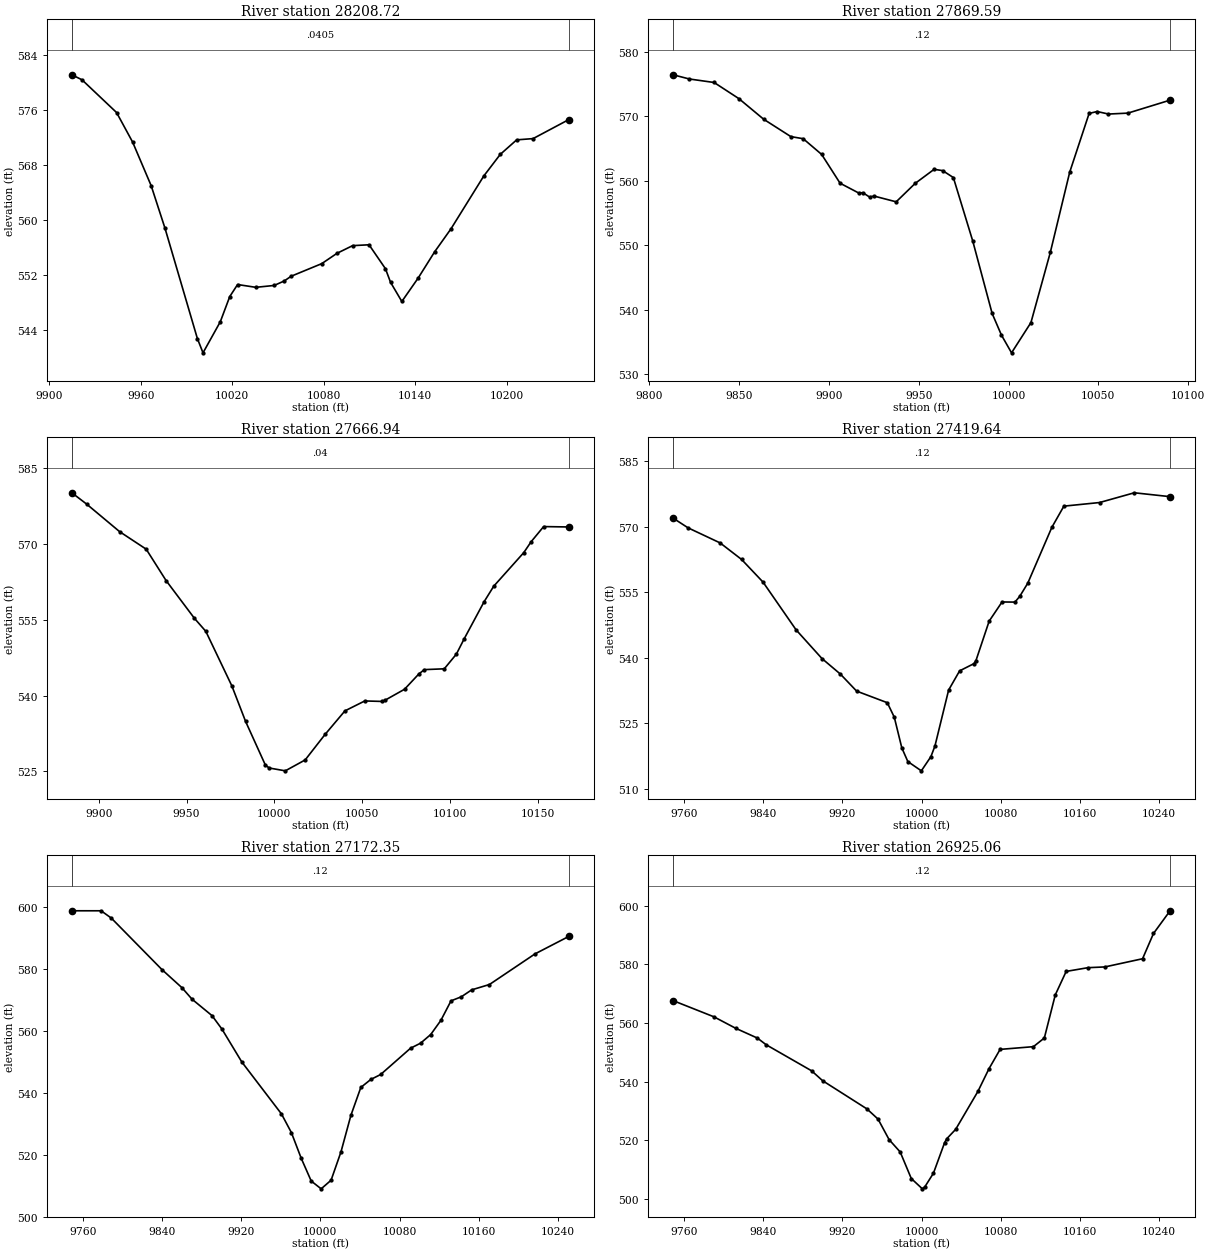
Type RM Length L Ch R = 1 ,28208.72,339.131500,339.131500,339.131500
XS GIS Cut Line= 5
665730.875324816740543.771565318 665634.10799706740492.107653052
665609.506134033 740508.50889504665567.682966977740505.228646636
 665433.19278267740451.924610183
#Sta/Elev= 30
9914.819581.14489921.479580.41569944.151575.66099954.675571.36759966.823565.0412
9975.908558.8462 9997.14542.821610000.83540.747210012.17545.264710018.37548.9256
 10023.5550.671210035.46550.264610047.48550.537210054.08551.1883 10058.6551.8729
10078.66 553.70510088.69555.208510098.92556.321210109.68556.446710120.43552.9762
10123.79550.994510131.19548.208810141.95551.6316 10152.7555.425410163.46558.7795
10184.97566.456510195.73569.580510206.49571.690110217.24571.8711 10240.7574.6383
#Mann= 3 , 0 , 0
9914.819  0.0405       09914.819  0.0405       0 10240.7  0.0405       0
#XS Ineff= 2 , 0
       0                10022.12       0
Bank Sta=9914.819,10240.7
Exp/Cntr=0.3,0.1

Type RM Length L Ch R = 1 ,27869.59,202.655400,202.655400,202.655400
XS GIS Cut Line= 5
665776.798802316740421.582312509665731.695386857740374.018710732
  665689.0521577740364.177965581665650.509239048740377.298959136
  665533.2403588740329.735357374
#Sta/Elev= 30
9813.339576.4427 9822.41575.78959836.191575.24619849.972572.74329863.754569.5488
9878.887566.85399885.759 566.5279896.021564.09199906.284559.62359916.547558.1237
9918.995558.14769922.651557.48899925.202 557.6319937.495556.73959948.059559.5984
9958.622561.78169963.366561.57739969.311560.50369980.103550.66049990.894539.4242
9996.089536.059710001.69533.319610012.48538.012610023.27548.906310034.06561.3441
10044.85570.4455 10049.3570.745810055.64570.352110066.43570.496610089.91572.5093
#Mann= 3 , 0 , 0
9813.339    0.12       09813.339    0.12       010089.91    0.12       0
#XS Ineff= 2 , 0
       0                               0
Bank Sta=9813.339,10089.91
Exp/Cntr=0.3,0.1

Type RM Length L Ch R = 1 ,27666.94,247.292100,247.292100,247.292100
XS GIS Cut Line= 2
665892.427558303740347.776723579665642.308618009740214.926663488
#Sta/Elev= 30
9884.625580.12849893.035 577.8989911.863572.43659927.004568.96929938.328562.7609
9954.499555.28339960.974552.71569975.817 541.917 9983.62534.90589994.943526.2347
9997.135525.674510006.27525.115910017.59 527.27510028.91532.313710040.24536.9788
10051.56538.944110061.09538.849910062.88539.0469 10074.2541.254210082.41544.3019
10085.53545.142410096.85545.302210103.73548.201110108.17551.2213 10119.5558.5462
10125.04561.646910142.14568.286210146.36570.450110153.47573.440510167.84573.3641
#Mann= 3 , 0 , 0
9884.625    0.04       09884.625    0.04       010167.84    0.04       0
#XS Ineff= 2 , 0
       0                               0
Bank Sta=9884.625,10167.84
Exp/Cntr=0.3,0.1

Type RM Length L Ch R = 1 ,27419.64,247.292000,247.292000,247.292000
XS GIS Cut Line= 6
666068.926336825740197.537601154665982.255200853740161.668020993
665920.422471654740127.795534618665891.438665935740105.533429168
665776.168730936740000.775790749665654.144869317739922.296494064
#Sta/Elev= 30
9749.073572.02079764.145569.79559796.613566.32889818.258562.54539839.903557.3597
9873.312546.41049899.406539.84379918.019536.27949934.436532.37579965.413529.7201
9972.464526.39779980.068519.36489986.144516.23539999.775514.109810009.44517.3663
 10013.5519.787810027.32 532.61710038.43537.016810052.92538.674410054.94539.3783
10068.26548.417410081.28552.8048 10094.3552.771110099.21554.110810107.22557.0914
10131.54569.8907 10143.7574.755810179.73575.583610214.84577.818810250.95576.9301
#Mann= 3 , 0 , 0
9749.073    0.12       09749.073    0.12       010250.95    0.12       0
#XS Ineff= 2 , 0
       0                               0
Bank Sta=9749.073,10250.95
Exp/Cntr=0.3,0.1

Type RM Length L Ch R = 1 ,27172.35,247.292100,247.292100,247.292100
XS GIS Cut Line= 6
666183.756831819739892.019619963666041.754459813739864.261342067
665890.329058539739868.190554825665839.590913581739863.806092888
665770.027209762739845.850611983665693.193690223739815.807590599
#Sta/Elev= 30
 9749.09598.90879778.645598.90719788.923596.55099840.138579.86699860.342574.0071
9870.444 570.3149890.648564.99039900.685560.62719920.695550.00969960.736533.2086
9970.759527.17199980.782518.78969990.806511.489310000.83508.967810010.85 511.755
10020.86520.938110030.87532.749310040.88541.7674 10050.9544.334810060.91545.9538
10091.07554.447210101.22556.084410111.44558.878810121.66563.433110131.96569.7768
10142.38571.089710152.81573.329910170.76575.059810216.78584.968710250.93590.6285
#Mann= 3 , 0 , 0
 9749.09    0.12       0 9749.09    0.12       010250.93    0.12       0
#XS Ineff= 2 , 0
       0                               0
Bank Sta=9749.09,10250.93
Exp/Cntr=0.3,0.1

Type RM Length L Ch R = 1 ,26925.06,247.292100,247.292100,247.292100
XS GIS Cut Line= 6
666232.740274916739743.390679531666100.496804025739684.224554767
666006.611832738739636.959343631666004.827334179739636.056257315
665903.943234329739584.822725956665779.781091057739527.293082793
#Sta/Elev= 30
9749.013  567.629790.358562.07799812.269558.17429834.179554.82959843.017552.5597
9888.955543.65329900.043540.28449944.826530.65249956.022527.17979967.217520.1634
9978.413515.94719989.609506.889810000.81 503.36810003.33 504.06110012.02508.7267
10023.24519.114310025.42520.461710034.45523.682910056.88536.6084 10068.1544.3739
10079.32550.968810112.96551.8971   10124554.859310135.03569.563210146.05577.5883
10168.09578.860110185.09579.1127 10223.2581.911810234.22590.526710250.99598.2815
#Mann= 3 , 0 , 0
9749.013    0.12       09749.013    0.12       010250.99    0.12       0
#XS Ineff= 2 , 0
       0                               0
Bank Sta=9749.013,10250.99
Exp/Cntr=0.3,0.1