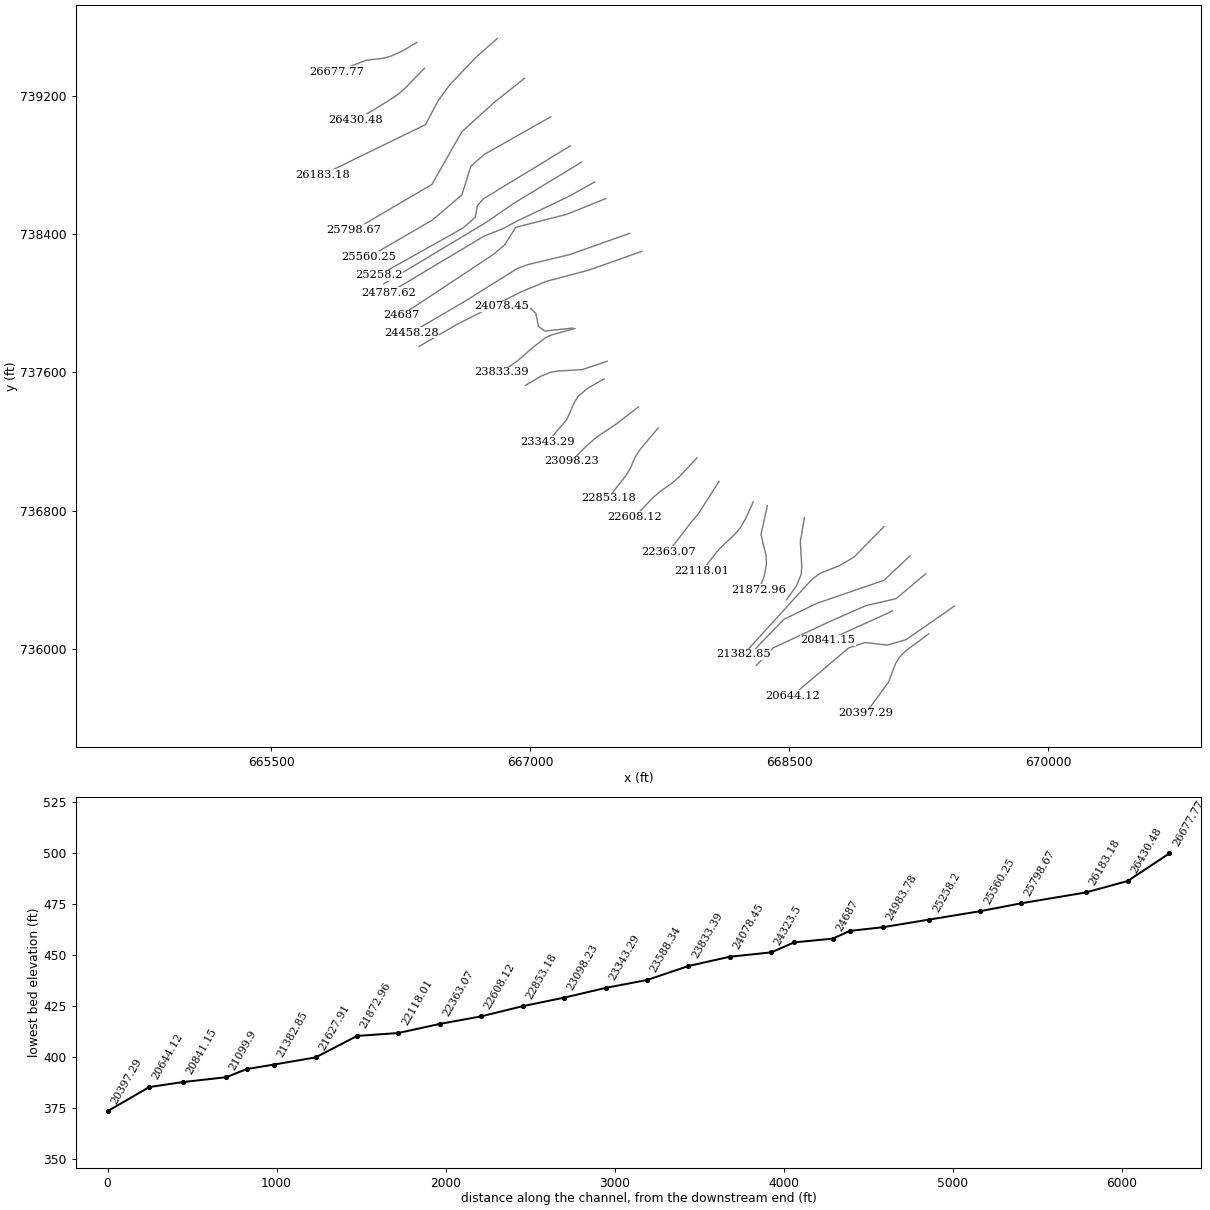
HEC-RAS study 4078_ras.prj: 4078

--- 4078_ras.g01 (geometry) --- (continued)

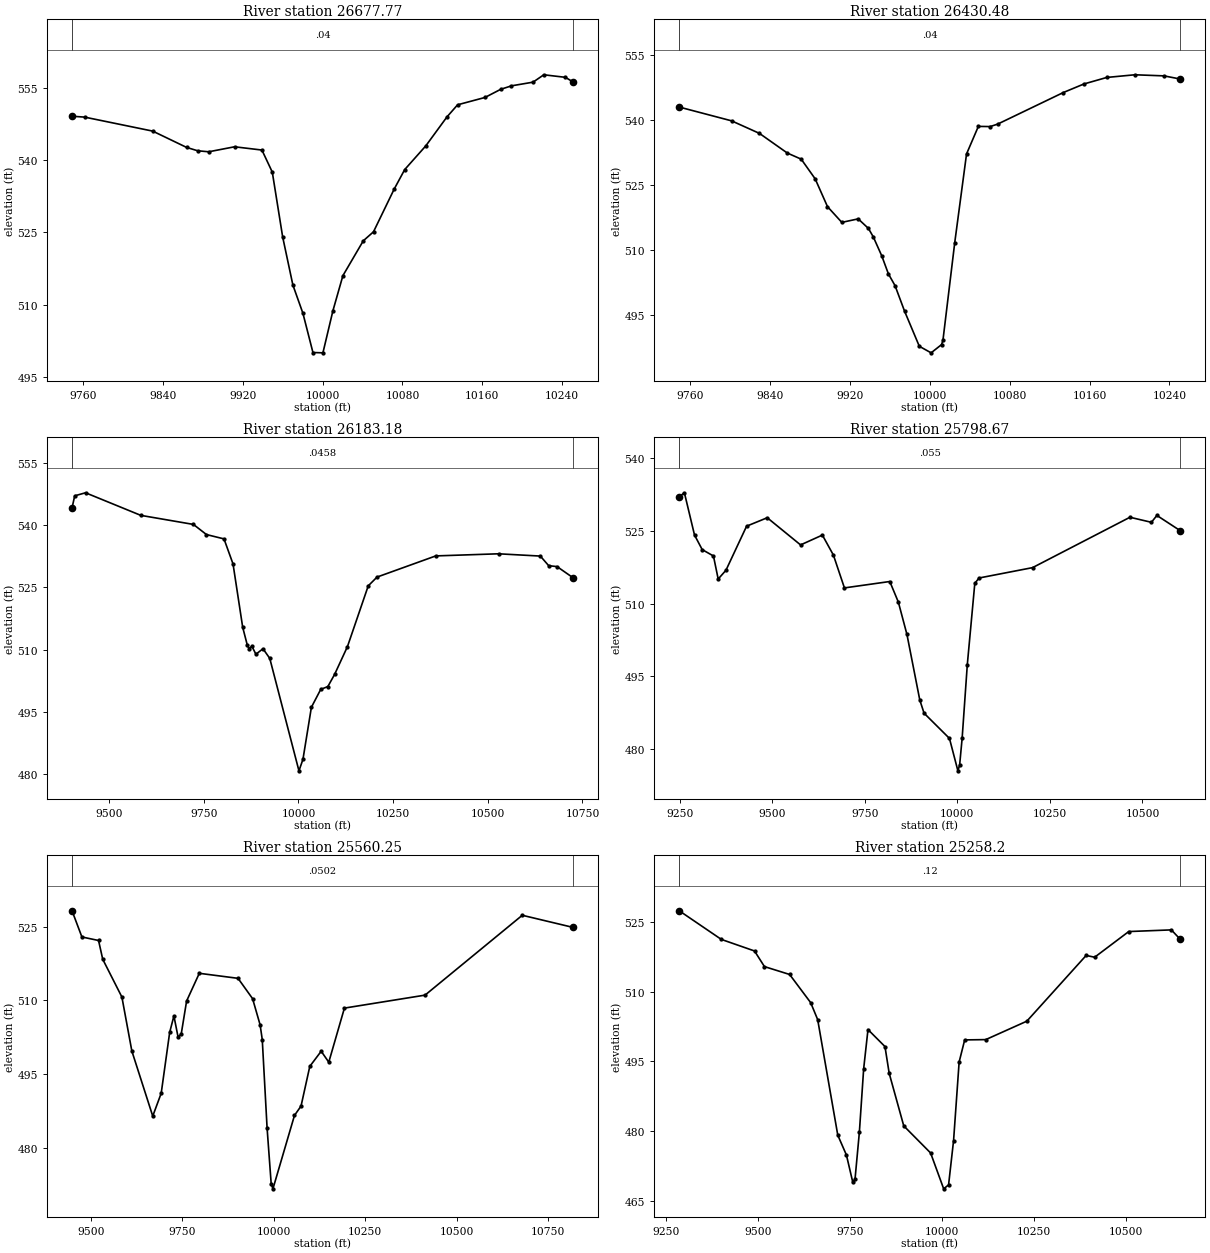
Type RM Length L Ch R = 1 ,26677.77,247.292000,247.292000,247.292000
XS GIS Cut Line= 6
666344.322397916739511.673764358666261.659979308739462.717865943
666193.443200808739431.867924471666149.689268143739419.656849497
666050.717209931 739408.12775004665877.776349066739341.774720188
#Sta/Elev= 30
9749.096549.20649761.714549.02089829.864546.10789863.761542.71889874.909542.0138
9885.979541.80419911.865542.84469939.248 542.165 9949.63537.57099960.012524.0751
9970.244514.05859980.305508.17469990.333500.011110000.33499.943510010.34508.7095
10020.34516.016910040.74 523.26710050.98525.146710071.66534.026610082.23538.1001
10103.39543.047610124.55549.066510135.18551.584710162.59553.113110178.35554.8081
10189.14555.534510210.73556.298410221.52557.835910243.11557.3065 10250.9556.3329
#Mann= 3 , 0 , 0
9749.096    0.04       09749.096    0.04       0 10250.9    0.04       0
#XS Ineff= 2 , 0
       0                               0
Bank Sta=9749.096,10250.9
Exp/Cntr=0.3,0.1

Type RM Length L Ch R = 1 ,26430.48,247.292100,247.292100,247.292100
XS GIS Cut Line= 6
666388.527241786739362.567559854666274.788235261 739245.64042879
666232.466961212 739208.37878585666207.080233552739191.635412453
666093.000597972739119.908508137665990.672664528739062.799385293
#Sta/Elev= 30
9749.081542.9544 9801.49539.78379829.391536.89839857.293532.37799871.243530.9643
9885.194526.44349897.556 520.0389911.898516.42039928.304517.22749938.567515.0214
9943.437513.07169951.891508.72159958.569504.56029965.214 501.8569974.726495.9973
9989.513487.910210001.34486.400710011.77 488.29610013.16489.253910024.99511.7629
10036.81532.165210048.64 538.50410060.46538.4651   10068539.035510133.77546.3027
10154.38548.267210177.28549.7699 10205.4550.382610234.54550.130810250.95549.4006
#Mann= 3 , 0 , 0
9749.081    0.04       09749.081    0.04       010250.95    0.04       0
#XS Ineff= 2 , 0
       0                               0
Bank Sta=9749.081,10250.95
Exp/Cntr=0.3,0.1

Type RM Length L Ch R = 1 ,26183.18,384.508600,384.508600,384.508600
XS GIS Cut Line= 6
666810.479749054739534.993320778666686.350489199 739425.61781238
666533.103877902739264.525502592666464.676116258739170.564255118
666394.144349515739035.309900194 665796.55312889738744.279980264
#Sta/Elev= 30
9402.309544.08539409.394546.99959437.988547.72869583.819542.29329722.851 540.111
9757.168 537.6749803.557536.62879827.409 530.5919852.909 515.3569865.191511.0135
9869.642510.24219877.244510.7733 9887.79508.86679906.526510.18889924.397507.8667
10001.45480.799210012.05483.584410034.29496.097710058.91500.401210077.75 501.088
10095.55504.003910129.54510.712710184.42525.327810207.59527.437110362.69532.5324
10528.35533.041510638.79532.493710660.88530.179410682.97  529.9610725.43527.2607
#Mann= 3 , 0 , 0
9402.309  0.0458       09402.309  0.0458       010725.43  0.0458       0
#XS Ineff= 2 , 0
       0                               0
Bank Sta=9402.309,10725.43
Exp/Cntr=0.3,0.1

Type RM Length L Ch R = 1 ,25798.67,238.425200,238.425200,238.425200
XS GIS Cut Line= 6
666967.254871637739303.685762912666788.537500769739161.137383789
666604.509723008738994.470717132666430.898611844738688.915161595
666010.759723008738442.387383804665976.282657325738425.260067303
#Sta/Elev= 30
9248.609532.10149262.539532.90939289.868524.1799 9310.65521.16629341.033519.8495
9353.825515.08979374.797 516.8969430.573 526.0069486.356527.75279576.427522.1355
9635.326524.1693 9665.12520.03999694.913513.25319817.499514.57539840.653510.3157
9863.807503.64489898.539490.08989910.116487.3652 9978.71482.154310001.54475.4546
10006.19476.651910012.95482.170310026.94497.410510047.19514.1913 10058.6515.2993
10203.25517.442910466.41527.851810524.38526.807510539.16 528.22810602.58525.0603
#Mann= 3 , 0 , 0
9248.609   0.055       09248.609   0.055       010602.58   0.055       0
#XS Ineff= 2 , 0
       0                               0
Bank Sta=9248.609,10602.58
Exp/Cntr=0.3,0.1

Type RM Length L Ch R = 1 ,25560.25,302.048500,302.048500,302.048500
XS GIS Cut Line= 6
  667118.6994102739080.243001089666735.759723008 738863.91516158
666656.593056262 738795.16516158666604.509723008738628.498494893
666433.676389664738482.665161565666064.662927921738268.385086999
#Sta/Elev= 30
 9448.02528.24769475.008522.91559520.559522.19889531.947518.3845  9584.4510.6877
 9611.66499.68899668.802486.44029691.956491.1007 9715.11503.49759726.687506.8386
9738.264502.47339746.809 503.2089761.418509.87699796.149 515.5189902.137514.4937
 9941.87510.36039962.488505.02589968.359 502.0359981.603483.99439992.738472.7104
9997.544471.638510056.51486.585410074.44488.4891 10098.4  496.5710129.55499.6536
10150.32497.4243 10193.1508.434210413.66 511.07510679.62527.332210818.78524.8584
#Mann= 3 , 0 , 0
 9448.02  0.0502       0 9448.02  0.0502       010818.78  0.0502       0
#XS Ineff= 2 , 0
       09889.038                       0
Bank Sta=9448.02,10818.78
Exp/Cntr=0.3,0.1

Type RM Length L Ch R = 1 , 25258.2,274.420300,274.420300,274.420300
XS GIS Cut Line= 6
667232.564241797  738912.2457086  666728.8152785738605.581828222
666694.093056321738565.304050446666681.593056262738498.637383804
666610.759723008738436.137383804666123.815861943738163.388629115
#Sta/Elev= 30
 9285.45527.46139399.946 521.2929490.312518.79589517.331515.42779585.785513.7346
9643.069507.66529662.164 504.0039716.885479.08879740.362474.82299757.637468.9697
9763.839469.64659775.578479.69549787.316493.42549799.055501.85879845.297498.1925
9856.736492.4346 9896.41481.09599969.436475.262510005.05467.528110018.39468.3878
10031.98477.9459 10047.1494.870710062.21499.629310119.52499.693410231.33503.6668
10392.72517.832510415.91517.450810508.64522.983410624.55523.343810649.11521.2882
#Mann= 3 , 0 , 0
 9285.45    0.12       0 9285.45    0.12       010649.11    0.12       0
#XS Ineff= 2 , 0
       0 9817.15                       0
Bank Sta=9285.45,10649.11
Exp/Cntr=0.3,0.1

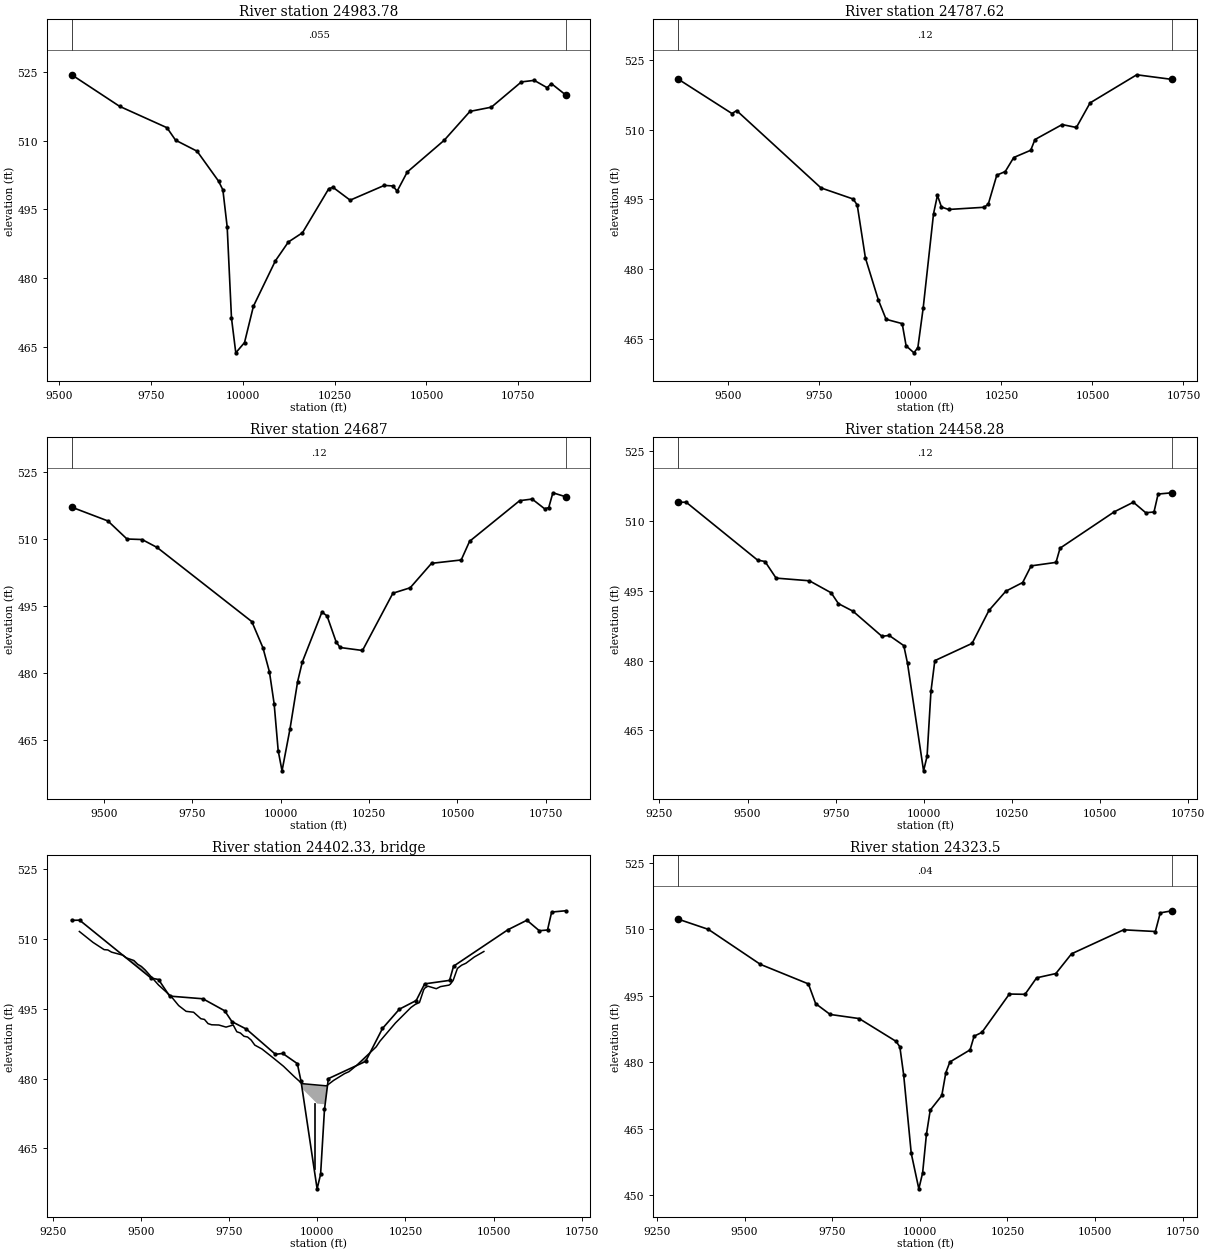
Type RM Length L Ch R = 1 ,24983.78,196.160500,196.160500,196.160500
XS GIS Cut Line= 4
667296.583270162738817.791404426666902.426389605738577.804050446
666742.009722948738467.387383804666151.991677486738113.376556528
#Sta/Elev= 30
9534.372524.32559665.011517.44639793.796512.79719817.211510.0794 9875.75507.6843
9934.289501.15519945.997499.25499957.704491.17639969.412471.3415 9981.12463.7727
10004.86466.005810029.14473.928910088.97483.816510124.25487.909810162.67489.9301
 10234.1 499.49810245.41499.833710292.41497.019110385.35500.234810408.67500.1139
10420.34498.9873 10447.9503.149310548.62 510.07610618.59516.3516 10676.9517.2741
10758.53  522.7710793.52523.1104 10828.5521.518610840.16522.405910878.66519.9686
#Mann= 3 , 0 , 0
9534.372   0.055       09534.372   0.055       010878.66   0.055       0
#XS Ineff= 2 , 0
       0                               0
Bank Sta=9534.372,10878.66
Exp/Cntr=0.3,0.1

Type RM Length L Ch R = 1 ,24787.62,100.618800,100.618800,100.618800
XS GIS Cut Line= 6
667373.912409782738703.699231222667223.954167396738619.470717132
666926.037500739738477.804050446666844.787500739738434.054050446
666734.370834082738390.304050446666181.864808951 738060.35174818
#Sta/Elev= 30
9362.056 520.9119509.912513.49549522.759  514.139754.353497.48359842.937495.0864
9854.011 493.7849876.471482.39719912.034473.34949933.258469.19129977.499 468.263
9988.255 463.48110009.77461.971910020.52463.108810035.09471.590410063.55491.9152
10074.31 495.88210085.33493.367810104.83492.837710202.37493.311210214.02493.9972
10237.32500.223610260.61501.010210283.91504.027610330.49505.584810342.14507.8919
10416.89511.1193 10455.9510.491610493.56515.783110621.68521.837410718.51520.8439
#Mann= 3 , 0 , 0
9362.056    0.12       09362.056    0.12       010718.51    0.12       0
#XS Ineff= 2 , 0
       0                               0
Bank Sta=9362.056,10718.51
Exp/Cntr=0.3,0.1

Type RM Length L Ch R = 1 ,   24687,228.724700,228.724700,228.724700
XS GIS Cut Line= 6
667438.989521742738607.683820128667212.909668028 738516.29755199
666916.401097924738440.493311048666852.501768619738339.384136096
666786.163695514738283.090498134666254.601016585737931.244979633
#Sta/Elev= 30
9408.608 517.1479511.116514.06049565.075510.02429607.785509.90519650.335508.1312
 9918.21491.55649949.739485.68699968.101480.29779981.406473.15229992.844462.6734
10003.69458.177510026.14467.513110047.84478.145310061.09 482.53210116.55493.6756
10131.03492.827910156.57487.050510167.85485.760210231.31485.092710317.32 497.901
10366.19499.114210426.64504.581910510.55505.334810534.23509.507110675.93518.5969
10711.17518.957310746.41516.791910758.15517.0392 10769.9520.360610805.61 519.483
#Mann= 3 , 0 , 0
9408.608    0.12       09408.608    0.12       010805.61    0.12       0
#XS Ineff= 2 , 0
       0                               0
Bank Sta=9408.608,10805.61
Exp/Cntr=0.3,0.1

Type RM Length L Ch R = 1 ,24458.28,134.774700,134.774700,134.774700
XS GIS Cut Line= 6
667575.891013235738405.698012963 667227.29868558738282.234362721
666985.293077439 738224.42076537666926.265299678 738202.71937649
666618.274587393738010.192961067666311.356212089737830.504507617
#Sta/Elev= 30
9302.945514.06169325.506 514.0949528.236501.64199549.376 501.333 9580.86497.7636
9675.268497.19149737.076494.60619757.678492.27439798.883490.65379881.198485.2434
9901.622485.44159943.137483.24919953.678479.44539999.248456.322210009.17459.4644
10020.17473.401310031.16480.0163 10136.9483.731910184.74 490.81310232.59494.9509
10280.43496.817810304.36500.396110374.96501.146710386.42504.200510540.47512.0303
10594.44514.081710629.53511.826610652.93511.978910664.62515.837510703.97516.1129
#Mann= 3 , 0 , 0
9302.945    0.12       09302.945    0.12       010703.97    0.12       0
#XS Ineff= 2 , 0
       0                               0
Bank Sta=9302.945,10703.97
Exp/Cntr=0.3,0.1

Type RM Length L Ch R = 3 ,24402.33,,,
BEGIN DESCRIPTION:
END DESCRIPTION:
Bridge Culvert--1,0,-1,-1, 0
Deck Dist Width WeirC Skew NumUp NumDn MinLoCord MaxHiCord MaxSubmerge Is_Ogee
50.752350,33.270000,2.6,0, 60, 60, , , 0.95, 0, 0,0,,
 9324.76 9363.23 9394.95 9405.53 9416.11 9447.84 9458.41 9479.56 9490.14 9500.72
 9511.29 9549.38 9585.33 9606.48 9627.63 9648.79 9669.49 9679.68 9689.88 9700.07
 9720.46 9740.85 9761.24 9771.44 9781.63 9791.83 9802.02 9812.21 9822.41 9842.80
 9873.38 9903.85 9935.46 9935.46 9956.7410025.8510045.9110045.9110077.4310089.55
10111.8210166.6610177.6310221.5210265.6310277.6010289.5610301.5310304.3710313.50
10337.4310349.3910373.3310377.2010385.2910397.2610409.2210421.1910445.1210472.40
  511.66  509.33  507.76  507.69  507.22  506.57  505.98  505.42  504.62  504.14
  503.40  500.15  497.68  495.73  494.49  494.30  492.90  492.75  491.85  491.60
  491.55  491.10  491.55  490.10  489.83  489.13  488.97  488.31  487.23  486.39
  484.56  482.68  480.38  480.38  478.94  478.47  479.63  479.63  481.11  481.51
  482.90  486.84  488.08  491.99  495.33  495.98  496.38  499.10  499.46  499.90
  499.36  499.81  500.13  500.33  501.15  503.71  504.41  504.82  506.17  507.36
 -488.34 -490.67 -492.24 -492.31 -492.78 -493.43 -494.02 -494.58 -495.38 -495.86
 -496.60 -499.85 -502.32 -504.27 -505.51 -505.70 -507.10 -507.25 -508.15 -508.40
 -508.45 -508.90 -508.45 -509.90 -510.17 -510.87 -511.03 -511.69 -512.77 -513.61
 -515.44 -517.32 -519.62  476.38  474.94  474.47  475.63 -520.37 -518.89 -518.49
 -517.10 -513.16 -511.92 -508.01 -504.67 -504.02 -503.62 -500.90 -500.54 -500.10
 -500.64 -500.19 -499.87 -499.67 -498.85 -496.29 -495.59 -495.18 -493.83 -492.64
 9324.76 9363.23 9394.95 9405.53 9416.11 9447.84 9458.41 9479.56 9490.14 9500.72
 9511.29 9549.38 9585.33 9606.48 9627.63 9648.79 9669.49 9679.68 9689.88 9700.07
 9720.46 9740.85 9761.24 9771.44 9781.63 9791.83 9802.02 9812.21 9822.41 9842.80
 9873.38 9903.85 9938.78 9938.78 9956.7410025.8510049.2310049.2310077.4310089.55
10111.8210166.6610177.6310221.5210265.6310277.6010289.5610301.5310304.3710313.50
10337.4310349.3910373.3310377.2010385.2910397.2610409.2210421.1910445.1210472.40
  511.66  509.33  507.76  507.69  507.22  506.57  505.98  505.42  504.62  504.14
  503.40  500.15  497.68  495.73  494.49  494.30  492.90  492.75  491.85  491.60
  491.55  491.10  491.55  490.10  489.83  489.13  488.97  488.31  487.23  486.39
  484.56  482.68  480.16  480.16  478.94  478.47  479.79  479.79  481.11  481.51
  482.90  486.84  488.08  491.99  495.33  495.98  496.38  499.10  499.46  499.90
  499.36  499.81  500.13  500.33  501.15  503.71  504.41  504.82  506.17  507.36
 -488.34 -490.67 -492.24 -492.31 -492.78 -493.43 -494.02 -494.58 -495.38 -495.86
 -496.60 -499.85 -502.32 -504.27 -505.51 -505.70 -507.10 -507.25 -508.15 -508.40
 -508.45 -508.90 -508.45 -509.90 -510.17 -510.87 -511.03 -511.69 -512.77 -513.61
 -515.44 -517.32 -519.84  476.16  474.94  474.47  475.79 -520.21 -518.89 -518.49
 -517.10 -513.16 -511.92 -508.01 -504.67 -504.02 -503.62 -500.90 -500.54 -500.10
 -500.64 -500.19 -499.87 -499.67 -498.85 -496.29 -495.59 -495.18 -493.83 -492.64
Pier Skew, UpSta & Num, DnSta & Num=  ,9990.69, 2 ,9994.00, 2 , 0 , 0 , 0 ,,
    3.00    3.00
 -521.29  478.71
    3.00    3.00
 -521.32  478.68
BR Coef=-1 , 0 , 0 ,, 0 ,,,0.8,0,1,0,
WSPro=,,,, 1 ,,,, 0 ,,,, 0 ,,,,-1 ,-1 ,-1 , 0 , 0 , 0 , 0 , 0
BC Design=,, 0 ,, 0 ,,,,,,

Type RM Length L Ch R = 1 , 24323.5,245.054300,245.054300,245.054300
XS GIS Cut Line= 6
667646.542962372 738301.45743227667337.202799708738192.302709818
667093.452799708 738127.71937649666943.452799708 738065.21937649
666572.908940971737876.662172079 666356.23770004737750.839866507
#Sta/Elev= 30
 9310.46512.27449396.663509.96929545.203502.07259682.162497.66829702.852493.2187
9744.232490.77719826.992489.8496 9932.32484.71059943.154483.47829953.987477.2122
9975.654459.4661 9997.32451.446810008.15455.042510018.99463.729610029.82469.1835
 10062.9472.503610074.42477.666410085.93480.054610143.52482.789210155.01485.8719
10177.37 486.73510255.63495.380510300.35495.319910333.47 499.03810388.28500.0017
10433.15504.456310581.73509.864910672.28509.4841 10686.3513.687410719.72514.1591
#Mann= 3 , 0 , 0
 9310.46    0.04       0 9310.46    0.04       010719.72    0.04       0
#XS Ineff= 2 , 0
       0                               0
Bank Sta=9310.46,10719.72
Exp/Cntr=0.3,0.1

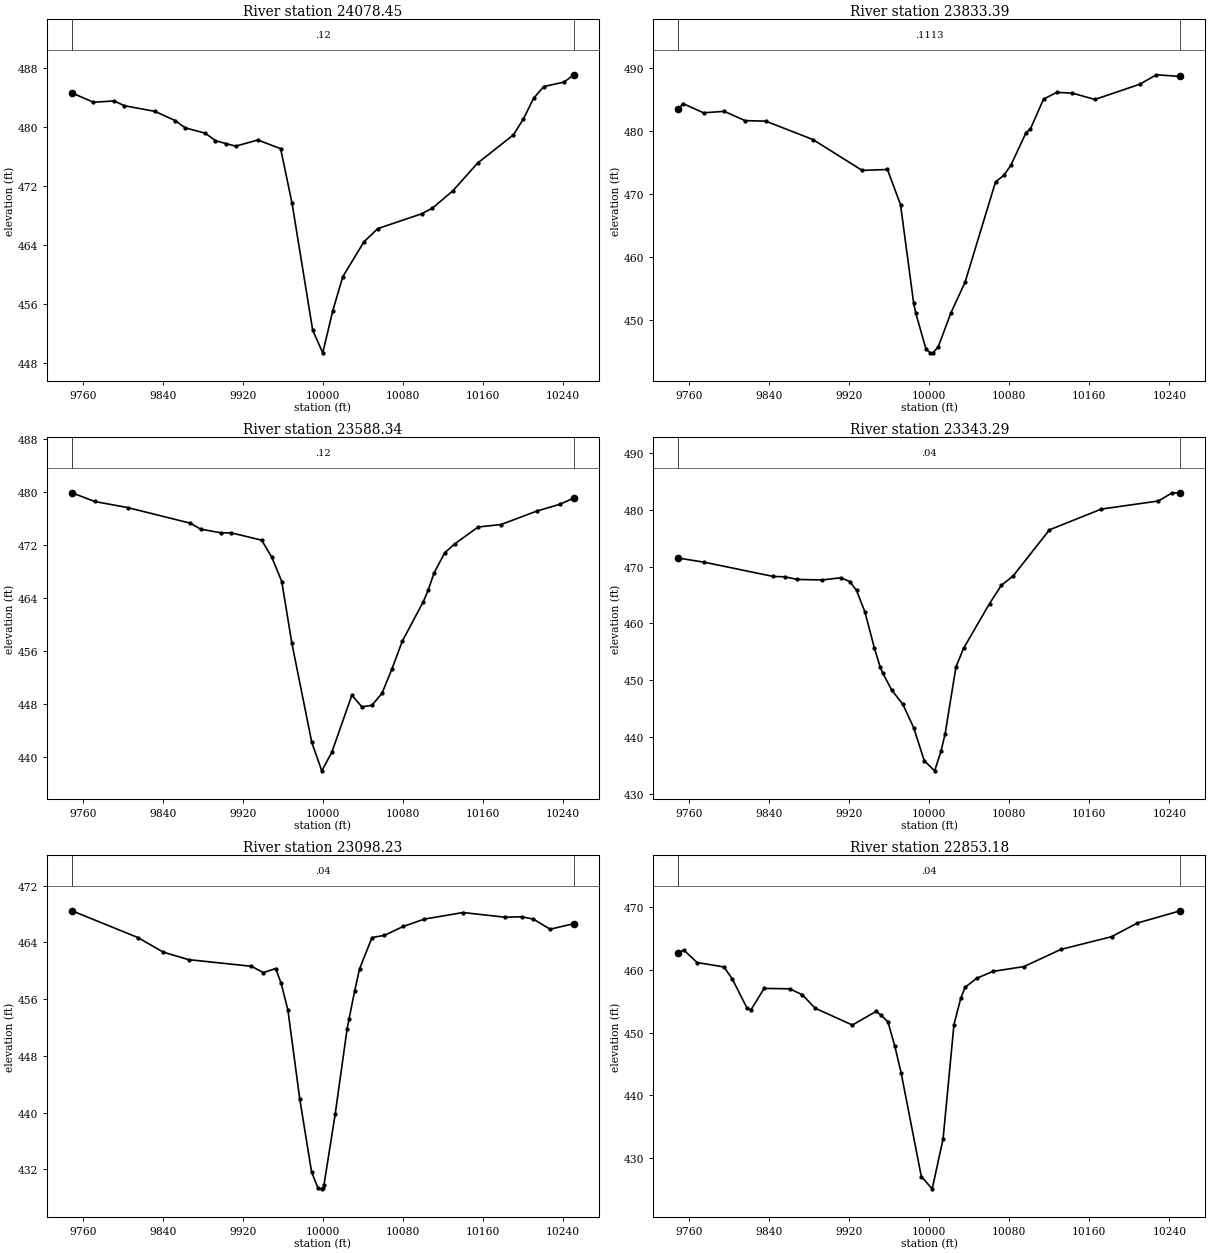
Type RM Length L Ch R = 1 ,24078.45,245.054300,245.054300,245.054300
XS GIS Cut Line= 6
667245.869253835737857.433247269 667085.31315747737839.694827574
667048.181930849737865.692298102667032.426908022 737942.40670018
667002.529438584737970.903482701 666835.24606318737982.377905548
#Sta/Elev= 30
9749.274484.58929770.737 483.3289791.306483.5012 9801.59482.8584 9832.12482.0919
 9852.39480.83529862.422479.85529882.433479.12449892.547478.12279902.698477.7273
9912.875477.36959935.006478.2035 9957.74477.02129969.155469.59899989.753452.3962
9999.801449.315410009.82455.024510019.83459.652110040.91464.369310054.77 466.178
10098.62 468.187 10109.4468.9586   10130 471.33710154.45475.0648 10190.3478.9006
10200.32 481.082 10210.4483.858710220.52485.455410240.77486.060610250.64487.0546
#Mann= 3 , 0 , 0
9749.274    0.12       09749.274    0.12       010250.64    0.12       0
#XS Ineff= 2 , 0
       0                               0
Bank Sta=9749.274,10250.64
Exp/Cntr=0.3,0.1

Type RM Length L Ch R = 1 ,23833.39,245.054200,245.054200,245.054200
XS GIS Cut Line= 6
667259.211323972737854.899352838667129.451662552737819.265836778
667089.540999765737801.896388235667016.502679673  737745.5603075
666929.627311451737670.160509652 666835.45751353737601.796709934
#Sta/Elev= 30
9749.053 483.368 9753.42484.2976 9774.16482.82479794.901483.05679815.641481.5843
9836.382481.50059883.616478.58339932.777473.69039958.086473.83489971.172468.2535
9984.258452.6846 9986.38451.07669996.607445.3664   10001444.762710003.73444.7735
10008.95445.742910021.53451.096810035.65455.932810066.17471.8713 10074.5472.9098
10081.42474.480310096.68479.681310100.98480.228110114.22485.000210127.46486.0628
10143.13485.943510165.45484.938710210.59487.363210227.08488.853910250.96488.5892
#Mann= 3 , 0 , 0
9749.053  0.1113       09749.053  0.1113       010250.96  0.1113       0
#XS Ineff= 2 , 0
       0                               0
Bank Sta=9749.053,10250.96
Exp/Cntr=0.3,0.1

Type RM Length L Ch R = 1 ,23588.34,245.054300,245.054300,245.054300
XS GIS Cut Line= 6
667446.206999392737664.985035626667300.385290984737616.381732928
667158.415320606 737608.53941076667119.019815259   737601.632716
667061.212518245 737577.97586567666972.865086847 737525.50880894
#Sta/Elev= 30
9749.055479.92979771.773 478.6129804.785477.69329867.307475.3388 9877.66474.4372
9898.226473.87119908.428473.87259938.772472.7613 9948.81470.21039958.846466.5178
9968.849457.26119988.855442.20459998.858437.901110008.94440.728210028.94449.3398
10038.95447.571310048.97 447.80310059.05449.615410069.19 453.36810079.44457.5287
10100.46463.485110105.38465.261910111.07467.795210121.82 470.86410131.65 472.188
10155.23474.758910178.14475.1302 10214.1477.176210236.59478.1764 10250.9479.1211
#Mann= 3 , 0 , 0
9749.055    0.12       09749.055    0.12       0 10250.9    0.12       0
#XS Ineff= 2 , 0
       0                               0
Bank Sta=9749.055,10250.9
Exp/Cntr=0.3,0.1

Type RM Length L Ch R = 1 ,23343.29,245.054300,245.054300,245.054300
XS GIS Cut Line= 6
667427.296193287737562.838789027667331.834914619737507.647926183
667280.103970302737463.981769286667258.645620715737432.363860516
667210.374191903737324.908508261667100.981850703737198.926652607
#Sta/Elev= 30
9749.102471.50819774.596470.80129843.928468.27659855.679468.21199867.888467.7519
9892.729467.65719911.417468.04459920.431467.37899927.249465.80179935.571462.0229
9945.096455.63639950.793452.33579953.178451.32679962.455448.23019973.562445.7376
9984.471441.55529994.925435.797110005.31434.0169 10011.6437.425610015.84440.5937
10026.58452.305610034.17455.601610060.17463.487310071.99466.7098 10083.8468.3698
 10120.1 476.49410171.97480.150310228.91 481.57510242.62482.991610250.95 483.024
#Mann= 3 , 0 , 0
9749.102    0.04       09749.102    0.04       010250.95    0.04       0
#XS Ineff= 2 , 0
       0                               0
Bank Sta=9749.102,10250.95
Exp/Cntr=0.3,0.1

Type RM Length L Ch R = 1 ,23098.23,245.054300,245.054300,245.054300
XS GIS Cut Line= 6
667627.120630736737401.466231898667498.279112972737301.431563056
667403.363420103737238.294209205 667371.25875281737214.295889189
667317.405095948737166.258334458667238.315199892737086.183138958
#Sta/Elev= 30
9749.018468.45969815.004464.68129840.325462.63019865.645461.57039928.342 460.635
9940.548459.74249952.753  460.329958.236458.21549964.958 454.4879976.804441.9699
9988.632431.64239995.146429.3493    9999429.252410000.45429.3581   10001429.7397
10012.33439.835310024.22451.825210026.16453.206510031.66 457.095 10036.6460.2526
10049.09464.683910061.57464.996810080.21466.244710101.43 467.28710140.18 468.213
10182.34467.549110198.75467.614510210.45467.287110227.21465.862610250.96466.6427
#Mann= 3 , 0 , 0
9749.018    0.04       09749.018    0.04       010250.96    0.04       0
#XS Ineff= 2 , 0
       0                               0
Bank Sta=9749.018,10250.96
Exp/Cntr=0.3,0.1

Type RM Length L Ch R = 1 ,22853.18,245.054300,245.054300,245.054300
XS GIS Cut Line= 6
667741.098589371737278.868545011667636.150373237737154.154504556
667607.563878431 737109.11153034667581.199716385737048.737399108
667556.808982534737006.950525818667451.937235215736871.841305822
#Sta/Elev= 30
9749.102462.69479754.313463.19579767.785461.19619794.728 460.4829802.975458.5591
9817.899453.86119821.671453.64569834.842 457.0669860.267457.0008 9872.98456.0598
9885.693453.92249923.037451.21669946.724453.39369951.665452.79489958.568 451.737
9965.543 447.8019971.822443.55669991.956427.050710002.84 425.08510013.73433.0515
10024.61451.300110031.43455.501210035.76457.244810047.33458.679110063.56459.7796
10094.54460.543310131.53463.284610182.18 465.31710208.04467.495210250.93469.4495
#Mann= 3 , 0 , 0
9749.102    0.04       09749.102    0.04       010250.93    0.04       0
#XS Ineff= 2 , 0
       0                               0
Bank Sta=9749.102,10250.93
Exp/Cntr=0.3,0.1

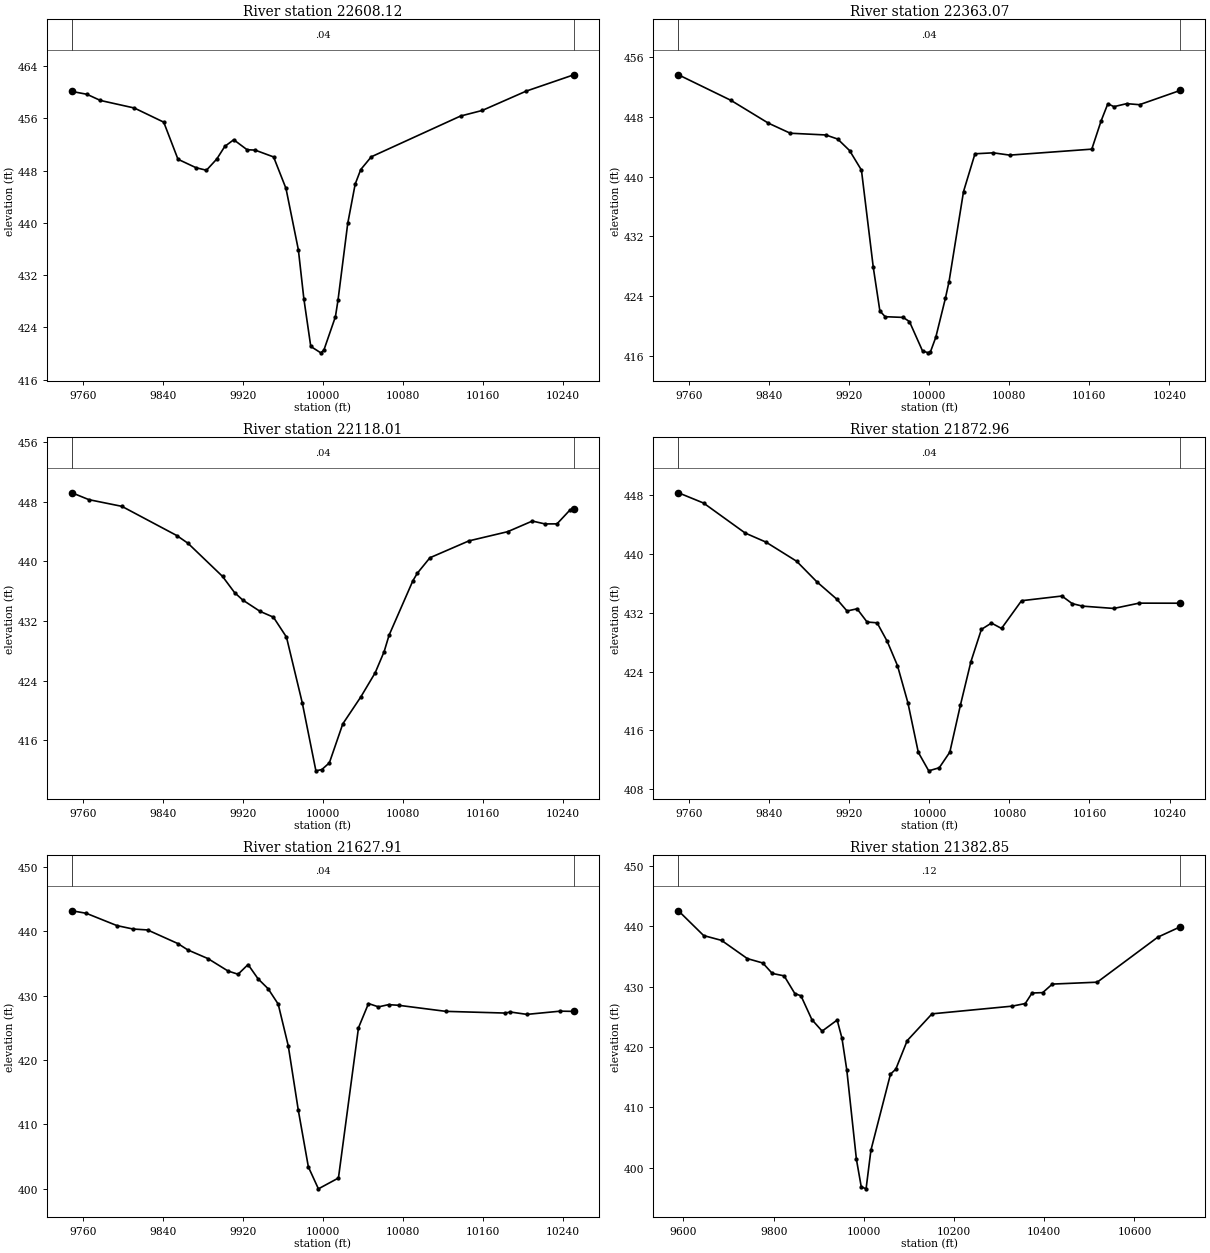
Type RM Length L Ch R = 1 ,22608.12,245.054300,245.054300,245.054300
XS GIS Cut Line= 6
667966.504495924 737106.18180738667867.721189921737000.275838978
667825.582435869736963.300094439667754.424003257736911.763464183
667716.089578813736879.737479318667602.394733801736762.755071831
#Sta/Elev= 30
9749.044460.13349764.027 459.7019777.426 458.7589811.399457.59879840.835455.4304
9855.073449.7508 9873.23448.4438 9883.55448.06559893.914449.78989901.913451.7202
9910.838452.73499924.142451.21069932.236451.14739950.697450.10189963.088445.2757
 9975.48435.86989980.964428.37169987.871421.07419997.898420.0917   10001420.5167
10012.53425.626510015.11428.158210024.83439.906910032.28445.933610037.84448.1681
10048.39450.123210137.68 456.369 10159.3457.221110203.23460.180910250.97462.6886
#Mann= 3 , 0 , 0
9749.044    0.04       09749.044    0.04       010250.97    0.04       0
#XS Ineff= 2 , 0
       0                               0
Bank Sta=9749.044,10250.97
Exp/Cntr=0.3,0.1

Type RM Length L Ch R = 1 ,22363.07,245.054200,245.054200,245.054200
XS GIS Cut Line= 6
668093.407272241736969.280564277667972.435675626736779.782788732
667956.259565715736760.533779558667933.050735441736734.108653232
667862.806424173736642.100452549667799.821098362736563.076557732
#Sta/Elev= 30
9749.038453.66019801.572450.2321    9839447.17589860.892445.82519896.483445.5907
9908.347445.04289920.211443.50259932.075440.88229943.939427.82519950.507 422.005
9955.803421.22839973.857421.13329980.104420.56899993.166416.6393    9999416.3839
   10001416.486710006.42418.462310016.02423.6836 10019.7425.946910034.17438.0097
10045.63443.069810063.92443.1971 10080.4442.887910162.45443.6905 10171.8447.4887
 10178.5449.776810184.58 449.38810197.37449.788910210.16449.648810250.98451.5689
#Mann= 3 , 0 , 0
9749.038    0.04       09749.038    0.04       010250.98    0.04       0
#XS Ineff= 2 , 0
       0                               0
Bank Sta=9749.038,10250.98
Exp/Cntr=0.3,0.1

Type RM Length L Ch R = 1 ,22118.01,245.054300,245.054300,245.054300
XS GIS Cut Line= 6
668291.638235706 736850.45287409668246.235770804 736750.18184757
668214.861642413 736698.01635978668185.261264484736663.549037071
668091.919405698736574.655364795667994.759557496736452.023965891
#Sta/Elev= 30
9749.089449.16839766.052448.24619798.984447.35299853.871443.44479865.089442.4096
9899.686437.96529911.694435.8017 9919.83434.80839937.238433.28269950.565432.5059
9963.601429.83759979.452421.00369993.036411.9264    9999412.1026 10006.5 412.998
10019.92418.217410037.85421.808210052.31425.060610061.25427.888710066.21430.0981
10090.05437.399210094.48438.397910107.04440.465710146.04442.726510184.77 443.956
10209.44445.381410222.04444.997410234.12 445.00410247.22446.881610250.97447.0261
#Mann= 3 , 0 , 0
9749.089    0.04       09749.089    0.04       010250.97    0.04       0
#XS Ineff= 2 , 0
       0                               0
Bank Sta=9749.089,10250.97
Exp/Cntr=0.3,0.1

Type RM Length L Ch R = 1 ,21872.96,245.054300,245.054300,245.054300
XS GIS Cut Line= 6
668373.415517368736828.999810511668336.531225238736661.450400988
 668366.55668207736537.009291079668368.222588918736488.415713987
668355.001848481736420.882606528 668325.64983448736343.039498401
#Sta/Elev= 30
9749.077448.33789774.213446.94039815.869442.85189836.531441.62699867.217439.0197
 9887.53436.20829907.598433.82949917.633432.24219927.652432.54229937.663430.7441
9947.698430.63119957.845 428.1039968.044424.81269978.463419.76049988.881412.9964
9999.298  410.4810009.82410.899110020.38413.024110030.94419.404610041.49425.3508
10051.95429.739610062.01430.598810072.07429.866510092.08433.642310132.45434.2812
10142.72433.249310153.02432.9052 10184.3432.589510209.56433.312210250.81 433.302
#Mann= 3 , 0 , 0
9749.077    0.04       09749.077    0.04       010250.81    0.04       0
#XS Ineff= 2 , 0
       0                               0
Bank Sta=9749.077,10250.81
Exp/Cntr=0.3,0.1

Type RM Length L Ch R = 1 ,21627.91,245.054300,245.054300,245.054300
XS GIS Cut Line= 6
668587.804474064736758.933435996668564.328719184736619.439741323
668572.777384387736476.059178582668569.152389332736430.829947362
668540.292446991736362.066513239 668484.13921662736284.157266292
#Sta/Elev= 30
9749.092443.19169763.344442.80389794.028440.88859810.046440.35719824.713440.2093
9854.947438.09579865.008437.09799885.131435.75139905.166433.82149915.166433.3231
9925.166434.82979935.171432.61029945.226431.06739955.281 428.6829965.336422.2047
9975.391 412.1729985.446403.3634 9995.49399.950610015.52401.634410035.55424.9965
10045.55428.766310055.56428.248610065.62428.596710075.73428.492610122.94427.5499
 10182.1427.286510187.46427.446310203.97427.080410237.19427.581310250.87427.5453
#Mann= 3 , 0 , 0
9749.092    0.04       09749.092    0.04       010250.87    0.04       0
#XS Ineff= 2 , 0
       0                               0
Bank Sta=9749.092,10250.87
Exp/Cntr=0.3,0.1

Type RM Length L Ch R = 1 ,21382.85,162.802500,162.802500,162.802500
XS GIS Cut Line= 6
669048.637723356 736706.94898127668874.964719564 736530.86931859
 668786.79463172736479.214852408668678.508165777736437.445800722
668629.675526291736400.228828475668235.528182997735967.789676692
#Sta/Elev= 30
9588.746442.5611 9644.73438.45169684.321437.65649741.608434.6349 9775.84433.9069
9796.806432.17979823.174431.77219846.865428.84279860.524428.46549884.687424.5242
9907.434422.61519940.758424.45299951.432421.42919962.106416.17219983.454401.3649
9994.128396.823110004.88396.474910015.64402.887510059.02415.487710070.74416.3088
10096.12421.043710151.06425.480110328.95426.755910357.91427.190710372.89428.9323
10396.53 428.99510417.83430.410510517.41 430.72610651.71438.186710701.68439.9081
#Mann= 3 , 0 , 0
9588.746    0.12       09588.746    0.12       010701.68    0.12       0
#XS Ineff= 2 , 0
       0                               0
Bank Sta=9588.746,10701.68
Exp/Cntr=0.3,0.1

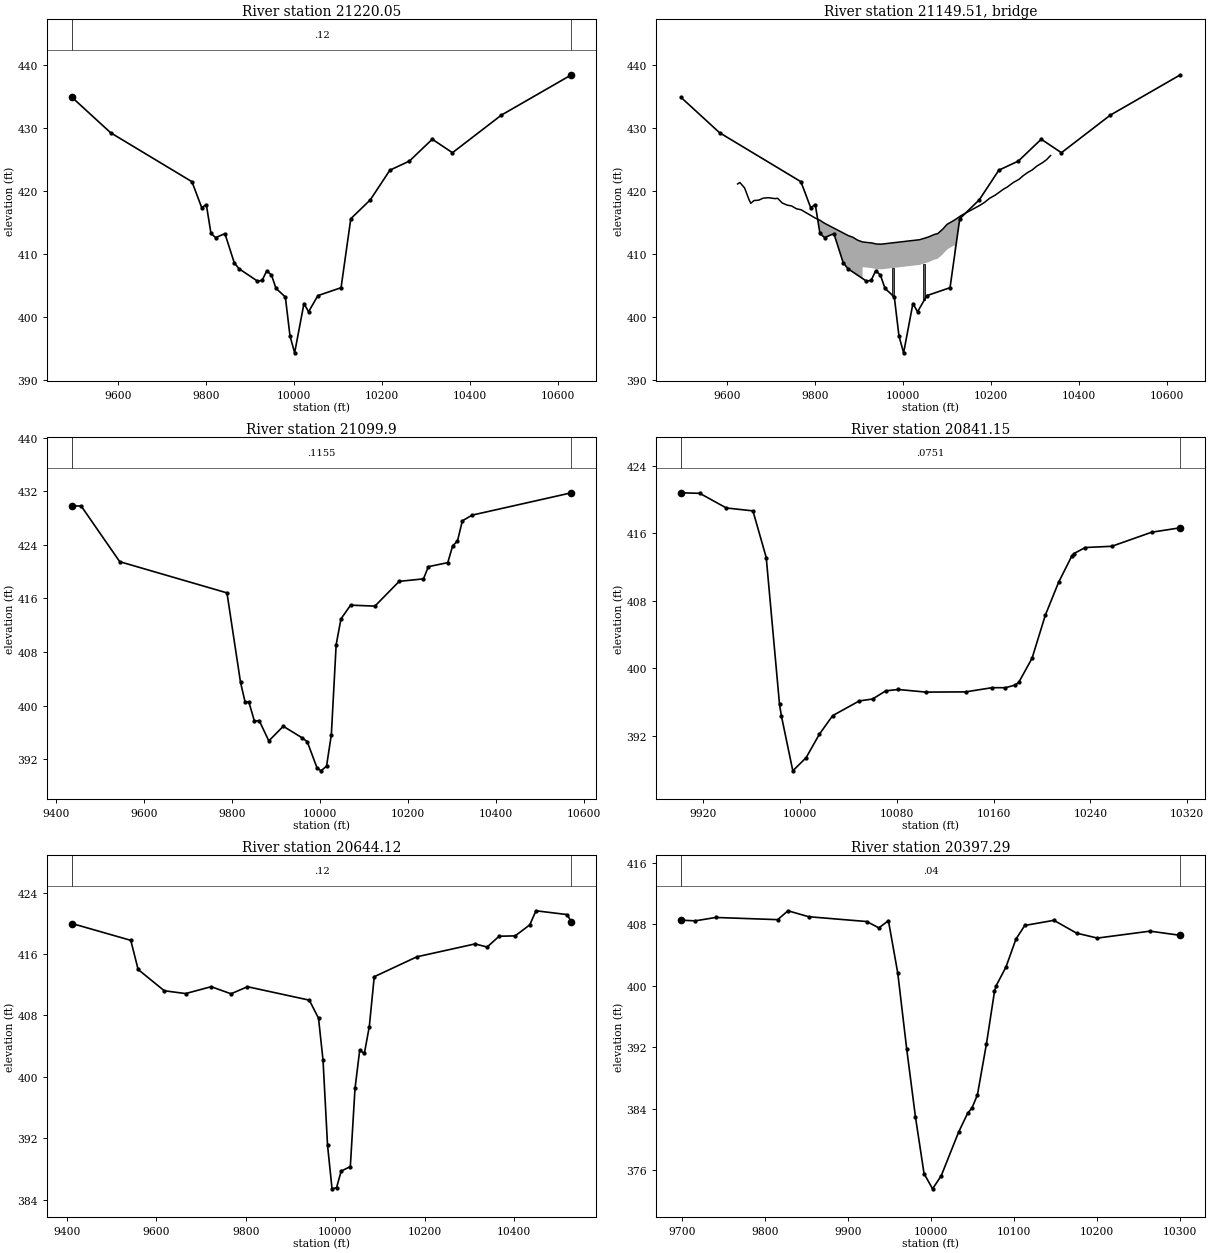
Type RM Length L Ch R = 1 ,21220.05,120.145600,120.145600,120.145600
XS GIS Cut Line= 5
669199.078808427736538.086538866669049.088177741736396.648989886
668660.199288785736263.315656558668468.532622188736170.260100991
668256.260383561735950.167306212
#Sta/Elev= 30
9494.672434.82439582.747429.18819767.582 421.4189789.724417.31139800.296417.7796
9810.867413.19539821.439412.53789842.581413.17259863.724408.55949874.296407.6155
9916.581405.63279927.153405.72919937.724407.27529948.296 406.6089958.867404.4728
 9980.01403.10539990.581396.919710001.15394.2403 10022.3402.061310032.87400.7627
10054.01403.326410106.75404.585210128.84 415.538 10173.3418.545510217.77423.2485
10262.23424.699110314.15428.1656 10360.1426.022710471.24431.987210630.78438.3994
#Mann= 3 , 0 , 0
9494.672    0.12       09494.672    0.12       010630.78    0.12       0
#XS Ineff= 2 , 0
       09963.397        10033.41       0
Bank Sta=9494.672,10630.78
Exp/Cntr=0.3,0.1

Type RM Length L Ch R = 3 ,21149.51,,,
BEGIN DESCRIPTION:
END DESCRIPTION:
Bridge Culvert--1,0,-1,-1, 0
Deck Dist Width WeirC Skew NumUp NumDn MinLoCord MaxHiCord MaxSubmerge Is_Ogee
44.432800,31.280000,2.6,0, 51, 46, , , 0.95, 0, 0,0,,
 9623.64 9628.81 9639.52 9650.23 9653.68 9660.95 9671.66 9681.53 9693.09 9709.39
 9714.52 9725.23 9735.95 9746.66 9757.38 9768.09 9800.23 9810.95 9820.82 9875.23
 9885.95 9896.66 9907.81 9907.81 9928.80 9939.52 9950.2310037.7610057.3710071.53
10078.8010089.5110100.2310116.9910116.9910132.3710175.2910186.0510196.8110209.40
10229.1010236.4810250.6210263.5510272.1410282.9010293.6610304.4210317.7010325.94
10335.33
  421.06  421.29  420.42  418.45  417.99  418.43  418.49  418.80  418.88  418.73
  418.79  418.03  417.71  417.56  417.12  416.96  415.64  415.29  414.84  412.86
  412.59  412.13  411.85  411.85  411.69  411.52  411.50  412.21  412.63  413.05
  413.18  413.84  414.66  415.33  415.33  416.06  417.69  418.18  418.79  419.28
  420.27  420.55  421.29  421.79  422.32  422.86  423.29  423.91  424.47  424.90
  425.57
 -578.94 -578.71 -579.58 -581.55 -582.01 -581.57 -581.51 -581.20 -581.12 -581.27
 -581.21 -581.97 -582.29 -582.44 -582.88 -583.04 -584.36 -584.71 -585.16 -587.14
 -587.41 -587.87 -588.15  407.85  407.69  407.52  407.50  408.21  408.63  409.05
  409.18  409.84  410.66  411.33 -584.67 -583.94 -582.31 -581.82 -581.21 -580.72
 -579.73 -579.45 -578.71 -578.21 -577.68 -577.14 -576.71 -576.09 -575.53 -575.10
 -574.43
 9623.64 9628.81 9639.52 9650.23 9653.68 9660.95 9671.66 9681.53 9693.09 9709.39
 9714.52 9725.23 9735.95 9746.66 9757.38 9768.09 9828.24 9828.24 9875.23 9885.95
 9896.66 9904.39 9928.80 9939.52 9950.2310037.4210037.4210078.8010089.5110100.23
10110.9410132.3710182.3210196.8110209.4010229.1010236.4810250.6210263.5510272.14
10282.9010293.6610304.4210317.7010325.9410335.33
  421.06  421.29  420.42  418.45  417.99  418.43  418.49  418.80  418.88  418.73
  418.79  418.03  417.71  417.56  417.12  416.96  414.57  414.57  412.86  412.59
  412.13  411.91  411.69  411.52  411.50  412.21  412.21  413.18  413.84  414.66
  415.06  416.06  418.00  418.79  419.28  420.27  420.55  421.29  421.79  422.32
  422.86  423.29  423.91  424.47  424.90  425.57
 -578.94 -578.71 -579.58 -581.55 -582.01 -581.57 -581.51 -581.20 -581.12 -581.27
 -581.21 -581.97 -582.29 -582.44 -582.88 -583.04 -585.43  410.57  408.86  408.59
  408.13  407.91  407.69  407.52  407.50  408.21 -587.79 -586.82 -586.16 -585.34
 -584.94 -583.94 -582.00 -581.21 -580.72 -579.73 -579.45 -578.71 -578.21 -577.68
 -577.14 -576.71 -576.09 -575.53 -575.10 -574.43
Pier Skew, UpSta & Num, DnSta & Num=  ,9977.04, 2 ,9897.47, 2 , 0 , 0 , 0 ,,
    3.00    3.00
 -588.32  411.68
    3.00    3.00
 -587.90  412.10
Pier Skew, UpSta & Num, DnSta & Num=  ,10047.77, 2 ,9968.19, 2 , 0 , 0 , 0 ,,
    3.00    3.00
 -587.55  412.45
    3.00    3.00
 -588.40  411.60
BR Coef=-1 , 0 , 0 ,, 0 ,,,0.8,0,1,0,
WSPro=,,,, 1 ,,,, 0 ,,,, 0 ,,,,-1 ,-1 ,-1 , 0 , 0 , 0 , 0 , 0
BC Design=,, 0 ,, 0 ,,,,,,

Type RM Length L Ch R = 1 , 21099.9,258.752100,258.752100,258.752100
XS GIS Cut Line= 6
669291.052966565 736434.85023886669119.227066576 736290.26010102
 668946.31039992736250.676767647668742.143733263736161.093434319
668406.727066606736004.843434319 668310.01183561735904.478571968
#Sta/Elev= 30
9436.789429.83039457.769429.80149545.275421.49389788.796416.83599819.572403.4755
9829.831400.58199838.745400.49769851.097397.69449862.017397.76559883.857394.7301
9916.618396.92039960.299395.1622 9971.22394.5992 9993.06390.7436 10002.2390.2644
 10014.9390.961110025.82395.660210036.74409.098410047.66412.951710069.58415.0054
10124.74414.8586 10179.9418.555510235.06418.929210246.09420.747910290.22421.3541
10301.25423.849210312.28424.588410323.31427.591510345.38428.443310571.11431.7826
#Mann= 3 , 0 , 0
9436.789  0.1155       09436.789  0.1155       010571.11  0.1155       0
#XS Ineff= 2 , 0
       09953.384         10033.6       0
Bank Sta=9436.789,10571.11
Exp/Cntr=0.3,0.1

Type RM Length L Ch R = 1 ,20841.15,197.028000,197.028000,197.028000
XS GIS Cut Line= 2
669099.186366886736219.317626745668723.350310057736048.590837508
#Sta/Elev= 30
9901.657420.82699917.238420.76029939.205419.02559961.172418.68099972.155413.1521
9983.139395.73569984.632394.41619994.122387.861510005.11389.421210016.09 392.207
10027.07394.407810049.04396.148410060.02396.375510071.01397.349110081.35397.5055
10103.96397.196210136.91397.222710158.87397.720110169.86 397.71610178.06398.0419
10180.84398.349710191.82401.206410202.81406.321910213.79410.222710224.77413.3532
10226.42413.619510235.76414.336410257.72414.482910290.67416.150910314.45416.6801
#Mann= 3 , 0 , 0
9901.657  0.0751       09901.657  0.0751       010314.45  0.0751       0
#XS Ineff= 2 , 0
       0                               0
Bank Sta=9901.657,10314.45
Exp/Cntr=0.3,0.1

Type RM Length L Ch R = 1 ,20644.12,246.837000,246.837000,246.837000
XS GIS Cut Line= 6
669457.428889632736248.101753876 669176.86352095 736052.70431307
669068.160637408736021.570926115668939.001832873736036.217275113
668843.326753289736004.561421826668517.578115167735728.047234338
#Sta/Elev= 30
9411.389419.9699 9542.95417.7793 9559.36413.98849617.818411.21579665.639410.8492
9722.681411.74519767.063410.8203 9803.86411.74169942.097409.99319962.706 407.646
9972.819402.17389982.859391.12059992.944385.4266 10003.1385.590810013.34 387.729
10033.85 388.33210044.31398.495510054.77403.459410065.24403.061410076.28406.5503
10087.31 413.04310182.74415.638110312.82417.314610339.78416.907710366.48418.3126
10402.46418.362710435.12 419.79710448.95421.628810518.29 421.13710528.35420.1795
#Mann= 3 , 0 , 0
9411.389    0.12       09411.389    0.12       010528.35    0.12       0
#XS Ineff= 2 , 0
       0                               0
Bank Sta=9411.389,10528.35
Exp/Cntr=0.3,0.1

Type RM Length L Ch R = 1 ,20397.29,246.836900,246.836900,246.836900
XS GIS Cut Line= 6
669308.805582499736087.166314351669179.081200166735991.431080244
669136.270902704 735948.96588917669115.046295723 735913.09802027
 669074.94002006735806.589000475668942.587321544735625.982282022
#Sta/Elev= 30
 9699.09408.55099716.248408.46029741.105408.90159815.675408.61789828.103409.7717
 9852.96408.99919922.965408.37089937.661407.54339949.093408.4899 9960.34401.6707
9971.069391.82689981.675 382.9339992.017375.563910002.29373.579510012.66375.2682
10033.67380.963110044.59383.4244 10049.8384.108810056.32385.815910067.26392.4846
 10076.9399.2739 10078.8399.997110090.74402.452910102.68406.075210113.37407.8597
10148.49408.529910175.74406.864410200.82406.217810264.17407.119910300.93406.5739
#Mann= 3 , 0 , 0
 9699.09    0.04       0 9699.09    0.04       010300.93    0.04       0
#XS Ineff= 2 , 0
       0                               0
Bank Sta=9699.09,10300.93
Exp/Cntr=0.3,0.1