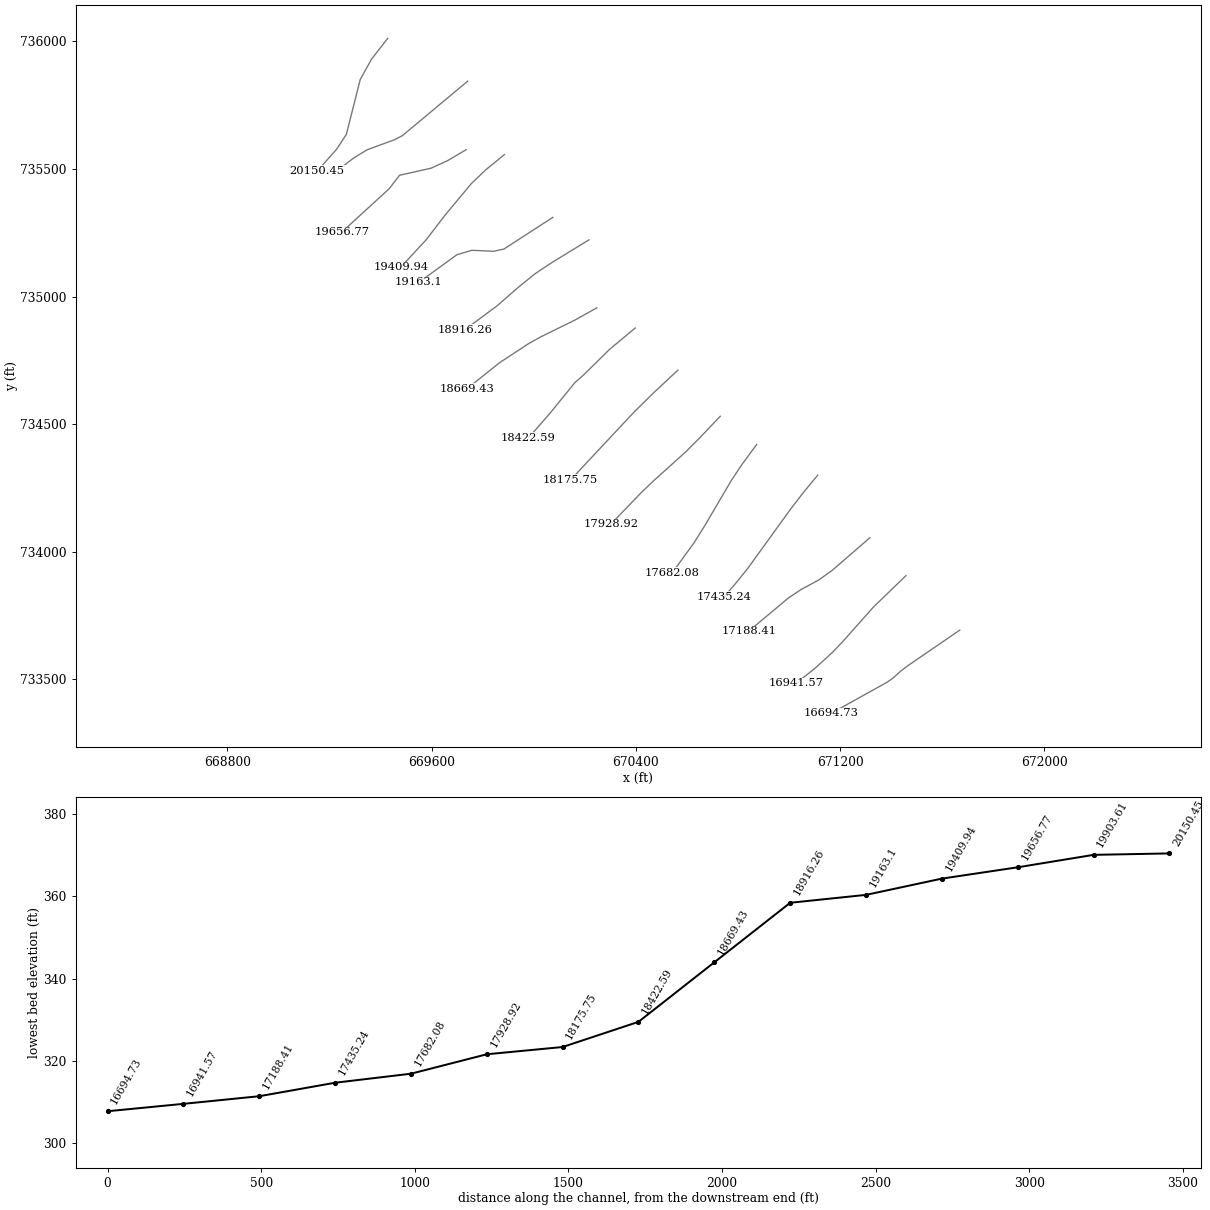
HEC-RAS study 4078_ras.prj: 4078

--- 4078_ras.g01 (geometry) --- (continued)

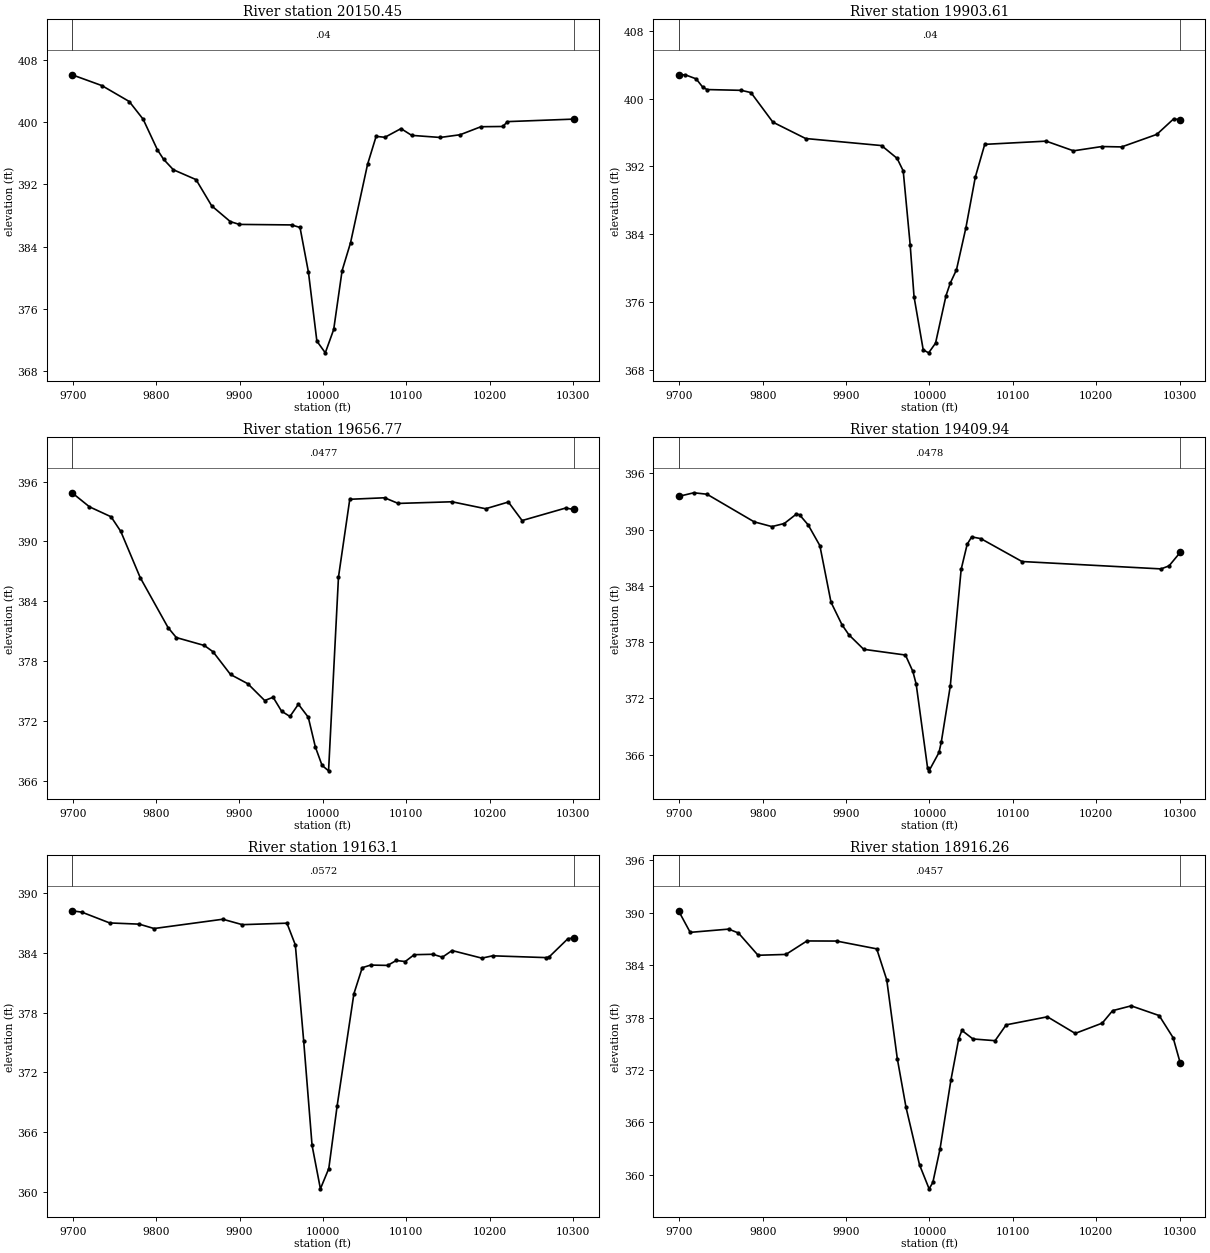
Type RM Length L Ch R = 1 ,20150.45,246.837000,246.837000,246.837000
XS GIS Cut Line= 6
669427.944918983736011.879142313669364.184364727735930.047195493
669320.114241324735850.366235942669265.780123068 735635.68877718
669227.668852827735577.373437778669151.480565784735491.819931029
#Sta/Elev= 30
 9699.09406.06449734.871404.67499767.651402.63349784.349400.35899801.502396.4237
9808.813395.22169820.563393.87519847.779392.6077 9866.56389.2396 9888.87387.2175
9899.755386.85779962.378386.79229972.486386.46439982.594380.72259992.701371.8771
 10002.8370.372810012.88373.372610022.96380.927510033.07384.498710053.48394.5644
10063.77398.162810074.25398.0392 10093.6399.154110106.42398.287110140.63398.0184
10164.48 398.36710189.45399.396210215.72 399.428 10221.3400.052410300.92400.3749
#Mann= 3 , 0 , 0
 9699.09    0.04       0 9699.09    0.04       010300.92    0.04       0
#XS Ineff= 2 , 0
       0                               0
Bank Sta=9699.09,10300.92
Exp/Cntr=0.3,0.1

Type RM Length L Ch R = 1 ,19903.61,246.836900,246.836900,246.836900
XS GIS Cut Line= 6
  669741.0775794735843.943667574669485.818551609735631.033883536
669455.082877036  735614.8213695669346.706106784735575.020413851
669294.081135536735542.712813618669248.601767663  735507.8703201
#Sta/Elev= 30
9699.003402.77879706.993402.8045 9720.14402.32279728.185401.32349733.286 401.062
9774.399400.96949785.872400.70389812.165397.21829851.439395.29029942.504394.4587
9961.143392.9523 9968.48391.47349976.815382.77719981.467376.63689992.487370.3671
    9999370.021310007.26371.164710019.86376.780810024.92378.243910032.36379.8122
10043.67384.770910054.97390.748210066.27394.601210139.92394.9802 10172.7393.8394
10206.72394.343410230.48394.299610272.69395.779310292.79397.602410300.85397.4967
#Mann= 3 , 0 , 0
9699.003    0.04       09699.003    0.04       010300.85    0.04       0
#XS Ineff= 2 , 0
       0                               0
Bank Sta=9699.003,10300.85
Exp/Cntr=0.3,0.1

Type RM Length L Ch R = 1 ,19656.77,246.837000,246.837000,246.837000
XS GIS Cut Line= 6
669735.245627429735575.639357815669664.264684536735533.565612763
669597.370944727735503.018298268669474.353477633735475.427721343
669433.654888634735422.684633539669247.799601644735252.497486513
#Sta/Elev= 30
9699.267394.87459720.132393.46699746.051392.46889757.676391.00249780.926386.3815
9814.379381.36139824.252380.36449857.834379.57069868.302378.94129889.237376.6638
 9910.05375.73219930.242374.05239940.338374.38229950.434372.9869 9960.53372.4533
9970.626373.68189982.475372.38089990.992369.3944    9999367.554110006.81367.0056
 10018.7386.430810032.24394.222910074.02394.373510090.27393.808110154.78393.9728
10195.17393.274210222.41393.948210238.88392.091510291.04393.343610300.93393.2034
#Mann= 3 , 0 , 0
9699.267  0.0477       09699.267  0.0477       010300.93  0.0477       0
#XS Ineff= 2 , 0
       0                               0
Bank Sta=9699.267,10300.93
Exp/Cntr=0.3,0.1

Type RM Length L Ch R = 1 ,19409.94,246.836900,246.836900,246.836900
XS GIS Cut Line= 6
669885.264379679735556.618524659669812.855785032735497.433774957
669755.694968758735442.787760207669653.429879435735320.265769909
669578.667059648735222.754698979669478.953950608735115.270778006
#Sta/Elev= 30
9699.048393.53149717.406393.91959733.207 393.7649789.797390.81819811.032390.3124
9825.882390.64099840.495391.65489844.166391.57349854.532390.49549868.569 388.283
9881.932382.24329895.103 379.8419903.474378.76069921.146377.2215 9971.22376.6109
9980.104374.86659984.089 373.5149997.815364.54359999.516364.257510011.48366.2186
10014.26  367.3510025.02373.311310038.06385.751910045.28 388.42710050.66389.2156
10061.72389.026610111.02386.5865 10277.8385.798810287.44386.124310300.94387.5752
#Mann= 3 , 0 , 0
9699.048  0.0478       09699.048  0.0478       010300.94  0.0478       0
#XS Ineff= 2 , 0
       0                               0
Bank Sta=9699.048,10300.94
Exp/Cntr=0.3,0.1

Type RM Length L Ch R = 1 , 19163.1,246.837000,246.837000,246.837000
XS GIS Cut Line= 6
670074.726674948735310.381780674669883.419122853735186.447857202
669843.282406278735177.500477093 669757.17509622735181.376215795
669698.842294784735163.870069401669549.592929684735055.655411515
#Sta/Elev= 30
9699.106388.24799710.877 388.1099744.174387.02659779.686386.90449797.442386.4646
9879.873387.39839903.258386.85299956.785387.00299966.855384.81829976.883375.1514
9986.902364.68329996.922360.309510006.97362.349510017.01368.664410037.07379.9089
10047.08382.527810057.13382.791910077.61382.759810087.85383.253810098.62383.1475
10109.38383.835610131.78 383.87710143.18383.5843 10154.8384.2526 10190.5383.4892
10203.47383.722610267.53383.542410270.98383.593910293.77385.445710300.86385.5287
#Mann= 3 , 0 , 0
9699.106  0.0572       09699.106  0.0572       010300.86  0.0572       0
#XS Ineff= 2 , 0
       0                               0
Bank Sta=9699.106,10300.86
Exp/Cntr=0.3,0.1

Type RM Length L Ch R = 1 ,18916.26,246.837000,246.837000,246.837000
XS GIS Cut Line= 6
670216.312067038735222.308759328670068.765661257 735131.87608145
670004.241528928  735088.7334856669938.347936507735035.393569695
669856.257974931 734963.71809297669729.776310421734869.866645135
#Sta/Elev= 30
 9699.03390.21169713.016387.74229759.213388.11459770.942387.66419794.399385.1211
9827.834 385.2179853.044 386.7599888.644386.74689936.761 385.8559948.791382.3076
9961.456373.29289971.933367.71499988.119361.14349999.625358.394510004.08359.1202
10012.71362.951510025.79370.849710035.09375.546310038.94376.522610052.21375.5443
10078.76 375.34710092.04377.159310141.52378.079910174.88376.1796 10207.3377.3564
10219.75378.784110242.01379.333110275.57378.222610292.35375.684510300.97372.7583
#Mann= 3 , 0 , 0
 9699.03  0.0457       0 9699.03  0.0457       010300.97  0.0457       0
#XS Ineff= 2 , 0
       0                10153.05       0
Bank Sta=9699.03,10300.97
Exp/Cntr=0.3,0.1

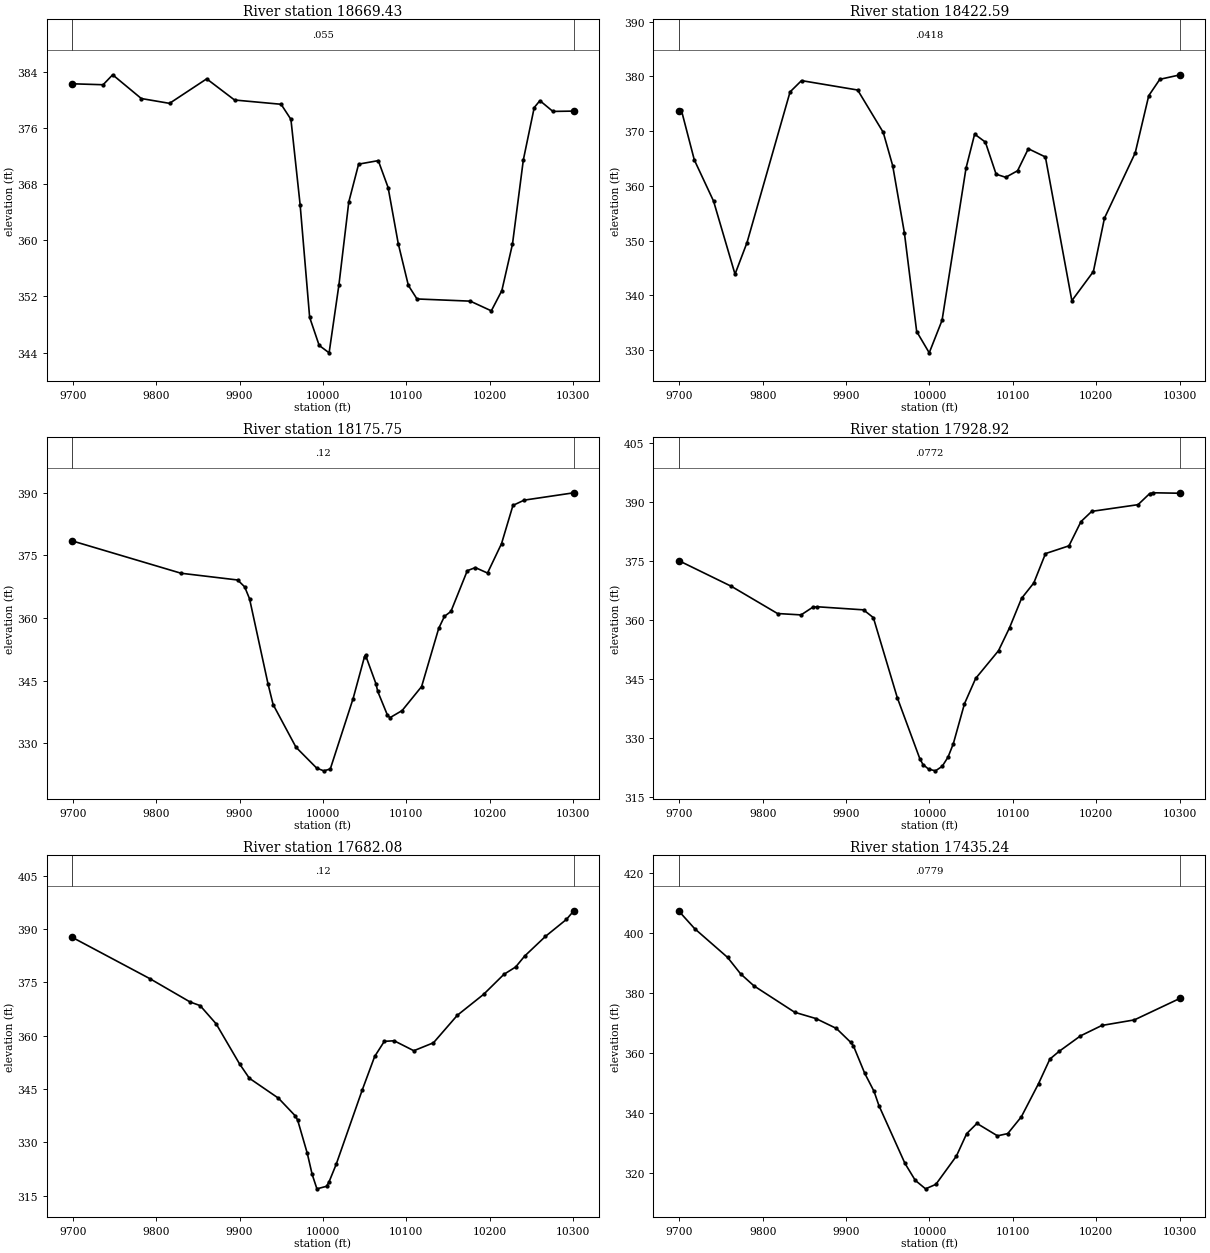
Type RM Length L Ch R = 1 ,18669.43,246.836900,246.836900,246.836900
XS GIS Cut Line= 6
670247.503082382734956.127075817 670161.75344924734908.180898036
670029.076352376 734842.92876585669981.888448098734816.936273186
669865.639390366734740.638228493669738.530334183734638.863974272
#Sta/Elev= 30
9699.028382.30699736.267  382.179747.724  383.599782.095380.20389815.942379.5158
9860.518383.0106 9893.95 379.9939949.781379.3852 9961.56377.23529972.614 365.058
9984.031349.01239995.448345.012910007.38343.952710019.18  353.6710030.98365.4589
10042.77370.851110066.37371.352610078.16367.5132 10090.3359.529510102.45353.5616
 10112.8351.633710176.74351.321410201.96349.939710214.56352.815410227.36359.4642
10240.39371.469410253.43378.917910260.24379.900610275.83378.366810300.98378.4139
#Mann= 3 , 0 , 0
9699.028   0.055       09699.028   0.055       010300.98   0.055       0
#XS Ineff= 2 , 0
       0                10060.68       0
Bank Sta=9699.028,10300.98
Exp/Cntr=0.3,0.1

Type RM Length L Ch R = 1 ,18422.59,246.837000,246.837000,246.837000
XS GIS Cut Line= 6
670397.623460531734876.927475253670297.229871013734793.254614131
670192.894102708734690.590839661670161.196356493734662.984968394
 670064.84301833734544.251491429669979.380483849734446.476237939
#Sta/Elev= 30
9699.026373.72239702.404373.84819717.962364.73659741.029357.21919766.779343.8677
9781.182 349.6479832.796377.16019846.533379.22779913.885 377.5089944.589369.7663
9955.937363.67439969.955351.41429984.689333.39249999.748329.500810015.14335.4482
10043.88 363.24310054.21369.449310067.09367.995310079.97362.132210091.49361.5636
10105.73362.764110118.61366.781310139.09365.278310170.83339.025810196.65344.3526
10209.93354.099910246.82366.022810263.06376.476110276.34379.461910300.94380.2921
#Mann= 3 , 0 , 0
9699.026  0.0418       09699.026  0.0418       010300.94  0.0418       0
#XS Ineff= 2 , 0
       0                10092.61       0
Bank Sta=9699.026,10300.94
Exp/Cntr=0.3,0.1

Type RM Length L Ch R = 1 ,18175.75,246.836900,246.836900,246.836900
XS GIS Cut Line= 6
670564.924316817734711.894952297670469.400943037734622.675975133
670395.288416934734549.692461444670350.559119299734502.165806133
670349.212317071734500.687251515670144.219449929  734281.6539842
#Sta/Elev= 30
9699.011378.4667 9829.72370.71419897.667369.0962 9906.07367.45129911.919364.6039
9934.156 344.1629940.179339.27619967.644329.0478 9992.52324.0408   10001323.3938
10008.79323.836410036.18340.704410049.88350.758210051.07351.083310063.57344.2548
 10065.7342.424510077.27336.772310080.34336.120510094.97337.828310118.36343.5824
10138.87357.514310145.75360.386910153.51361.561510173.15371.318310182.78372.0685
10197.41370.760310214.24377.808610227.93386.958110241.32388.2146   10301389.9814
#Mann= 3 , 0 , 0
9699.011    0.12       09699.011    0.12       0   10301    0.12       0
#XS Ineff= 2 , 0
       0                 10047.5       0
Bank Sta=9699.011,10301
Exp/Cntr=0.3,0.1

Type RM Length L Ch R = 1 ,17928.92,246.837000,246.837000,246.837000
XS GIS Cut Line= 6
670730.637943652734531.021549076670652.296343224734448.506909379
670595.006739981734391.105224308670471.323540101 734279.74092925
670422.383359796 734233.16678176670302.369104633734108.440437115
#Sta/Elev= 30
9699.019375.10169762.479368.53449817.754 361.6279846.011 361.2769860.139363.2395
9865.596 363.3439920.922362.56179932.733360.58059961.444  340.239988.458324.7232
9992.236323.2405    9999322.066110007.24321.628710015.29322.773110022.29 325.112
10028.67328.525710042.04338.692310055.42345.113910082.87352.178510096.22358.0678
10110.48365.465610125.23369.409410139.23376.863110167.39378.838910181.81385.0025
10194.74387.602610250.25389.303110264.12392.106210268.34392.326910300.98392.2083
#Mann= 3 , 0 , 0
9699.019  0.0772       09699.019  0.0772       010300.98  0.0772       0
#XS Ineff= 2 , 0
       0                               0
Bank Sta=9699.019,10300.98
Exp/Cntr=0.3,0.1

Type RM Length L Ch R = 1 ,17682.08,246.836900,246.836900,246.836900
XS GIS Cut Line= 6
670873.366252872734420.201613904670816.751831552734343.508162894
670773.797140022734279.039183118670672.144336289734105.678474206
670628.582224265734036.091996164670542.862490159733917.835774978
#Sta/Elev= 30
 9699.02387.64349792.492375.98579840.619369.44839852.635368.42799871.815363.3167
9899.947352.0411 9911.65348.0148 9946.65342.39149966.929337.39289969.699336.1848
9981.224326.86719987.047320.96659992.748316.912110004.27317.625510007.14318.7806
10015.82323.777210047.11344.699610062.03354.131210073.59 358.38110085.39358.5409
10108.99355.744610132.58357.978310161.19365.711110192.69371.590310217.01377.2043
 10231.2379.293810241.81382.3203 10266.9387.888210291.99392.649210300.98395.0894
#Mann= 3 , 0 , 0
 9699.02    0.12       0 9699.02    0.12       010300.98    0.12       0
#XS Ineff= 2 , 0
       0                               0
Bank Sta=9699.02,10300.98
Exp/Cntr=0.3,0.1

Type RM Length L Ch R = 1 ,17435.24,246.837000,246.837000,246.837000
XS GIS Cut Line= 6
671112.462273561734300.011683827671059.886367579734236.396451136
671009.382470268734171.409979078670838.939258229733935.524163746
670794.269130502733879.931950212670745.601138141733823.157417621
#Sta/Elev= 30
9699.015407.5052 9718.49401.5047 9757.82391.95669773.518386.44369789.508 382.445
9838.397373.63559863.848371.54379888.328368.25529905.349363.66389908.843362.4152
 9922.37353.27419933.558347.2423 9939.39342.51469970.631323.21619982.989317.5613
9995.347314.724310007.72316.222210032.36325.656610044.67333.139410056.99336.5522
10081.62332.408610093.94333.161110110.22 338.74210130.88349.831210144.49358.0241
10155.54360.5946 10181.2365.762810206.86369.244710245.85371.095810300.97378.3333
#Mann= 3 , 0 , 0
9699.015  0.0779       09699.015  0.0779       010300.97  0.0779       0
#XS Ineff= 2 , 0
       0                               0
Bank Sta=9699.015,10300.97
Exp/Cntr=0.3,0.1

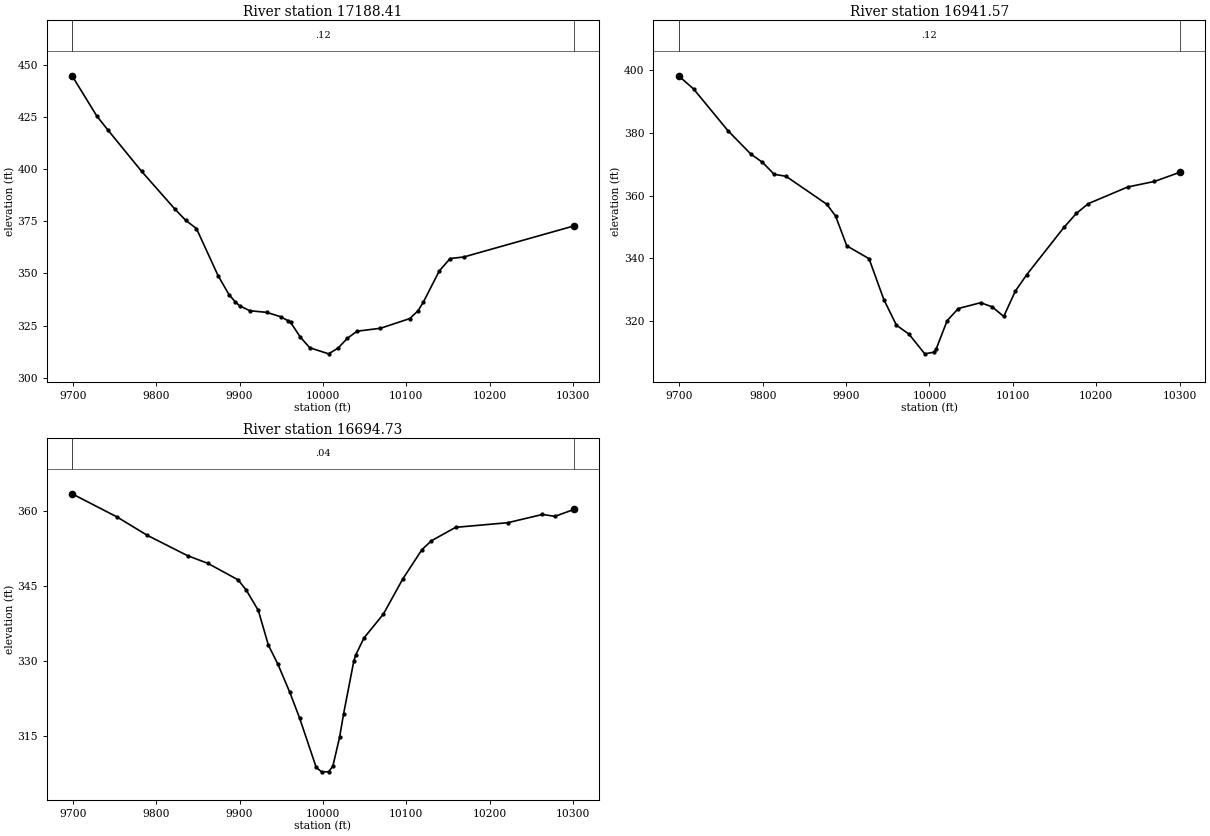
Type RM Length L Ch R = 1 ,17188.41,246.837000,246.837000,246.837000
XS GIS Cut Line= 6
671317.064488324734055.188465042671169.244303674733927.076786632
671117.375637287733889.955413705671047.573358078733852.274160354
670998.732629235733819.718906407670841.893584141733688.709803203
#Sta/Elev= 30
9699.065444.7505 9728.77425.43539742.233418.66129782.622398.88039822.299380.8842
9835.287375.48419848.276371.50749874.253348.89089887.241339.86439894.717336.4196
9899.936334.49789912.233 332.123 9932.65331.32619949.125329.26139958.501327.2452
9961.214326.53839972.635 319.6019984.055314.386510006.79311.450910018.11314.1998
10029.42318.949310040.92322.310310068.97323.704110104.14328.356810114.02332.0971
10120.27336.144510139.51351.180110152.54357.155410168.68357.859910300.94372.7735
#Mann= 3 , 0 , 0
9699.065    0.12       09699.065    0.12       010300.94    0.12       0
#XS Ineff= 2 , 0
       0                               0
Bank Sta=9699.065,10300.94
Exp/Cntr=0.3,0.1

Type RM Length L Ch R = 1 ,16941.57,246.836900,246.836900,246.836900
XS GIS Cut Line= 6
671458.279576842733906.481857333671330.437380803733782.937757456
671208.549920728733645.795719031671169.609216353733605.156005893
671103.739276722733545.018094123671029.429621311733485.593640464
#Sta/Elev= 30
9699.039398.16249717.227393.93219758.317380.66759785.709373.24689799.689370.6014
 9813.83 366.7799827.971366.15179876.846357.24769887.456353.47649900.823  344.01
9927.555339.90379945.324326.86879960.395  318.739975.465315.88139994.388   309.6
10005.49310.125910007.86310.985710021.24 320.16410034.63324.030610061.43325.8947
10075.28 324.56410089.13321.502510102.98329.550210116.84334.860710161.34349.8687
10176.17354.310110190.56357.442210237.86362.742110269.88364.512410300.95367.4786
#Mann= 3 , 0 , 0
9699.039    0.12       09699.039    0.12       010300.95    0.12       0
#XS Ineff= 2 , 0
       0                10050.86       0
Bank Sta=9699.039,10300.95
Exp/Cntr=0.3,0.1

Type RM Length L Ch R = 1 ,16694.73,246.837000,246.837000,246.837000
XS GIS Cut Line= 6
671669.337486831733693.147784554 671465.64784092733553.660456678
671437.134178296733531.803751019671408.950001556733506.209897414
671384.338163751733488.848318125671165.021772374733366.913711814
#Sta/Elev= 30
 9699.02363.51589752.757358.88829789.117355.20619837.597351.11359861.837 349.583
9898.198346.26839908.125 344.1799922.438 340.1429934.558333.17459945.893329.3798
9960.128323.76959971.909 318.6099991.887308.70099998.281307.807110006.68  307.82
10011.79308.901310019.89314.694710024.73319.420410036.97329.972110039.34331.2428
 10049.2334.631510072.44339.400810095.63346.420110118.61352.2928   10130354.0896
10159.12356.792410221.62357.719810263.29359.370110278.19 358.99710300.97360.3675
#Mann= 3 , 0 , 0
 9699.02    0.04       0 9699.02    0.04       010300.97    0.04       0
#XS Ineff= 2 , 0
       0                               0
Bank Sta=9699.02,10300.97
Exp/Cntr=0.3,0.1