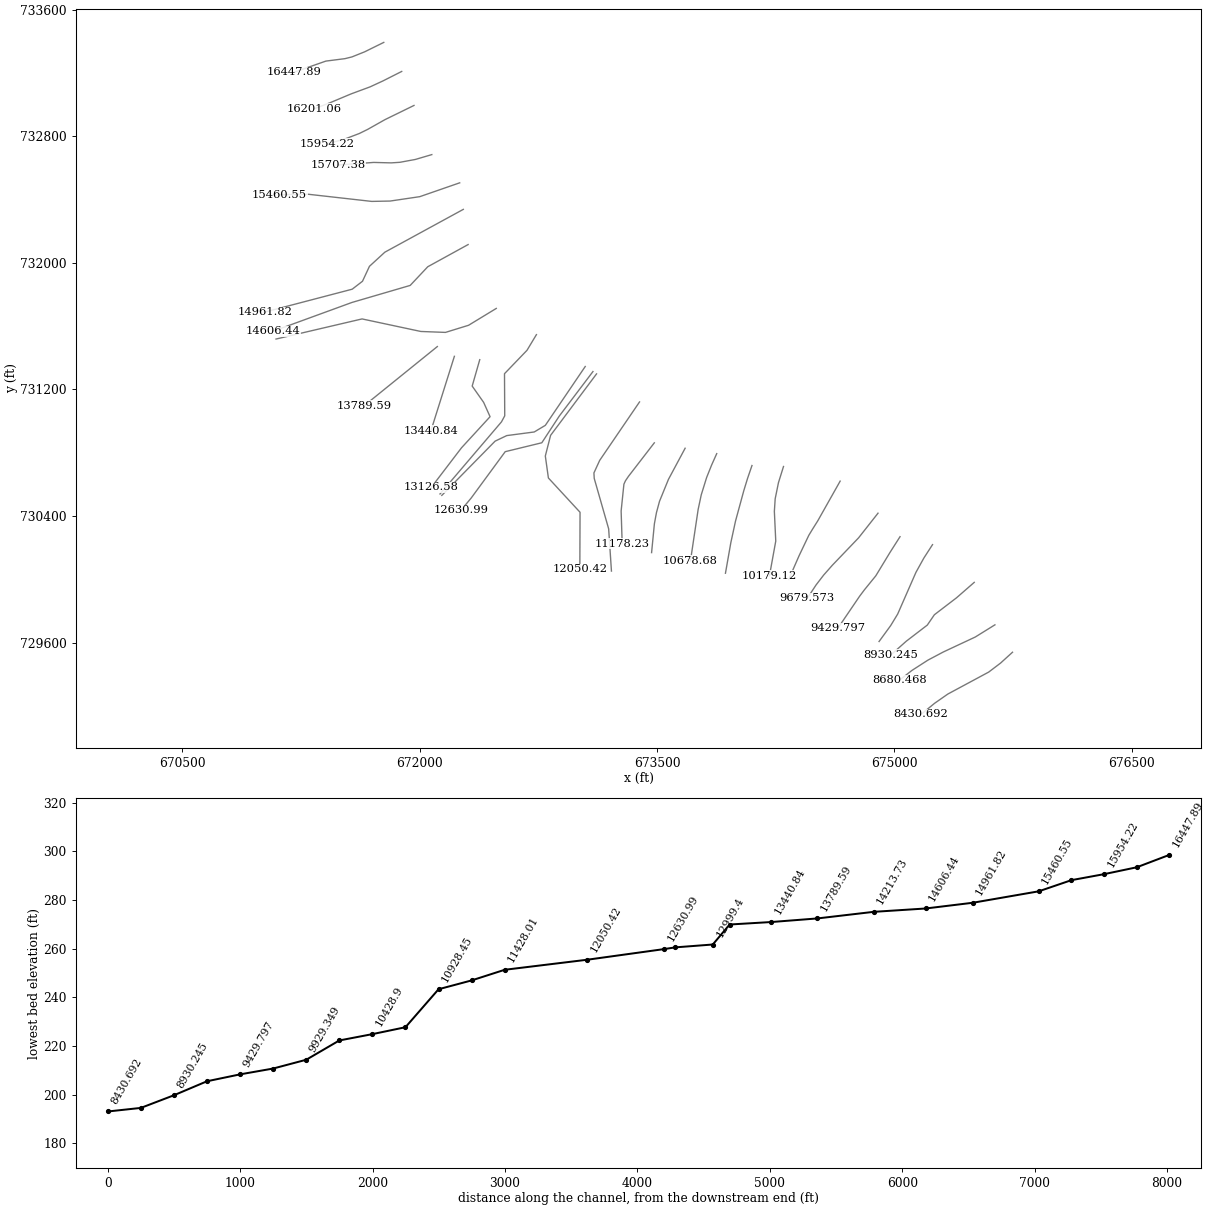
HEC-RAS study 4078_ras.prj: 4078

--- 4078_ras.g01 (geometry) --- (continued)

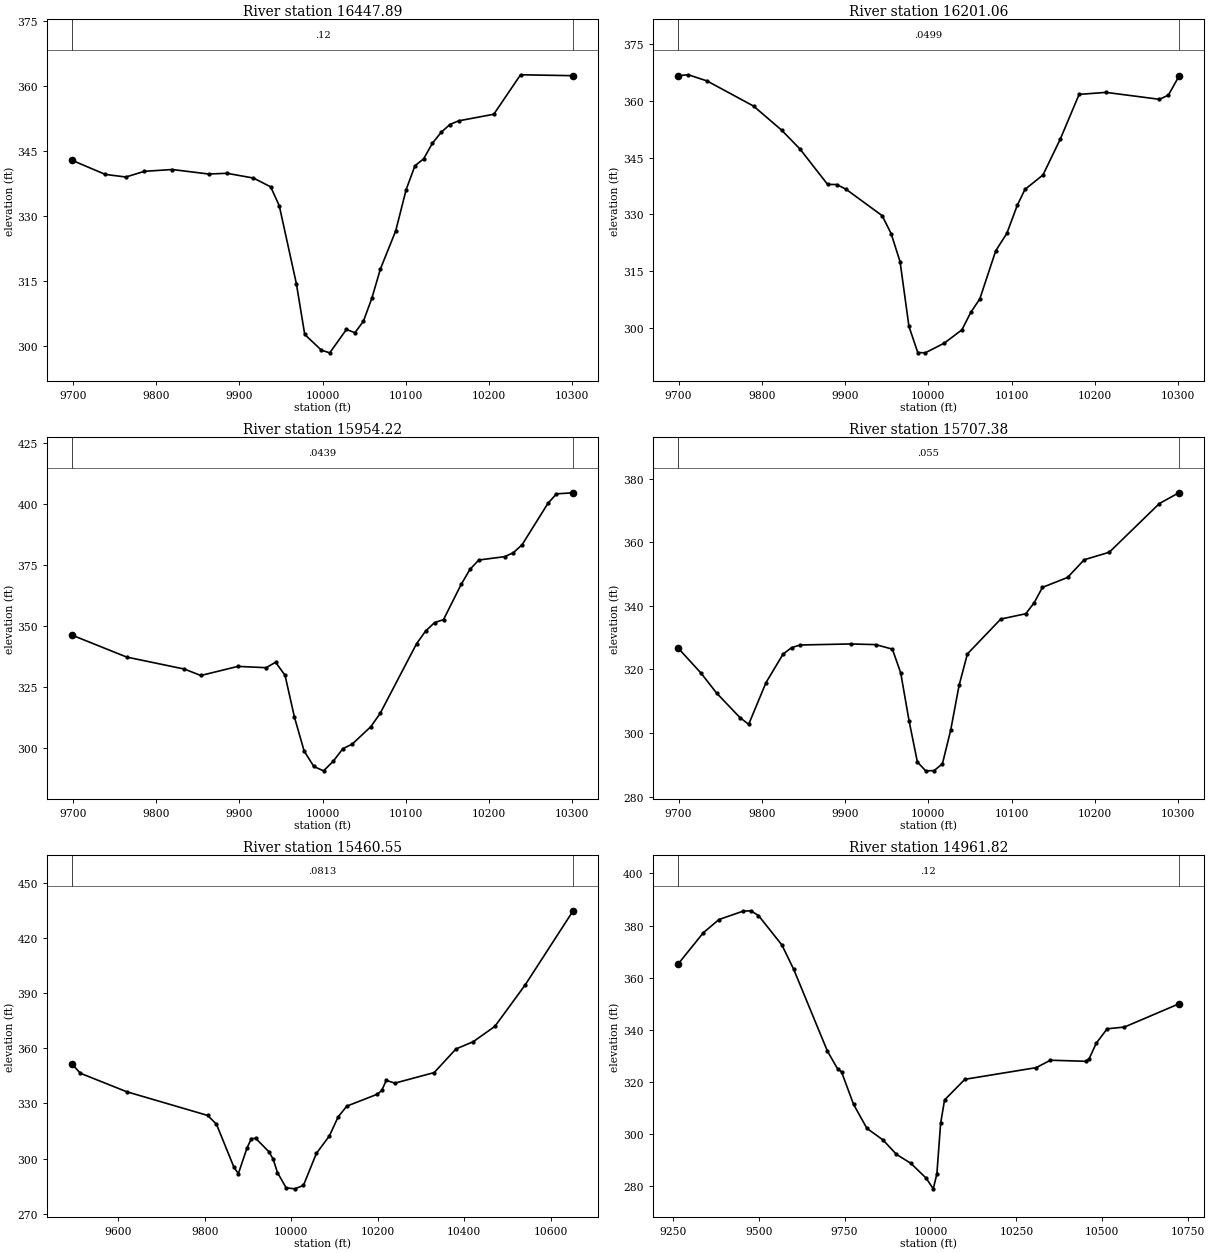
Type RM Length L Ch R = 1 ,16447.89,246.836900,246.836900,246.836900
XS GIS Cut Line= 6
671772.968598041733392.635008237671652.346726626733333.223624551
671572.066131569733301.001061848671527.976304497733290.028980442
671407.017056422733274.513143159671206.004318437733204.074050609
#Sta/Elev= 30
9699.114342.90549739.025339.65089763.732339.05379786.027340.36239819.468340.7796
9863.323339.74019885.055339.91179916.988338.81129937.698 336.7829948.003332.4125
9968.529 314.4649978.555302.74919998.606299.116110008.62298.508810028.65303.9116
10038.81303.139410049.02305.787410059.23311.135810069.44317.844710087.81326.6261
10100.41336.169610110.89341.630910121.37343.249610131.86346.820810142.34349.3448
10152.83351.151210163.31351.999310205.63353.524510237.74362.6252 10300.9362.4168
#Mann= 3 , 0 , 0
9699.114    0.12       09699.114    0.12       0 10300.9    0.12       0
#XS Ineff= 2 , 0
       0                10032.09       0
Bank Sta=9699.114,10300.9
Exp/Cntr=0.3,0.1

Type RM Length L Ch R = 1 ,16201.06,246.837000,246.837000,246.837000
XS GIS Cut Line= 6
671886.355848813733209.162268479671767.656834514733149.161154942
671686.789294907733111.798404757671565.919442173 733067.00997649
671430.761792393733010.258600487671333.241638163732973.095006473
#Sta/Elev= 30
9699.019366.63319711.744366.86969734.154365.24819790.179358.58719823.794352.2413
9845.964 347.2329879.011337.90749890.027337.86789901.043336.64679944.571329.6453
9955.342324.90759966.112317.46589976.749 300.4049987.342293.48849996.338293.4012
10019.15295.961110040.39299.479610051.03304.091210061.87 307.64510081.05320.3757
10094.41324.987510106.88332.3761 10116.1336.568310137.79340.408710158.54349.8663
10181.18361.686110213.49362.2194 10277.7360.3875 10288.4361.492310300.98366.4268
#Mann= 3 , 0 , 0
9699.019  0.0499       09699.019  0.0499       010300.98  0.0499       0
#XS Ineff= 2 , 0
       0                               0
Bank Sta=9699.019,10300.98
Exp/Cntr=0.3,0.1

Type RM Length L Ch R = 1 ,15954.22,246.836900,246.836900,246.836900
XS GIS Cut Line= 6
671963.980041461 732994.26482858 671780.18203484732904.384297938
671671.273074222732842.971386174671618.155790157732816.881442261
671525.378398532732781.498398819671415.563194345732751.843199924
#Sta/Elev= 30
9699.013346.26459764.668337.2576 9833.92332.34349853.721329.70339898.248333.4385
 9932.17332.90119943.511335.13679954.852329.81869966.211  312.579977.851298.6779
9989.491292.358110001.17290.575210012.76294.504610024.35299.677210035.66301.5639
10057.94308.706610069.09314.127410112.89342.7517 10123.7347.924710134.52351.4084
10145.24352.626310166.41367.0484   10177373.239410187.58377.085410218.82378.4743
10229.24 380.11410239.65 383.34910270.65400.320310280.94404.240110300.96404.6832
#Mann= 3 , 0 , 0
9699.013  0.0439       09699.013  0.0439       010300.96  0.0439       0
#XS Ineff= 2 , 0
       0                               0
Bank Sta=9699.013,10300.96
Exp/Cntr=0.3,0.1

Type RM Length L Ch R = 1 ,15707.38,246.837000,246.837000,246.837000
XS GIS Cut Line= 6
672076.601965621732683.637706277671973.027397028732653.108057742
671874.575223061732634.910879946 671819.50808574732631.386212908
671709.223357832732634.180136755671481.627839367732617.577981136
#Sta/Elev= 30
9699.062326.85749727.239318.78479745.623312.60229773.913304.82539784.283302.7475
9805.022 315.8269825.523324.8152 9835.76326.85249845.997327.69439906.804328.0219
 9936.87327.81569956.911326.38419966.925318.86359976.932303.83229986.938290.8595
9996.945 288.10510006.96288.166710016.98290.310510026.99300.9849   10037314.9765
   10047  324.8810087.04335.845610117.12337.525810127.15340.962910137.18345.8243
10167.26348.930310187.31354.513310217.39356.861710277.55372.181910300.98375.5771
#Mann= 3 , 0 , 0
9699.062   0.055       09699.062   0.055       010300.98   0.055       0
#XS Ineff= 2 , 0
       0  9893.5                       0
Bank Sta=9699.062,10300.98
Exp/Cntr=0.3,0.1

Type RM Length L Ch R = 1 ,15460.55,498.727300,498.727300,498.727300
XS GIS Cut Line= 6
672252.754932349732505.307600755672000.725306001732417.917902795
671813.328156707732390.153591871671697.154253468732387.848647294
671293.594317045732433.296859174671114.247860614732430.259402176
#Sta/Elev= 30
9493.305351.3469  9512.5346.36339619.731 336.2999806.927 323.422 9827.31318.6436
 9867.85295.16919877.934291.79139898.085305.86019908.125310.85979918.165310.9448
9948.286303.74269958.308  299.759968.327292.36979988.364284.091210008.39283.5208
 10028.4285.3879 10058.4302.805910088.53312.325110108.65322.644610128.77328.4842
10199.56334.985910209.67337.060910219.79342.471910240.01340.9832 10330.8346.7255
10381.06359.549210421.13363.513810471.21371.868810541.22394.388710652.05434.6652
#Mann= 3 , 0 , 0
9493.305  0.0813       09493.305  0.0813       010652.05  0.0813       0
#XS Ineff= 2 , 0
       09943.812                       0
Bank Sta=9493.305,10652.05
Exp/Cntr=0.3,0.1

Type RM Length L Ch R = 1 ,14961.82,355.374600,355.374600,355.374600
XS GIS Cut Line= 6
672275.629444688732337.561176955671779.826860479732067.025007754
671682.494151859731977.705171984671638.531328086731883.283352978
671573.519146731731833.133647266671020.562949099731688.305622939
#Sta/Elev= 30
9264.599365.03749338.878377.20159384.501382.31149454.567385.51229477.064385.6724
 9499.56383.8505 9567.58372.54959601.945363.20379700.143 331.741 9729.53324.9803
9741.147323.7921 9776.28311.26259815.049302.05469861.856297.60879901.006292.0741
9943.394288.57339987.675282.897710008.18278.812810018.74284.606610029.61303.9827
10041.07312.971510100.09320.900510307.95325.3921   10349328.243710451.54327.8303
 10461.8328.7809 10482.3334.741410514.22340.321410564.34340.978810722.83 349.898
#Mann= 3 , 0 , 0
9264.599    0.12       09264.599    0.12       010722.83    0.12       0
#XS Ineff= 2 , 0
       0                               0
Bank Sta=9264.599,10722.83
Exp/Cntr=0.3,0.1

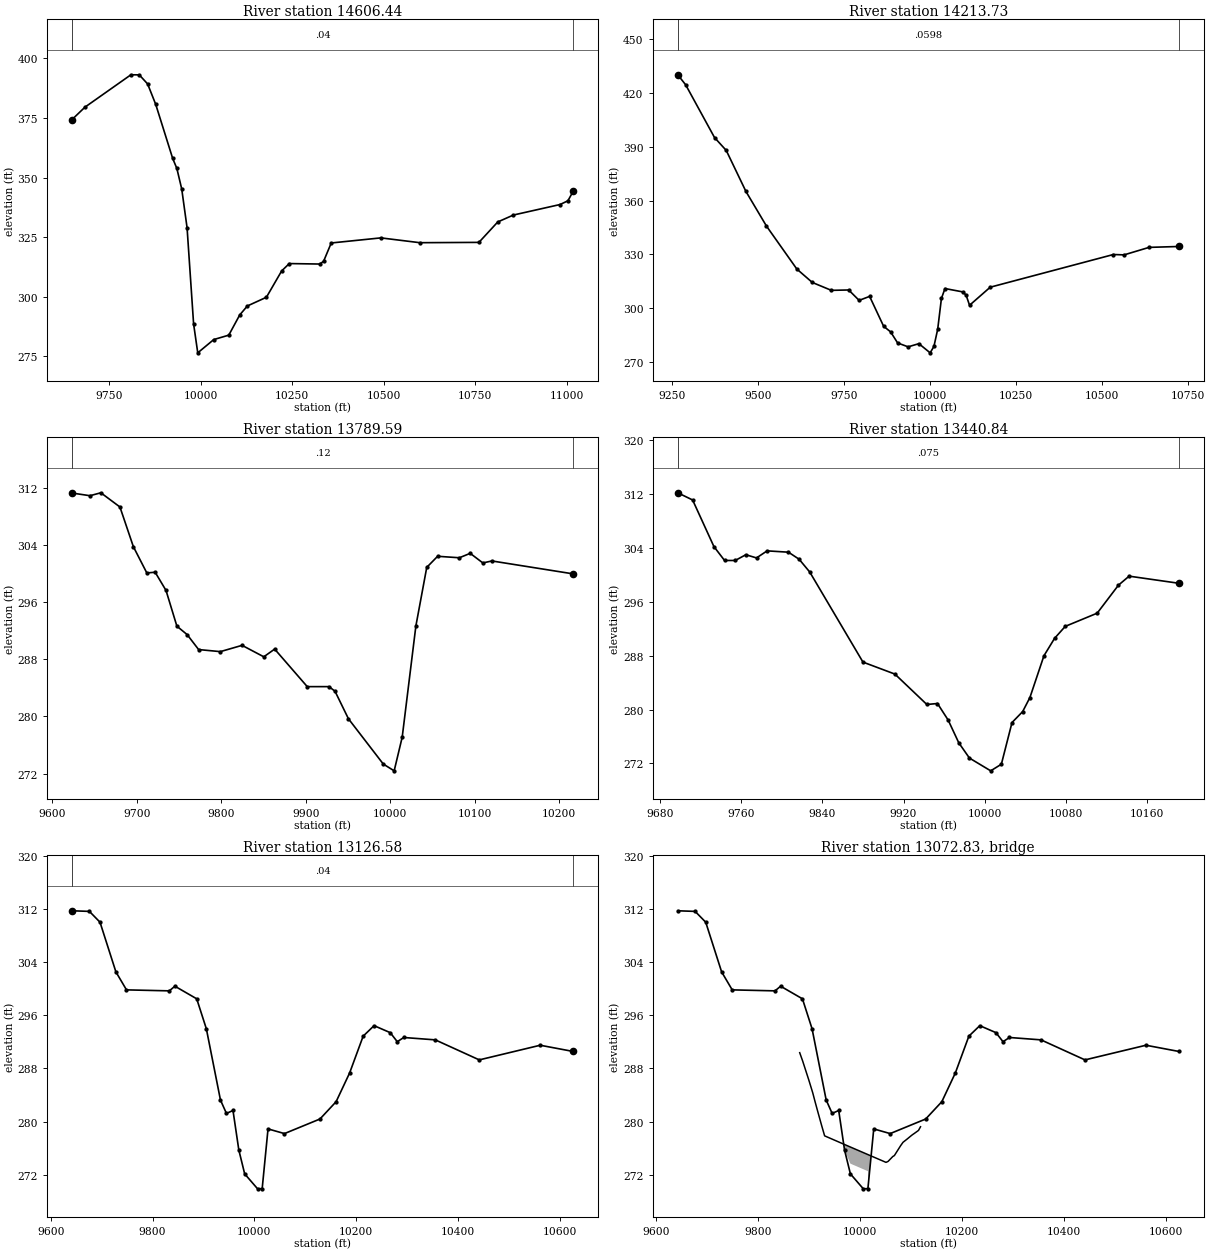
Type RM Length L Ch R = 1 ,14606.44,392.716400,392.716400,392.716400
XS GIS Cut Line= 5
672305.960757737 732115.13154796672051.037500709731975.026272655
671939.926389635731856.970717117671571.870834053731749.331828207
671071.540932047 731566.74274054
#Sta/Elev= 30
9648.947 374.3159684.275379.51959809.794393.09719832.615393.06159855.437389.2592
9877.602380.67879923.902 358.0189935.312353.81439948.643345.18499963.234328.9569
9981.067288.60629992.415276.463810036.19 282.03610077.19283.881410107.09292.3576
10127.92296.119610180.02299.779210221.69310.828310242.53313.910110325.88313.7095
 10336.3314.894610357.14322.547510492.74324.682410599.19322.663910760.59322.7946
10812.09 331.36710854.67334.260810982.41338.6796 11003.7340.242311018.03344.2035
#Mann= 3 , 0 , 0
9648.947    0.04       09648.947    0.04       011018.03    0.04       0
#XS Ineff= 2 , 0
       0                               0
Bank Sta=9648.947,11018.03
Exp/Cntr=0.3,0.1

Type RM Length L Ch R = 1 ,14213.73,424.138400,424.138400,424.138400
XS GIS Cut Line= 6
672483.910216982731711.600334257672308.758406031731605.101495802
672162.799878882731560.062074909672007.081930697731566.016339267
671635.795787868731645.259813922671091.946377993731518.083600213
#Sta/Elev= 30
9266.103430.14859289.047424.57989373.011395.13879407.104387.94859464.369365.0656
9524.095345.74979612.281321.81899657.213 314.3379712.624309.93579763.025310.1406
9793.381304.33899823.898306.56319864.586289.90559884.931286.76399905.275 280.603
9935.792278.42829967.097280.19769999.868275.083210010.87 278.67110021.81288.2627
10032.64305.4219   10043310.945310094.24309.081510104.32307.3028 10114.4301.6035
10174.47311.685210532.59329.912710563.64329.712710636.29333.896610722.93334.3931
#Mann= 3 , 0 , 0
9266.103  0.0598       09266.103  0.0598       010722.93  0.0598       0
#XS Ineff= 2 , 0
       0                               0
Bank Sta=9266.103,10722.93
Exp/Cntr=0.3,0.1

Type RM Length L Ch R = 1 ,13789.59,348.753200,348.753200,348.753200
XS GIS Cut Line= 2
672111.519615084731470.636443123671650.240116239731097.821505681
#Sta/Elev= 30
9623.301311.24329644.542310.87029657.399311.28029679.994309.29219695.903303.7364
9711.812300.06689721.688300.16499734.546297.61619747.404292.61939759.538291.4409
9773.119289.34829798.835 289.059 9824.55289.93759850.266288.33499863.124289.4129
9901.697284.16169927.412284.16289934.534283.52229950.443279.66549991.701273.3298
10004.56272.382610014.08277.094510030.27292.652610043.13300.845710055.99 302.396
10081.71  302.1910094.56302.808110109.53301.465110120.28301.7426 10216.4299.9368
#Mann= 3 , 0 , 0
9623.301    0.12       09623.301    0.12       0 10216.4    0.12       0
#XS Ineff= 2 , 0
       0                               0
Bank Sta=9623.301,10216.4
Exp/Cntr=0.3,0.1

Type RM Length L Ch R = 1 ,13440.84,314.256000,314.256000,314.256000
XS GIS Cut Line= 2
 672219.18390274731408.966436356   672070.932852730938.269350246
#Sta/Elev= 30
 9697.67312.20939712.313311.13839733.282304.21669743.766302.1517 9754.25302.1516
9764.734303.00629775.219302.53049785.703 303.5819806.672303.38269817.156302.3408
 9827.64300.43819880.061287.05479911.514285.27429942.967 280.7589953.451280.9023
9963.936 278.449 9974.42275.06339984.904272.798510005.87270.899210016.36271.8825
10026.84278.075110037.33279.702910044.47281.790110058.29 287.99510068.78290.5899
10079.26292.360210110.72294.322910131.68298.486510142.17299.822510191.16298.7644
#Mann= 3 , 0 , 0
 9697.67   0.075       0 9697.67   0.075       010191.16   0.075       0
#XS Ineff= 2 , 0
       0                               0
Bank Sta=9697.67,10191.16
Exp/Cntr=0.3,0.1

Type RM Length L Ch R = 1 ,13126.58,127.181600,127.181600,127.181600
XS GIS Cut Line= 6
672379.552927405 731387.81692186672331.705817997 731220.86105071
672403.985493928 731118.04066667672444.706438065731027.436565876
672264.264598221730830.893272057672073.895374566730581.540046528
#Sta/Elev= 30
9641.906311.74249676.044311.65029696.849310.02249728.057302.54559748.862299.8361
9832.982 299.6879843.952 300.3889886.804298.49089905.726293.97989933.451283.2529
9945.169281.23679958.054281.67759969.524275.72739980.993 272.13810006.43269.8836
 10015.4269.921610026.87278.905510059.16278.201510128.88280.395910160.61283.0033
10187.18287.333810213.76292.872210235.18294.447410266.91 293.39610280.74292.0325
10293.48292.667210355.39  292.3110441.79289.2952 10561.5291.500210626.19290.5651
#Mann= 3 , 0 , 0
9641.906    0.04       09641.906    0.04       010626.19    0.04       0
#XS Ineff= 2 , 0
       0                               0
Bank Sta=9641.906,10626.19
Exp/Cntr=0.3,0.1

Type RM Length L Ch R = 3 ,13072.83,,,
BEGIN DESCRIPTION:
END DESCRIPTION:
Bridge Culvert--1,0,-1,-1, 0
Deck Dist Width WeirC Skew NumUp NumDn MinLoCord MaxHiCord MaxSubmerge Is_Ogee
52.090800,23.000000,2.6,0, 26, 26, , , 0.95, 0, 0,0,,
 9881.44 9887.31 9899.13 9900.07 9907.07 9911.38 9916.71 9924.55 9930.39 9969.75
 9969.7510015.7510015.7510050.9310054.9710064.3210067.3610067.4410079.7510084.37
10092.1510101.3010104.5410106.2910114.8110118.73
  290.38  289.11  286.31  286.08  284.33  283.07  281.57  279.41  277.86  276.55
  276.55  275.03  275.03  273.87  274.01  274.75  274.89  274.90  276.39  276.89
  277.36  277.94  278.12  278.21  278.68  279.23
 -709.62 -710.89 -713.69 -713.92 -715.67 -716.93 -718.43 -720.59 -722.14 -723.45
  274.05  272.53 -724.97 -726.13 -725.99 -725.25 -725.11 -725.10 -723.61 -723.11
 -722.64 -722.06 -721.88 -721.79 -721.32 -720.77
 9881.44 9887.31 9899.13 9900.07 9907.07 9911.38 9916.71 9924.55 9930.39 9986.38
 9986.3810032.3810032.3810050.9310054.9710064.3210067.3610067.4410079.7510084.37
10092.1510101.3010104.5410106.2910114.8110118.73
  290.38  289.11  286.31  286.08  284.33  283.07  281.57  279.41  277.86  276.00
  276.00  274.48  274.48  273.87  274.01  274.75  274.89  274.90  276.39  276.89
  277.36  277.94  278.12  278.21  278.68  279.23
 -709.62 -710.89 -713.69 -713.92 -715.67 -716.93 -718.43 -720.59 -722.14 -724.00
  273.50  271.98 -725.52 -726.13 -725.99 -725.25 -725.11 -725.10 -723.61 -723.11
 -722.64 -722.06 -721.88 -721.79 -721.32 -720.77
BR Coef=-1 , 0 , 0 ,, 0 ,,,0.8,0,1,0,
WSPro=,,,, 1 ,,,, 0 ,,,, 0 ,,,,-1 ,-1 ,-1 , 0 , 0 , 0 , 0 , 0
BC Design=,, 0 ,, 0 ,,,,,,

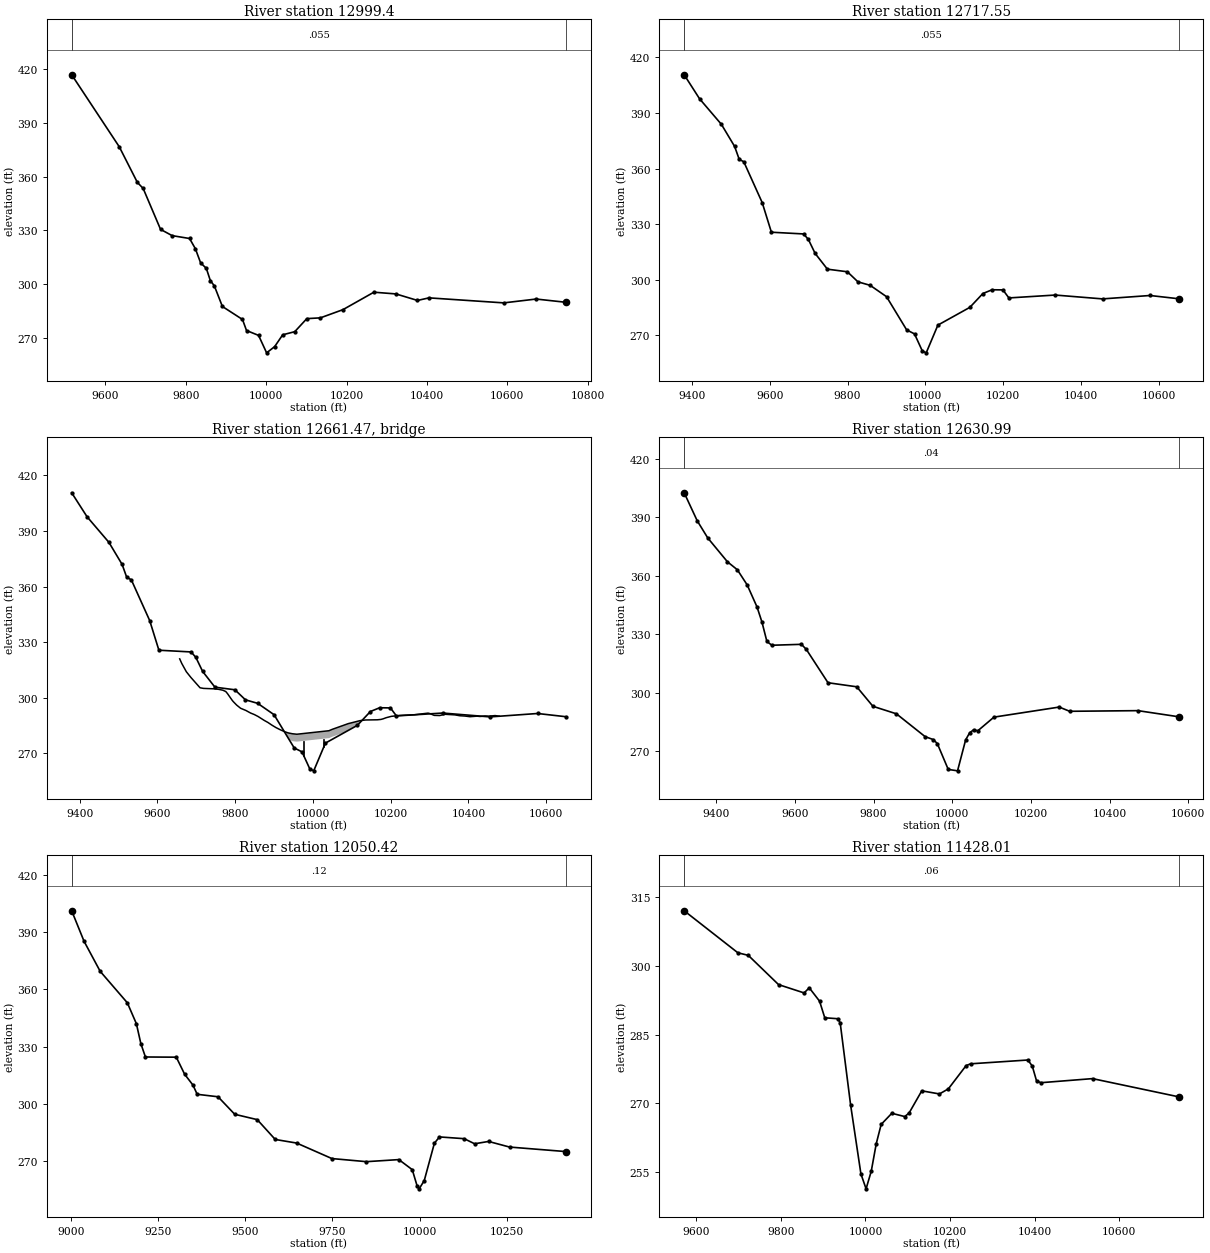
Type RM Length L Ch R = 1 , 12999.4,281.852700,281.852700,281.852700
XS GIS Cut Line= 6
672737.627804635731545.979131199672678.017092556731446.910987273
672535.893733263731299.102693588672537.362677664731032.883890271
672516.642372459730994.544365779672128.336159547 730539.00818325
#Sta/Elev= 30
9516.258416.75859634.602376.59229679.587356.72819694.015353.36599737.298 330.528
9766.154327.03499809.437  325.449823.865319.76219837.003311.83399851.106308.8009
9861.106301.98329871.106299.00719891.106287.52299941.106 280.2759951.106274.1186
9981.107271.392510001.11261.663710021.11265.134310041.11271.723810071.11273.4653
10101.11280.741510134.87281.176210191.02285.752310267.97295.483610322.71294.5229
10376.37290.888910405.05292.324310591.05289.529410671.56291.670510745.95 289.851
#Mann= 3 , 0 , 0
9516.258   0.055       09516.258   0.055       010745.95   0.055       0
#XS Ineff= 2 , 0
       0                               0
Bank Sta=9516.258,10745.95
Exp/Cntr=0.3,0.1

Type RM Length L Ch R = 1 ,12717.55,86.558500,86.558500,86.558500
XS GIS Cut Line= 6
673046.066501389731344.637204142672793.958176774 730972.75425215
672723.784828973730930.849879268672550.045525597730907.994016526
672476.429942555730872.863193705672139.732085791730530.105115872
#Sta/Elev= 30
9379.749410.59899419.214397.66099475.414383.84949509.404371.9265 9521.23364.9723
9533.056 363.6289580.359341.59799604.011325.60569686.823324.67649699.068321.7168
 9716.47314.16029748.044305.66129799.396304.25449826.605298.81769857.951296.9386
9900.037290.81679951.895272.86549972.047270.72319992.092261.513410002.11260.4939
10032.15275.4624 10114.3285.042510147.91292.5249 10171.6 294.54610199.37294.4681
10214.73290.136710333.87291.688910455.58289.616210577.65291.449310650.97289.7023
#Mann= 3 , 0 , 0
9379.749   0.055       09379.749   0.055       010650.97   0.055       0
#XS Ineff= 2 , 0
       0                               0
Bank Sta=9379.749,10650.97
Exp/Cntr=0.3,0.1

Type RM Length L Ch R = 3 ,12661.47,,,
BEGIN DESCRIPTION:
END DESCRIPTION:
Bridge Culvert--1,0,-1,-1, 0
Deck Dist Width WeirC Skew NumUp NumDn MinLoCord MaxHiCord MaxSubmerge Is_Ogee
32.729250,21.100000,2.6,0, 60, 60, , , 0.95, 0, 0,0,,
 9657.48 9662.83 9674.58 9686.32 9709.80 9718.71 9745.03 9756.87 9768.51 9775.95
 9780.25 9791.99 9795.03 9803.74 9814.11 9827.64 9839.85 9849.19 9858.87 9874.63
 9884.34 9894.76 9905.18 9915.60 9927.07 9927.07 9936.43 9939.36 9947.27 9958.74
10041.2910049.6010076.8710076.8710090.7410121.4810135.5310165.6910175.0610180.77
10188.4110201.7710222.7010261.5310296.1210300.3610311.8710313.3010326.2510339.19
10365.0810378.0210390.6310403.9110422.1310429.7910442.7410453.6310468.6210479.03
  320.94  318.45  313.98  310.90  305.33  305.00  304.77  304.52  304.02  303.30
  302.22  298.70  297.91  296.03  294.27  293.09  291.69  290.90  289.85  287.75
  286.61  285.14  283.83  282.72  281.64  281.64  280.98  280.85  280.52  280.26
  282.15  282.89  284.93  284.93  285.97  287.61  287.95  288.05  288.25  288.58
  289.18  289.91  290.40  290.78  291.65  291.44  290.45  290.43  290.35  291.03
  290.70  290.23  290.08  289.72  290.01  289.84  290.12  290.02  290.33  290.00
 -679.06 -681.55 -686.02 -689.10 -694.67 -695.00 -695.23 -695.48 -695.98 -696.70
 -697.78 -701.30 -702.09 -703.97 -705.73 -706.91 -708.31 -709.10 -710.15 -712.25
 -713.39 -714.86 -716.17 -717.28 -718.36  277.64  276.98  276.85  276.52  276.26
  278.15  278.89  280.93 -715.07 -714.03 -712.39 -712.05 -711.95 -711.75 -711.42
 -710.82 -710.09 -709.60 -709.22 -708.35 -708.56 -709.55 -709.57 -709.65 -708.97
 -709.30 -709.77 -709.92 -710.28 -709.99 -710.16 -709.88 -709.98 -709.67 -710.00
 9657.48 9662.83 9674.58 9686.32 9709.80 9718.71 9745.03 9756.87 9768.51 9775.95
 9780.25 9791.99 9795.03 9803.74 9814.11 9816.49 9827.64 9839.85 9849.19 9858.87
 9874.63 9884.34 9894.76 9905.18 9925.67 9925.67 9936.43 9947.27 9958.7410041.29
10049.6010075.4710075.4710090.7410121.4810135.5310165.6910175.0610180.7710188.41
10201.7710222.7010261.5310274.4810296.1210300.3610311.8710313.3010326.2510339.19
10365.0810378.0210390.6310403.9110422.1310429.7910442.7410453.6310468.6210479.03
  320.94  318.45  313.98  310.90  305.33  305.00  304.77  304.52  304.02  303.30
  302.22  298.70  297.91  296.03  294.27  294.12  293.09  291.69  290.90  289.85
  287.75  286.61  285.14  283.83  281.75  281.75  280.98  280.52  280.26  282.15
  282.89  284.82  284.82  285.97  287.61  287.95  288.05  288.25  288.58  289.18
  289.91  290.40  290.78  291.16  291.65  291.44  290.45  290.43  290.35  291.03
  290.70  290.23  290.08  289.72  290.01  289.84  290.12  290.02  290.33  290.00
 -679.06 -681.55 -686.02 -689.10 -694.67 -695.00 -695.23 -695.48 -695.98 -696.70
 -697.78 -701.30 -702.09 -703.97 -705.73 -705.88 -706.91 -708.31 -709.10 -710.15
 -712.25 -713.39 -714.86 -716.17 -718.25  277.75  276.98  276.52  276.26  278.15
  278.89  280.82 -715.18 -714.03 -712.39 -712.05 -711.95 -711.75 -711.42 -710.82
 -710.09 -709.60 -709.22 -708.84 -708.35 -708.56 -709.55 -709.57 -709.65 -708.97
 -709.30 -709.77 -709.92 -710.28 -709.99 -710.16 -709.88 -709.98 -709.67 -710.00
Pier Skew, UpSta & Num, DnSta & Num=  ,9976.50, 2 ,9975.10, 2 , 0 , 0 , 0 ,,
    3.00    3.00
 -719.33  280.67
    3.00    3.00
 -719.36  280.64
Pier Skew, UpSta & Num, DnSta & Num=  ,10027.44, 2 ,10026.04, 2 , 0 , 0 , 0 ,,
    3.00    3.00
 -718.17  281.83
    3.00    3.00
 -718.20  281.80
BR Coef=-1 , 0 , 0 ,, 0 ,,,0.8,0,1,0,
WSPro=,,,, 1 ,,,, 0 ,,,, 0 ,,,,-1 ,-1 ,-1 , 0 , 0 , 0 , 0 , 0
BC Design=,, 0 ,, 0 ,,,,,,

Type RM Length L Ch R = 1 ,12630.99,580.565700,580.565700,580.565700
XS GIS Cut Line= 6
 673094.91103411731312.752578614672882.074288845731031.394360259
672771.657622129730862.644360244672540.407622159730806.394360259
672324.782622159730512.644360244672260.443214487730435.799546578
#Sta/Elev= 30
9318.419402.67459351.423388.33579378.295379.47719428.451367.19559453.529 363.126
9478.606355.32429503.684343.96649516.223336.20619528.762326.25319541.301324.3155
9616.634324.79059629.073 322.1629684.131305.05289757.187302.96989798.357 292.943
9858.109289.07839931.184277.33419951.768275.85789962.059273.80689989.838 260.516
10013.52259.7745 10034.1  275.6810044.39279.342510054.68280.899810064.98280.3413
10106.14287.3783 10272.1292.549910298.67290.375210472.34290.707110575.49 287.577
#Mann= 3 , 0 , 0
9318.419    0.04       09318.419    0.04       010575.49    0.04       0
#XS Ineff= 2 , 0
       0                               0
Bank Sta=9318.419,10575.49
Exp/Cntr=0.3,0.1

Type RM Length L Ch R = 1 ,12050.42,622.416900,622.416900,622.416900
XS GIS Cut Line= 6
673117.555714949731297.970634177672827.183334053730909.563309699
672793.850000709730779.007754162672813.294445157730640.118865252
673013.294445217730423.452198595673011.967847506 730063.22776799
#Sta/Elev= 30
9002.824401.19169038.276385.18319084.447369.44789162.218352.95739188.142341.9993
9201.104331.47739214.066 324.5359302.564324.42879326.486315.47959350.408309.7625
9362.369304.97099422.174303.67389470.018294.49029534.475291.68529586.079281.2895
9647.468279.40259748.443271.27439847.433269.64859940.289270.73339978.712265.4599
9992.477257.02859998.496255.400910013.05259.716310042.15279.3256 10056.7282.6213
10127.43281.699810157.44279.030710197.46280.249110257.48 277.30910419.41 274.935
#Mann= 3 , 0 , 0
9002.824    0.12       09002.824    0.12       010419.41    0.12       0
#XS Ineff= 2 , 0
       0                               0
Bank Sta=9002.824,10419.41
Exp/Cntr=0.3,0.1

Type RM Length L Ch R = 1 ,11428.01,249.776100,249.776100,249.776100
XS GIS Cut Line= 6
673389.178393234731120.661385844 673137.37090788730751.323041787
673101.018911216730672.077465066673102.894784743730637.506905364
673194.115199116730318.615563896673211.732437444730051.812648568
#Sta/Elev= 30
9571.146312.06349698.194302.87689722.741302.32149794.387295.92419854.809294.1064
9867.027295.22149891.464292.29849903.682288.67479935.388288.45679940.337287.4629
9964.773269.6671 9989.21254.545510001.45251.276110013.69255.138510025.52261.1546
10037.12265.358110062.32267.793210092.79267.076810103.04267.826210133.19272.7009
10174.99272.022110196.03273.1285 10238.1278.220310248.62278.608710384.17279.4393
10394.53  278.1310404.88274.821110415.24274.481210537.07275.3714 10740.6 271.399
#Mann= 3 , 0 , 0
9571.146    0.06       09571.146    0.06       0 10740.6    0.06       0
#XS Ineff= 2 , 0
       0                               0
Bank Sta=9571.146,10740.6
Exp/Cntr=0.3,0.1

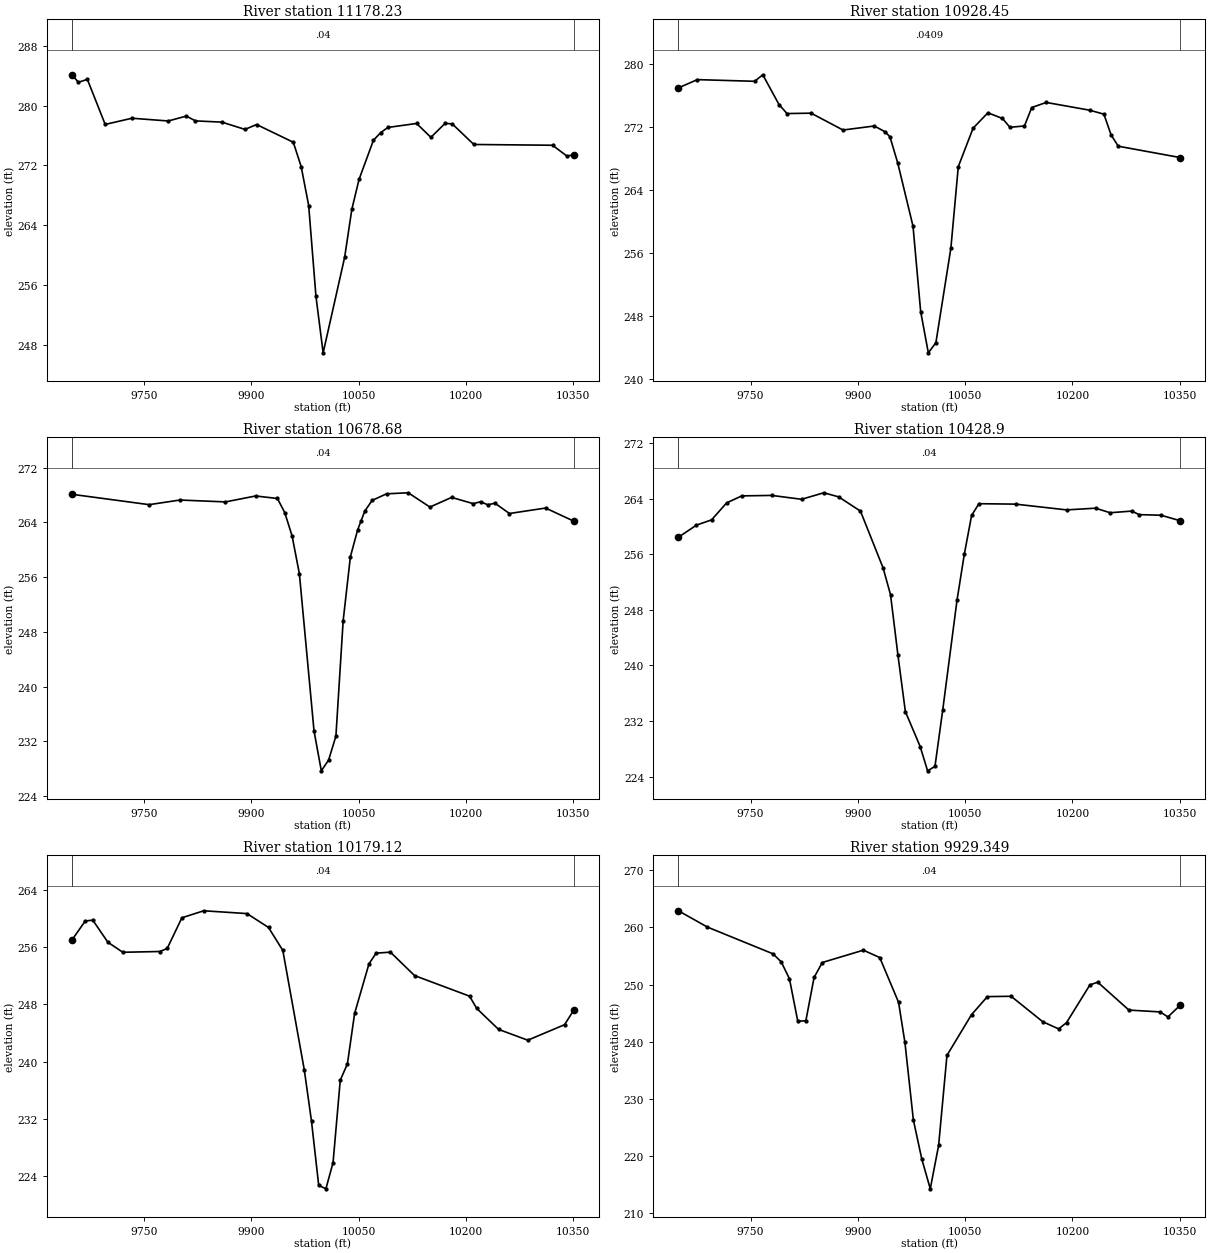
Type RM Length L Ch R = 1 ,11178.23,249.776000,249.776000,249.776000
XS GIS Cut Line= 6
 673482.63697296730862.251396776673319.330349014730650.599315083
673300.504111554730622.780930505 673290.50531502730601.159376819
673272.907993678730431.265420133673279.563924409 730225.22718441
#Sta/Elev= 30
9649.098284.12439658.149283.11689670.631283.51359695.595277.47859733.042 278.309
9783.682277.94049809.115278.59799821.832277.95129858.708277.78769891.082 276.813
9907.269277.46539958.609275.09629969.627271.84549980.147 266.6229990.323254.4699
10000.37246.908810030.45259.700710040.51266.124210050.59270.123510070.73275.3653
10080.81276.372910090.88277.074910131.02277.608110151.05275.750810171.05277.6332
10181.05277.539410211.06274.795510321.17274.692810341.19273.249110350.97273.4059
#Mann= 3 , 0 , 0
9649.098    0.04       09649.098    0.04       010350.97    0.04       0
#XS Ineff= 2 , 0
       0                               0
Bank Sta=9649.098,10350.97
Exp/Cntr=0.3,0.1

Type RM Length L Ch R = 1 ,10928.45,249.776100,249.776100,249.776100
XS GIS Cut Line= 6
673677.357109018730828.114628737673571.945348973730631.383604809
 673515.52957184730492.994156481673496.053407373730420.928865576
673483.123630365730350.784685718673465.368091944 730168.50914804
#Sta/Elev= 30
9649.028 277.0059675.479278.05939755.582277.84699767.025278.67659789.715274.8871
9800.928273.73969834.566  273.799879.246271.64279923.023 272.1599938.571271.3922
9944.912270.76449955.725 267.454 9977.13259.39699987.832248.52929998.534 243.281
10009.11 244.56810030.08 256.61610040.44266.985410061.15271.878410081.87273.8373
10102.26273.113910112.64271.992910132.98272.160410143.15274.509810163.49275.1532
10223.98274.172110244.11273.661410254.14271.019110264.17269.583610350.95 268.136
#Mann= 3 , 0 , 0
9649.028  0.0409       09649.028  0.0409       010350.95  0.0409       0
#XS Ineff= 2 , 0
       0                               0
Bank Sta=9649.028,10350.95
Exp/Cntr=0.3,0.1

Type RM Length L Ch R = 1 ,10678.68,249.776100,249.776100,249.776100
XS GIS Cut Line= 6
673877.000306208730794.019302787673845.027316105730722.724508429
673813.207224603730643.221928006673779.298841295730534.004992031
673759.650998852730441.487796404673710.979040702730115.911197528
#Sta/Elev= 30
9649.032268.1026 9757.03266.58819800.115267.26519863.759266.99139905.919267.8588
9936.423267.49139946.654265.42499956.886262.03089967.117256.4877 9987.58233.5142
9997.812 227.67110008.02229.255210018.21232.748610028.35249.626910038.46258.9779
10048.57262.885310053.25264.191210058.69265.6551 10068.8267.205310089.02268.1733
10119.35268.325210149.69266.237210180.02267.650810210.35266.733810220.46267.0141
10230.58266.574610240.69266.794810260.91265.295410311.46 266.09310350.99264.1697
#Mann= 3 , 0 , 0
9649.032    0.04       09649.032    0.04       010350.99    0.04       0
#XS Ineff= 2 , 0
       0                               0
Bank Sta=9649.032,10350.99
Exp/Cntr=0.3,0.1

Type RM Length L Ch R = 1 , 10428.9,249.776100,249.776100,249.776100
XS GIS Cut Line= 6
674099.742737828730718.856316071674072.137884207730638.434133909
674048.550154378730561.641137034673995.757337008730367.882457695
673966.167124809730231.370621584673932.150810865730038.246177311
#Sta/Elev= 30
9649.019258.45279674.241260.19519695.387260.95249716.532 263.4039737.639264.4018
9779.484264.47079821.266263.91249852.368264.84969873.103264.26169903.625 262.212
9935.308254.02679945.676250.18559956.043241.48489966.411233.36749987.145 228.326
9997.513224.833310007.85225.475810018.78233.660610038.62249.356610048.85255.9917
10059.08261.587810069.31263.278110120.48263.215410191.82262.387110232.43262.6319
10252.74261.9761 10283.2262.216610293.36261.703310323.82261.621610350.98 260.821
#Mann= 3 , 0 , 0
9649.019    0.04       09649.019    0.04       010350.98    0.04       0
#XS Ineff= 2 , 0
       0                               0
Bank Sta=9649.019,10350.98
Exp/Cntr=0.3,0.1

Type RM Length L Ch R = 1 ,10179.12,249.776000,249.776000,249.776000
XS GIS Cut Line= 6
674298.982445722 730712.63660392 674267.04972046730610.272881631
674246.392663942730508.787957905 674241.20874526730429.249231088
674250.048644785730241.282580687674210.254728043730022.344938357
#Sta/Elev= 30
9649.045257.00019667.636259.65719678.177259.78079699.259256.69259720.176255.2876
9771.975255.39559782.239255.81619802.767260.10679833.334 261.0869893.868260.6941
9923.922258.75369943.932255.54789973.993238.83639984.045231.67019994.097222.7337
10004.15 222.23110014.19225.894710024.24 237.40310034.28239.695910044.33246.7448
 10064.4253.6691 10074.4255.161610094.41255.306910128.13252.032910205.03 249.156
10215.15247.435610245.64244.511910286.52243.001710337.92245.167510350.93247.2225
#Mann= 3 , 0 , 0
9649.045    0.04       09649.045    0.04       010350.93    0.04       0
#XS Ineff= 2 , 0
       0                               0
Bank Sta=9649.045,10350.93
Exp/Cntr=0.3,0.1

Type RM Length L Ch R = 1 ,9929.349,249.776100,249.776100,249.776100
XS GIS Cut Line= 6
674656.975647474730620.271756037674515.587042538730369.445194322
674481.522796955 730315.21045228674458.514593132730277.063492807
674397.592338353730149.207566374674332.005783898729999.137671104
#Sta/Elev= 30
9649.021262.9138 9689.51260.06729781.345255.38479792.824253.97429804.304251.0254
9815.961243.60369827.262 243.6879838.741251.25099850.221253.87039907.617256.0242
9930.576254.74089956.906246.91149965.792239.89759977.589226.36359989.387219.5168
10001.25214.303510012.92221.8982 10024.6237.645410058.91 244.74310081.07247.9055
 10114.3 247.96710158.61243.513610180.76242.266410191.77243.348610224.51249.9562
10235.42250.428210279.08245.551710322.73245.234710333.64244.354310350.95246.4345
#Mann= 3 , 0 , 0
9649.021    0.04       09649.021    0.04       010350.95    0.04       0
#XS Ineff= 2 , 0
       0                               0
Bank Sta=9649.021,10350.95
Exp/Cntr=0.3,0.1

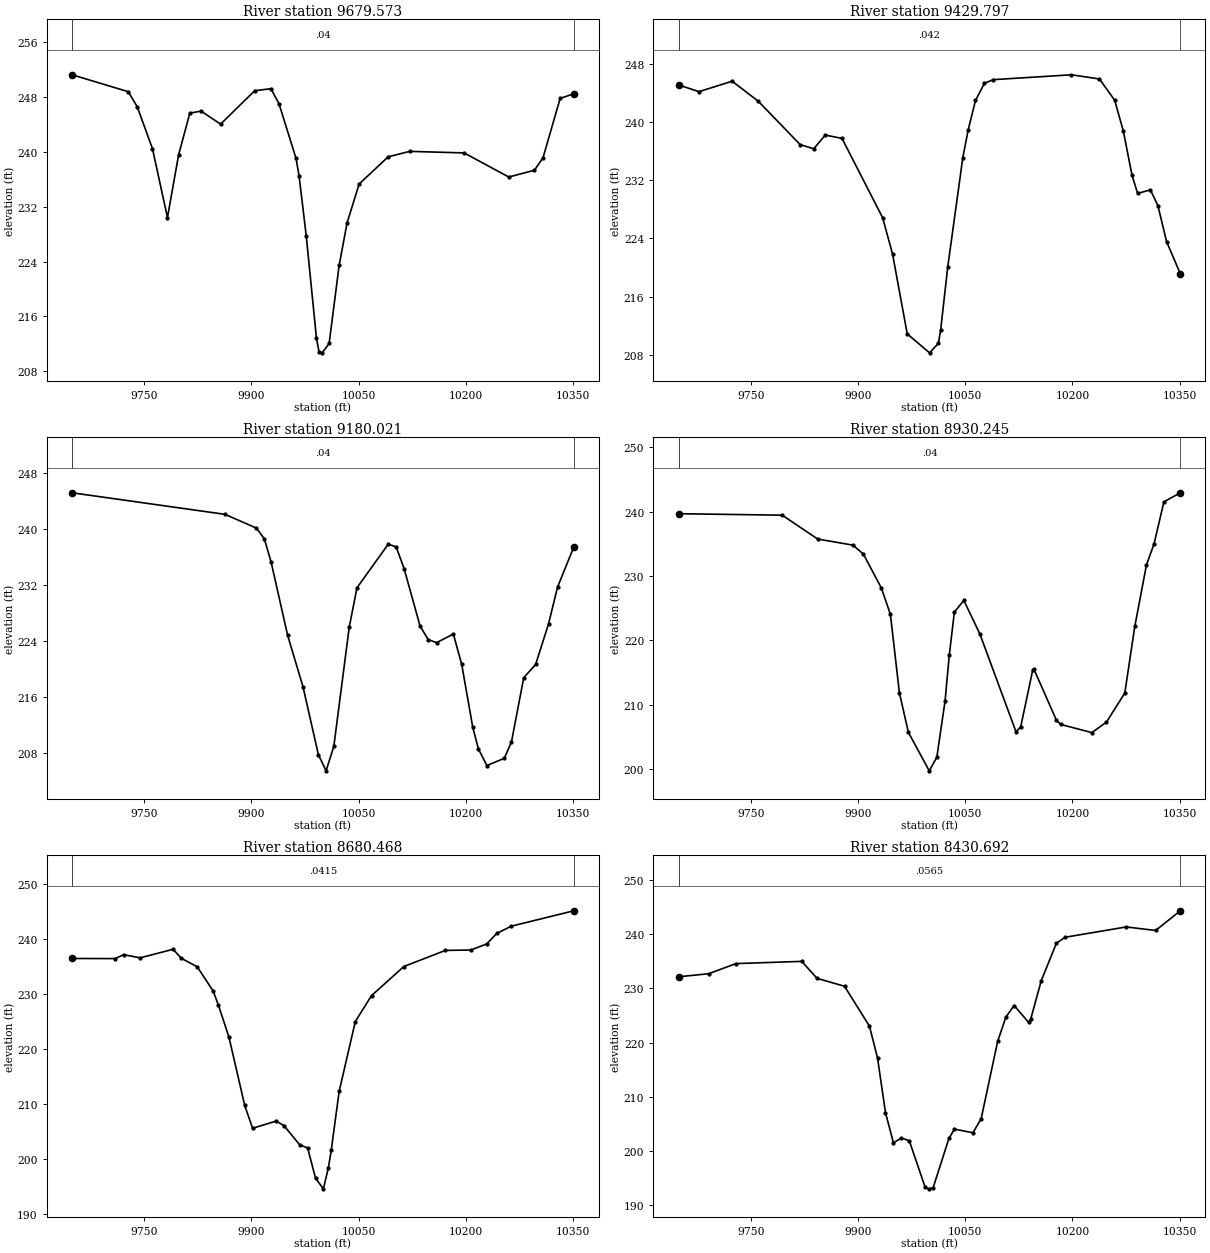
Type RM Length L Ch R = 1 ,9679.573,249.776100,249.776100,249.776100
XS GIS Cut Line= 6
674896.243848585730417.743714881674773.259731523730261.654753797
674607.196824913730088.320832773674552.677696629730026.531696021
674504.835658897729964.228172043674448.611965451729878.978095737
#Sta/Elev= 30
9649.024251.26439727.697248.79369740.236 246.5859761.474240.47919782.456230.4402
9798.109239.61089813.762245.67129829.415245.96379856.816 244.0669904.444248.9372
9927.253249.23469938.542 247.0189962.348239.05369966.581236.49519976.616227.7503
9990.884212.80489994.619210.7763    9999210.695310008.65212.083110022.62223.4571
10033.76229.678510050.58235.329110091.19239.296710121.42240.091410197.42239.8627
10259.88236.348510295.82237.336810307.79239.153310331.75247.811610350.94248.5016
#Mann= 3 , 0 , 0
9649.024    0.04       09649.024    0.04       010350.94    0.04       0
#XS Ineff= 2 , 0
       0                               0
Bank Sta=9649.024,10350.94
Exp/Cntr=0.3,0.1

Type RM Length L Ch R = 1 ,9429.797,249.776100,249.776100,249.776100
XS GIS Cut Line= 6
675035.312884956730269.127450977674972.361078535730170.334826111
674882.348652007730022.007919309674810.077381433729933.114831995
674780.192142999729893.289882196674641.441124084729689.083168344
#Sta/Elev= 30
9649.031245.08759677.641244.16299724.048245.60099760.644242.84169819.205236.8923
9838.191236.32159854.297238.20039877.692237.74519934.568226.84519948.378221.8845
9968.954210.900310000.18208.299210012.57209.608510015.66211.405110025.66220.1128
10046.67235.0835 10054.3238.952910064.45242.952110076.95245.314610089.45245.8118
10198.74246.481210237.88245.902910259.19 242.97310271.28 238.74310283.37232.6906
10291.26230.188110309.06230.684510319.64228.510810331.73223.581610350.98219.1487
#Mann= 3 , 0 , 0
9649.031   0.042       09649.031   0.042       010350.98   0.042       0
#XS Ineff= 2 , 0
       0                10097.38       0
Bank Sta=9649.031,10350.98
Exp/Cntr=0.3,0.1

Type RM Length L Ch R = 1 ,9180.021,249.776000,249.776000,249.776000
XS GIS Cut Line= 6
675240.674377096730218.981974852675186.234726129730134.669589272
675135.992291019730043.969887002675020.600452372729780.490218395
674976.324084596729707.479632322674902.887653034729606.760763785
#Sta/Elev= 30
9649.038245.24169862.973242.1568 9906.97240.1833 9917.97238.66069927.519235.3073
9950.507224.86519972.055217.49629993.603 207.77710004.35205.467210015.16208.9603
10036.77226.044510047.58231.655110091.34237.892710102.47237.4901 10113.6234.3482
10135.86226.1574 10147.3224.232310158.99223.805410182.38225.037210194.08220.6823
10209.53211.695610217.47208.590810229.28206.226610253.62207.257810263.69209.6099
10280.83218.795210297.48220.686110315.61226.524910328.12231.750110350.93237.5074
#Mann= 3 , 0 , 0
9649.038    0.04       09649.038    0.04       010350.93    0.04       0
#XS Ineff= 2 , 0
       0                10077.87       0
Bank Sta=9649.038,10350.93
Exp/Cntr=0.3,0.1

Type RM Length L Ch R = 1 ,8930.245,249.776100,249.776100,249.776100
XS GIS Cut Line= 6
675504.299247246729980.534573184675392.559871099729883.138655552
675252.345138145729775.855952028 675207.78798472729710.680213067
675074.280484186729608.261122706674978.190268099729522.723653167
#Sta/Elev= 30
9649.131239.65969794.189239.43119843.687235.72379893.056 234.778 9907.63233.3877
9932.813228.10889945.404224.02749957.996211.83899970.587205.6822 9999.77199.7115
10010.38201.832410021.85210.563610027.74217.644910034.88224.382810048.16226.1822
10070.57220.966910121.24205.725710127.74206.597210144.38215.337410146.25215.4766
10177.68207.553810183.78206.9158 10227.2 205.64910247.62207.293710273.22 211.796
10287.18222.137510303.53231.700710314.22235.010610327.89241.501110350.87242.9113
#Mann= 3 , 0 , 0
9649.131    0.04       09649.131    0.04       010350.87    0.04       0
#XS Ineff= 2 , 0
       0                 10038.4       0
Bank Sta=9649.131,10350.87
Exp/Cntr=0.3,0.1

Type RM Length L Ch R = 1 ,8680.468,249.776100,249.776100,249.776100
XS GIS Cut Line= 6
675634.973831614729712.166199583675510.883837324 729635.17037987
675308.978926753729540.625411692675212.113107259729489.403320443
675111.035918502729424.363423555675029.781698342729361.090055232
#Sta/Elev= 30
9649.056236.37359709.393236.35619721.121237.06889744.223236.49229790.428238.0468
9801.753236.41829824.086234.87489846.419230.46189853.688227.92529868.535222.0702
9890.547209.67039901.553205.5196 9934.57206.83149945.575205.97449967.587 202.498
9978.593  201.939989.598196.445410000.58194.513610007.53198.307510011.54201.4827
10022.65212.222110045.28224.9204 10067.9229.622210113.15234.915210171.15237.8379
 10206.9237.920710229.03239.013610243.17240.942110263.59242.250710350.96245.0445
#Mann= 3 , 0 , 0
9649.056  0.0415       09649.056  0.0415       010350.96  0.0415       0
#XS Ineff= 2 , 0
       0                               0
Bank Sta=9649.056,10350.96
Exp/Cntr=0.3,0.1

Type RM Length L Ch R = 1 ,8430.692,249.776100,249.776100,249.776100
XS GIS Cut Line= 6
675746.196630971729539.067712375675670.595929124729470.417087917
675595.774698016729413.652521069675337.447505007729274.781697606
675253.952720327729216.548390201675168.639596098729146.439436466
#Sta/Elev= 30
9649.082232.14279691.221232.70729729.509234.57769821.432234.98469842.848231.8553
9881.253230.3967 9916.13223.03839927.432217.17459938.545207.08399949.657 201.533
 9960.77202.41499971.882 201.8969994.107193.3014    9999193.040510005.19193.2493
10027.36202.367410035.01204.053110060.85203.375810072.38205.976510095.42220.2211
10106.94224.716310118.47226.845410138.69223.740310141.63 224.31110156.42231.4209
 10177.6238.3216 10189.8239.432110275.33241.334910316.37240.684110350.95244.3157
#Mann= 3 , 0 , 0
9649.082  0.0565       09649.082  0.0565       010350.95  0.0565       0
#XS Ineff= 2 , 0
       0                               0
Bank Sta=9649.082,10350.95
Exp/Cntr=0.3,0.1