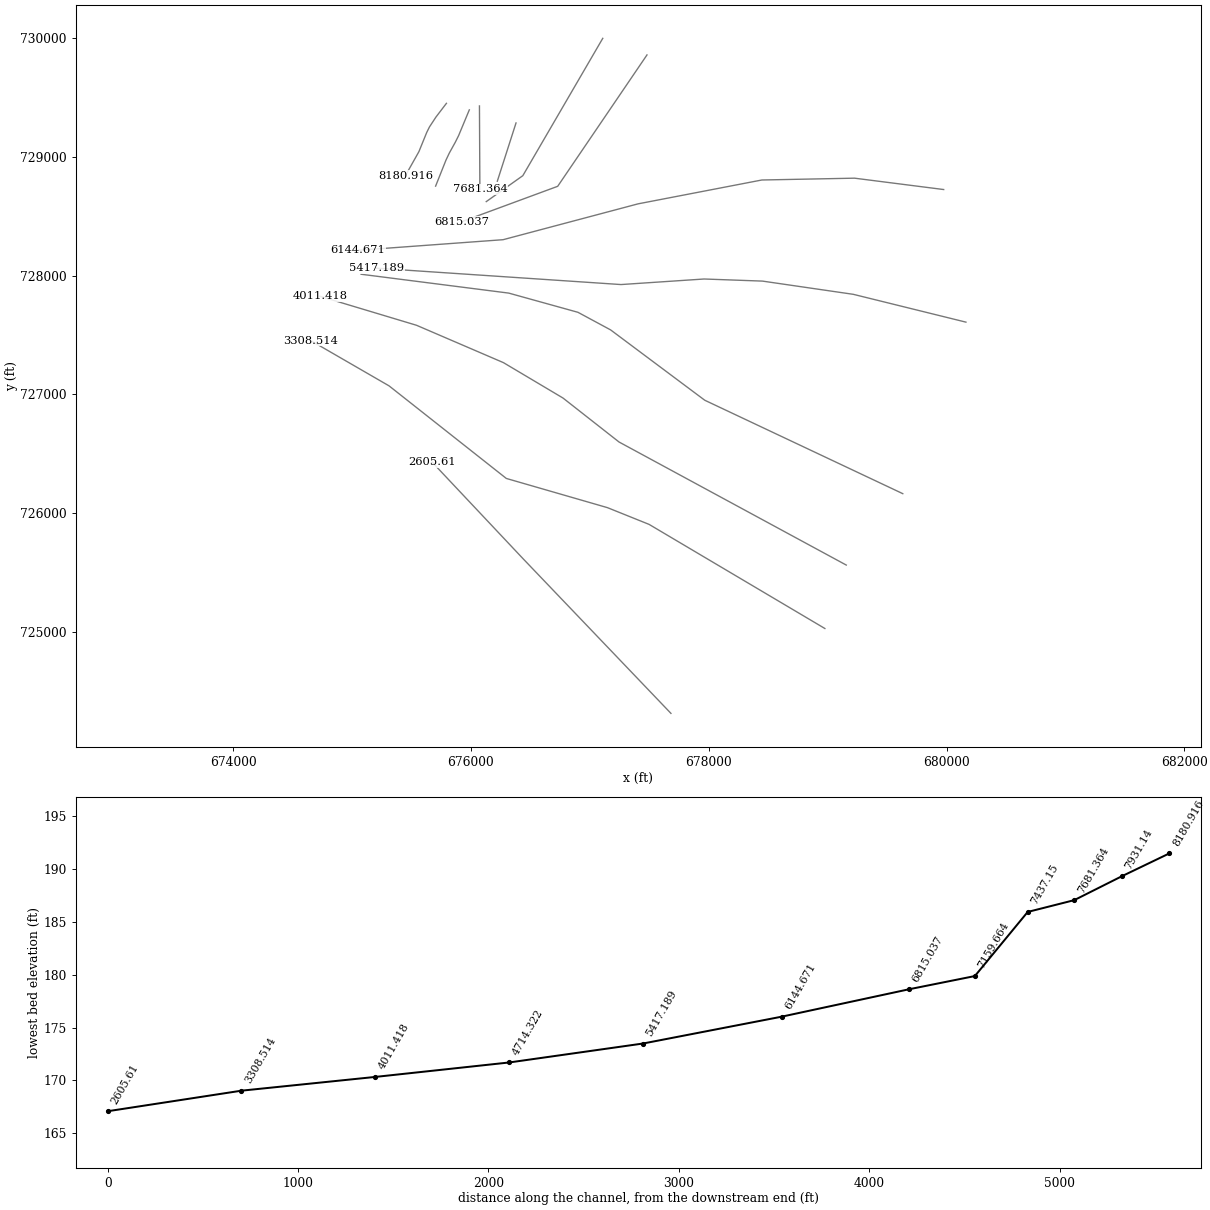
HEC-RAS study 4078_ras.prj: 4078

--- 4078_ras.g01 (geometry) --- (continued)

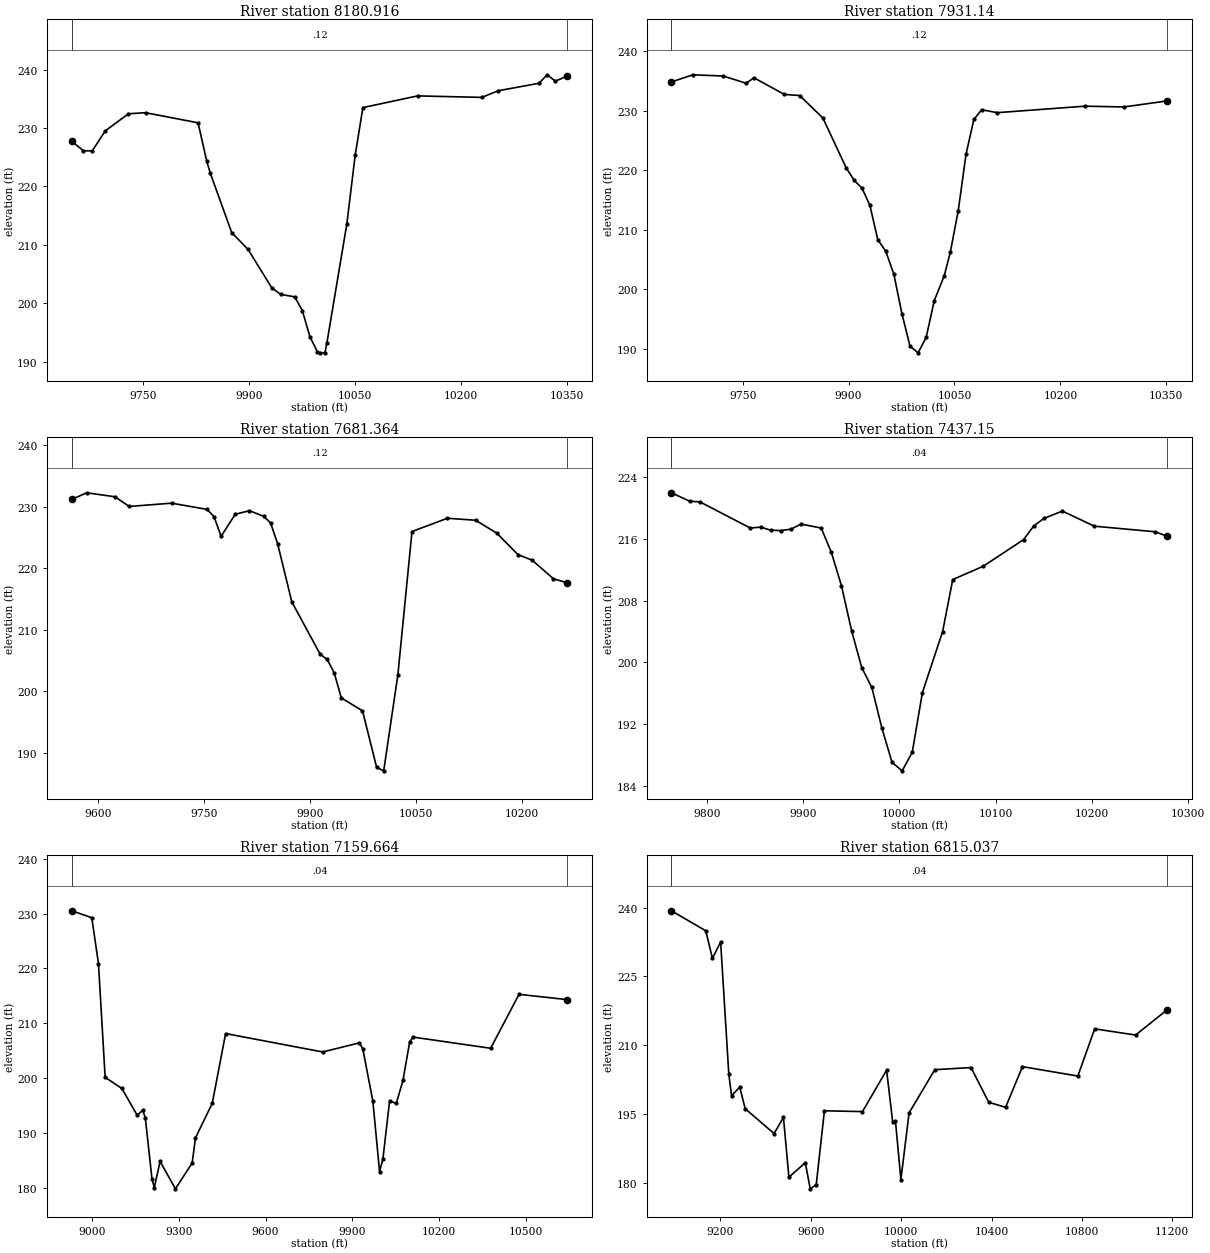
Type RM Length L Ch R = 1 ,8180.916,249.776000,249.776000,249.776000
XS GIS Cut Line= 6
675793.753112865 729448.09509894675705.674536075729332.718469806
 675650.99976796729249.380998072675628.261053702729203.564574771
675562.379885905729041.827494581675449.085284896728840.354828216
#Sta/Elev= 30
9649.052227.73479665.527226.12739678.108226.10499696.437229.52519729.397232.4645
9753.593232.64249827.982230.91489840.168224.37679845.143222.33059875.577212.1104
9898.808209.2139  9932.3202.64489945.066201.50829964.931  201.099975.631 198.736
9986.332194.27869997.032191.6604   10001191.497310007.73191.522410010.49193.2302
10038.65213.557310050.51225.369610061.42233.519110138.84235.525410229.87235.2693
10253.02236.406310310.88237.688310322.45239.143310334.02238.044310350.97 238.931
#Mann= 3 , 0 , 0
9649.052    0.12       09649.052    0.12       010350.97    0.12       0
#XS Ineff= 2 , 0
       0                               0
Bank Sta=9649.052,10350.97
Exp/Cntr=0.3,0.1

Type RM Length L Ch R = 1 , 7931.14,249.776100,249.776100,249.776100
XS GIS Cut Line= 6
675986.367040751729393.261824034675896.342734277729176.897820272
675868.821974737729121.698344773675818.014536071729029.847524623
675789.979341245728970.579171924675702.873605576728751.919475298
#Sta/Elev= 30
9649.016234.85129679.515236.05649722.681235.84569755.055234.62389765.847235.5669
9809.013232.7525 9830.82232.56569863.602228.79239896.678220.41829907.852218.3176
9919.026217.0093  9930.2214.12359941.374208.35359952.732206.39679964.181202.5416
 9975.63195.87429987.079190.45789998.528189.331510009.96191.927810021.36198.0851
10035.48202.258910044.16206.244310055.39213.247910066.46222.752510077.52228.5588
10088.58  230.18 10110.7229.687810234.86230.780910289.99230.648510350.98231.6575
#Mann= 3 , 0 , 0
9649.016    0.12       09649.016    0.12       010350.98    0.12       0
#XS Ineff= 2 , 0
       0                               0
Bank Sta=9649.016,10350.98
Exp/Cntr=0.3,0.1

Type RM Length L Ch R = 1 ,7681.364,244.214000,244.214000,244.214000
XS GIS Cut Line= 2
676071.584782362729426.203738317676075.160778582728725.308477148
#Sta/Elev= 30
9562.846231.1879 9584.05232.2619 9624.05231.61139644.051230.03789704.051230.5716
9754.052229.56479764.052228.39769774.052225.18329794.053228.76729814.053229.3482
9834.053228.45469844.053227.36569854.053 223.9639874.054214.53149914.054206.0574
9924.054205.17179934.054 202.9999944.055 198.9219974.055196.82819994.055187.6322
10004.06187.069610024.06202.643510044.06225.963510094.06228.119710134.06227.7955
10164.06225.689110194.06222.195210214.06221.307610244.06218.289910263.75217.6259
#Mann= 3 , 0 , 0
9562.846    0.12       09562.846    0.12       010263.75    0.12       0
#XS Ineff= 2 , 0
       0                               0
Bank Sta=9562.846,10263.75
Exp/Cntr=0.3,0.1

Type RM Length L Ch R = 1 , 7437.15,277.486000,277.486000,277.486000
XS GIS Cut Line= 2
676379.120458156 729283.16388911676221.776624024728793.252405539
#Sta/Elev= 30
9763.334221.97639782.412220.87649792.915220.8024 9845.43217.40249855.934 217.531
9866.437217.1287 9876.94217.07839887.443217.25869897.946217.92649918.952217.4042
9929.455214.25149939.958209.92229950.461204.11749960.964199.33539971.468196.7535
9981.971191.46929992.474 187.04910002.98185.953610013.48188.374410023.98196.0862
10044.99204.001110055.49210.7347   10087 212.44810129.01215.904110139.52217.6578
10150.02 218.64710169.24 219.60610202.54217.648910265.55216.924810277.89216.3654
#Mann= 3 , 0 , 0
9763.334    0.04       09763.334    0.04       010277.89    0.04       0
#XS Ineff= 2 , 0
       09814.247                       0
Bank Sta=9763.334,10277.89
Exp/Cntr=0.3,0.1

Type RM Length L Ch R = 1 ,7159.664,344.627600,344.627600,344.627600
XS GIS Cut Line= 3
677108.623689145729994.787138969676436.336397856728839.740356535
676128.800722003728621.604586452
#Sta/Elev= 30
8930.011230.50538999.188 229.2449022.329220.8975 9045.47200.17829103.323198.1503
9155.885193.30869175.764 194.1669184.316192.80979207.457181.65969215.523180.1244
9235.402184.87719288.451179.88189346.304184.58539357.874189.17539415.727195.4342
9462.009208.15279797.555204.80029924.831206.46139936.402205.35999971.113195.8437
9994.254183.037410005.82185.268710028.97195.869610052.11195.436310075.25199.6215
10098.39206.623110109.96207.507910378.44205.475210476.52215.291510643.51214.3305
#Mann= 3 , 0 , 0
8930.011    0.04       08930.011    0.04       010643.51    0.04       0
#XS Ineff= 2 , 0
       0 9868.49                       0
Bank Sta=8930.011,10643.51
Exp/Cntr=0.3,0.1

Type RM Length L Ch R = 1 ,6815.037,670.365300,670.365300,670.365300
XS GIS Cut Line= 3
677480.527297139729855.323285967 676729.56808877728750.340450749
 675924.96893689728453.532763645
#Sta/Elev= 30
8982.797239.29729134.956234.9416 9164.55228.92039200.822232.48779237.094203.6053
9249.185198.95269285.458200.82879309.639196.11269437.399190.6999 9478.91194.2254
9503.092181.17959575.637184.33839597.515 178.635    9624179.53719660.272195.6619
9828.795195.48729935.539204.52189962.542193.17169974.633193.45589998.814180.6585
10035.09195.206210149.03204.630410309.14205.094910387.63197.523310462.24 196.416
10536.85205.2918   10782203.242710856.61213.534711037.81212.187711176.41 217.661
#Mann= 3 , 0 , 0
8982.797    0.04       08982.797    0.04       011176.41    0.04       0
#XS Ineff= 2 , 0
       09887.612                       0
Bank Sta=8982.797,11176.41
Exp/Cntr=0.3,0.1

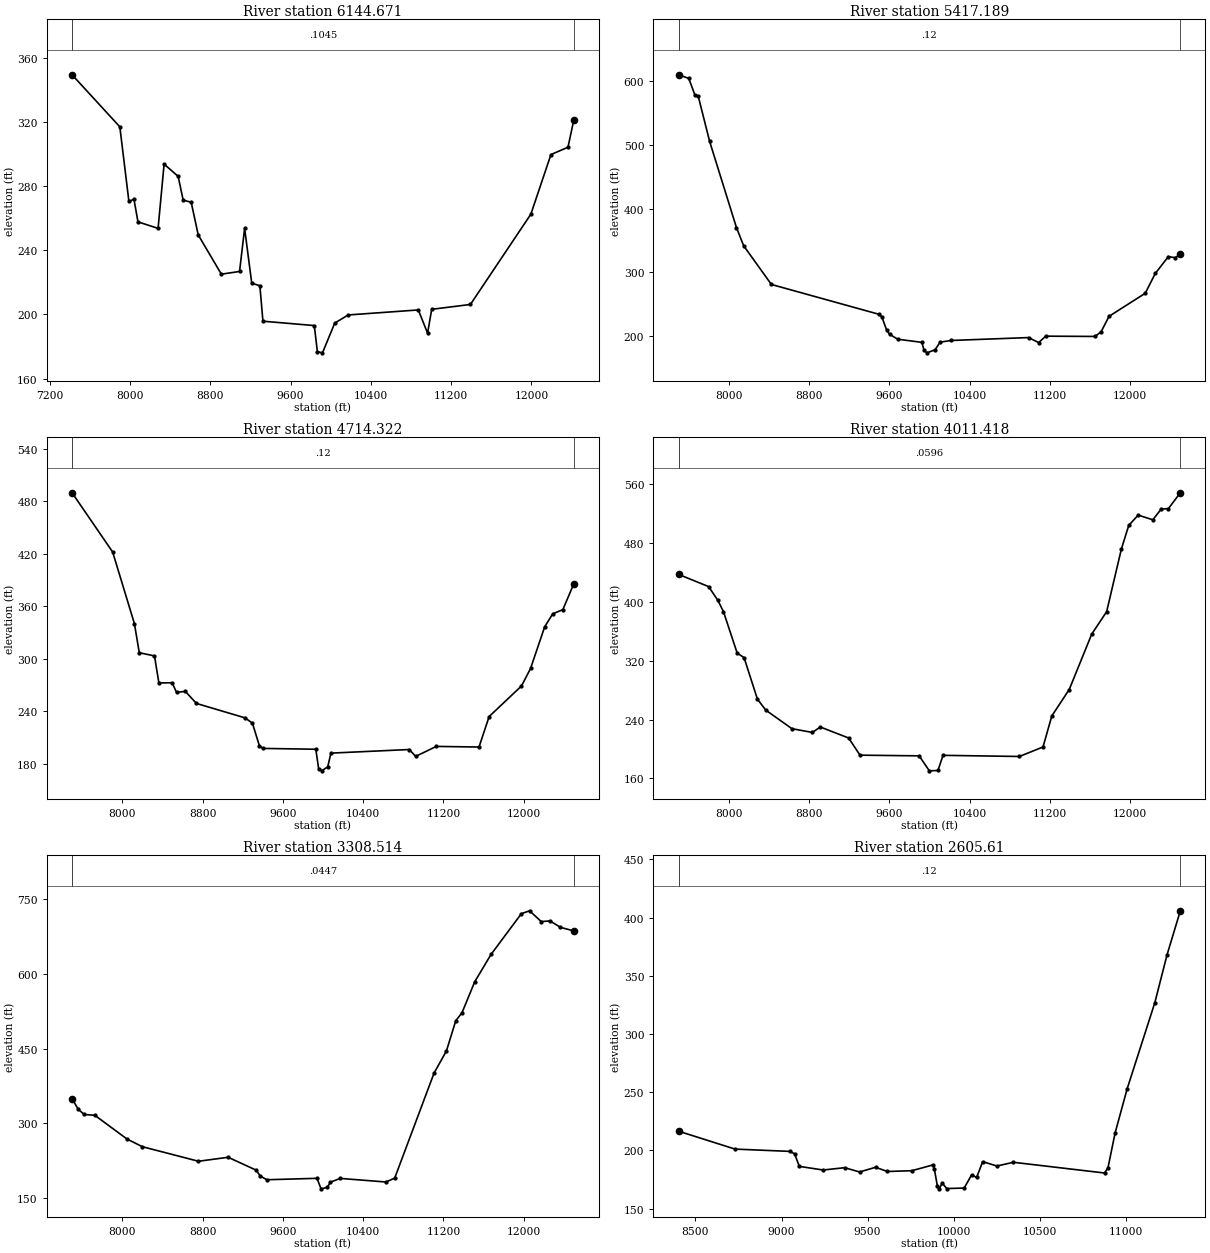
Type RM Length L Ch R = 1 ,6144.671,727.482300,727.482300,727.482300
XS GIS Cut Line= 6
679975.752335821728723.149038717679226.070561078728818.737594944
678446.656534909728803.441360011677405.602721533728602.830288013
676270.479782708728301.364004812675046.473478625 728211.86122282
#Sta/Elev= 30
7421.409349.36957897.533316.92797988.028270.38068038.271271.79018078.389257.6798
8278.803253.62128338.856293.66658478.882286.04288528.883 271.2048608.902269.9192
8678.935  249.538909.578225.07199090.848226.75589141.359253.64429212.271219.4858
9293.525217.83649323.995195.75299836.015193.03699866.584176.78329917.532176.0328
10040.15194.606810174.73199.653710872.78202.775310965.35188.266211006.24203.1717
11392.06206.188111994.69262.467712194.79 299.624 12364.8304.200212423.33321.3742
#Mann= 3 , 0 , 0
7421.409  0.1045       07421.409  0.1045       012423.33  0.1045       0
#XS Ineff= 2 , 0
       09612.909                       0
Bank Sta=7421.409,12423.33
Exp/Cntr=0.3,0.1

Type RM Length L Ch R = 1 ,5417.189,702.867200,702.867200,702.867200
XS GIS Cut Line= 6
680162.919509955727607.980117214679215.789231877727841.898732041
678451.990406056727953.126315029677961.265437891 727970.80258938
677261.940217999727924.059401613675205.837185775728061.912227297
#Sta/Elev= 30
7499.048 610.1737600.967604.55017663.315 577.908  7694.4577.10777808.378505.8758
8076.511 370.1538148.449  341.598424.747280.87099494.661234.12879524.689230.4363
9574.699208.63759604.705202.38939684.713194.88689925.105189.94629945.219177.9313
9975.439 173.49310056.22178.324110106.48190.282710216.89192.921410988.63197.4707
11088.97 189.56211159.18199.679411650.22199.220711710.31206.306111790.43230.8548
12150.96266.991812251.15298.125312381.48324.629412451.66322.878112500.95328.7671
#Mann= 3 , 0 , 0
7499.048    0.12       07499.048    0.12       012500.95    0.12       0
#XS Ineff= 2 , 0
       0                               0
Bank Sta=7499.048,12500.95
Exp/Cntr=0.3,0.1

Type RM Length L Ch R = 1 ,4714.322,702.904000,702.904000,702.904000
XS GIS Cut Line= 6
679631.731834917726165.494640811677966.323369832726951.238455053
 677174.98904807727542.511733145676899.945548977727690.700353189
 676318.06898011727852.148795566675076.204342308  728010.7902649
#Sta/Elev= 30
7499.034489.75927903.586422.00338120.712339.97038168.962306.81858320.494303.1555
8364.448272.20818496.309272.46538540.263261.46168628.186262.62038738.447248.7931
9223.296232.29279296.835226.22549365.512200.63759400.172 197.3499928.576196.4024
9956.919174.24099987.535171.698210047.55176.286810079.14191.964810861.37196.0945
10923.78188.207911129.61 199.64311555.48198.929711656.35233.792311978.65268.7497
12069.26288.7666 12210.2336.479912290.74351.350912391.41356.105612500.94385.8298
#Mann= 3 , 0 , 0
7499.034    0.12       07499.034    0.12       012500.94    0.12       0
#XS Ineff= 2 , 0
       0                               0
Bank Sta=7499.034,12500.94
Exp/Cntr=0.3,0.1

Type RM Length L Ch R = 1 ,4011.418,702.904000,702.904000,702.904000
XS GIS Cut Line= 6
679156.490851717725564.984790324677245.381245207726599.965097074
676774.212463015726969.673533421676273.332312556 727267.38525373
675542.384857409727581.600071216674730.381620297727825.472670794
#Sta/Elev= 30
 7499.08437.20537798.474420.64557889.847402.22267946.863386.6461  8083.7330.2474
8152.119324.15488285.702267.6655 8368.28 252.843 8629.32227.60258833.172222.4683
 8912.35229.88579195.126 214.8999307.806191.62379897.655190.6921    9999170.3298
10084.81 170.80410135.64191.392510896.18189.828111132.26202.745411220.06244.9202
11393.55280.818111618.12 356.15411766.33386.508611913.57471.783411986.98503.7464
12080.92517.736212226.67511.364912309.78 525.82612382.31526.588712500.93548.0532
#Mann= 3 , 0 , 0
 7499.08  0.0596       0 7499.08  0.0596       012500.93  0.0596       0
#XS Ineff= 2 , 0
       0                               0
Bank Sta=7499.08,12500.93
Exp/Cntr=0.3,0.1

Type RM Length L Ch R = 1 ,3308.514,702.904100,702.904100,702.904100
XS GIS Cut Line= 6
678976.710777416725031.381688725677498.214330481725907.073503506
677148.535439454726047.694573696  676297.4726126726293.482110214
675311.331260371727072.083385139674655.179639948727451.351381175
#Sta/Elev= 30
7499.046349.47247560.364328.55037619.652318.08347726.373316.29288045.413 268.992
8199.537253.45988759.081 224.2729054.733232.2598 9331.74206.6757 9375.06194.7856
9440.162 187.2499940.177190.08969981.174169.026510042.65171.796910073.39 182.235
10171.62189.944110628.31182.722910715.01190.510211107.86401.209411230.42445.1113
11323.68505.825511386.06521.885911513.05584.000411675.86638.836411977.57720.2683
12059.61726.114412175.04704.551812263.69705.746212367.52692.901512500.94685.7542
#Mann= 3 , 0 , 0
7499.046  0.0447       07499.046  0.0447       012500.94  0.0447       0
#XS Ineff= 2 , 0
       0                               0
Bank Sta=7499.046,12500.94
Exp/Cntr=0.3,0.1

Type RM Length L Ch R = 1 , 2605.61,0.000000,0.000000,0.000000
XS GIS Cut Line= 3
 677682.00946781724317.703864768 676438.79636851725617.897564441
675673.223242283726430.893698707
#Sta/Elev= 30
8401.707216.58828730.024201.20889048.245199.23699075.917197.20779103.588186.3632
9241.945 183.2399366.467185.2436 9453.68181.56869546.331185.5787 9615.51181.9679
9757.547 182.6529878.388187.55869887.775184.4133 9906.06 169.1339916.715167.0796
9933.731172.03079960.125167.326310061.41167.756510104.82179.133710133.76176.8192
10168.94190.437210251.58186.677510347.73189.874510877.15180.677410897.17185.2974
10938.38215.074311008.43253.006211168.88326.770111240.56368.222911317.34405.8209
#Mann= 3 , 0 , 0
8401.707    0.12       08401.707    0.12       011317.34    0.12       0
#XS Ineff= 2 , 0
       0                               0
Bank Sta=8401.707,11317.34
Exp/Cntr=0.3,0.1